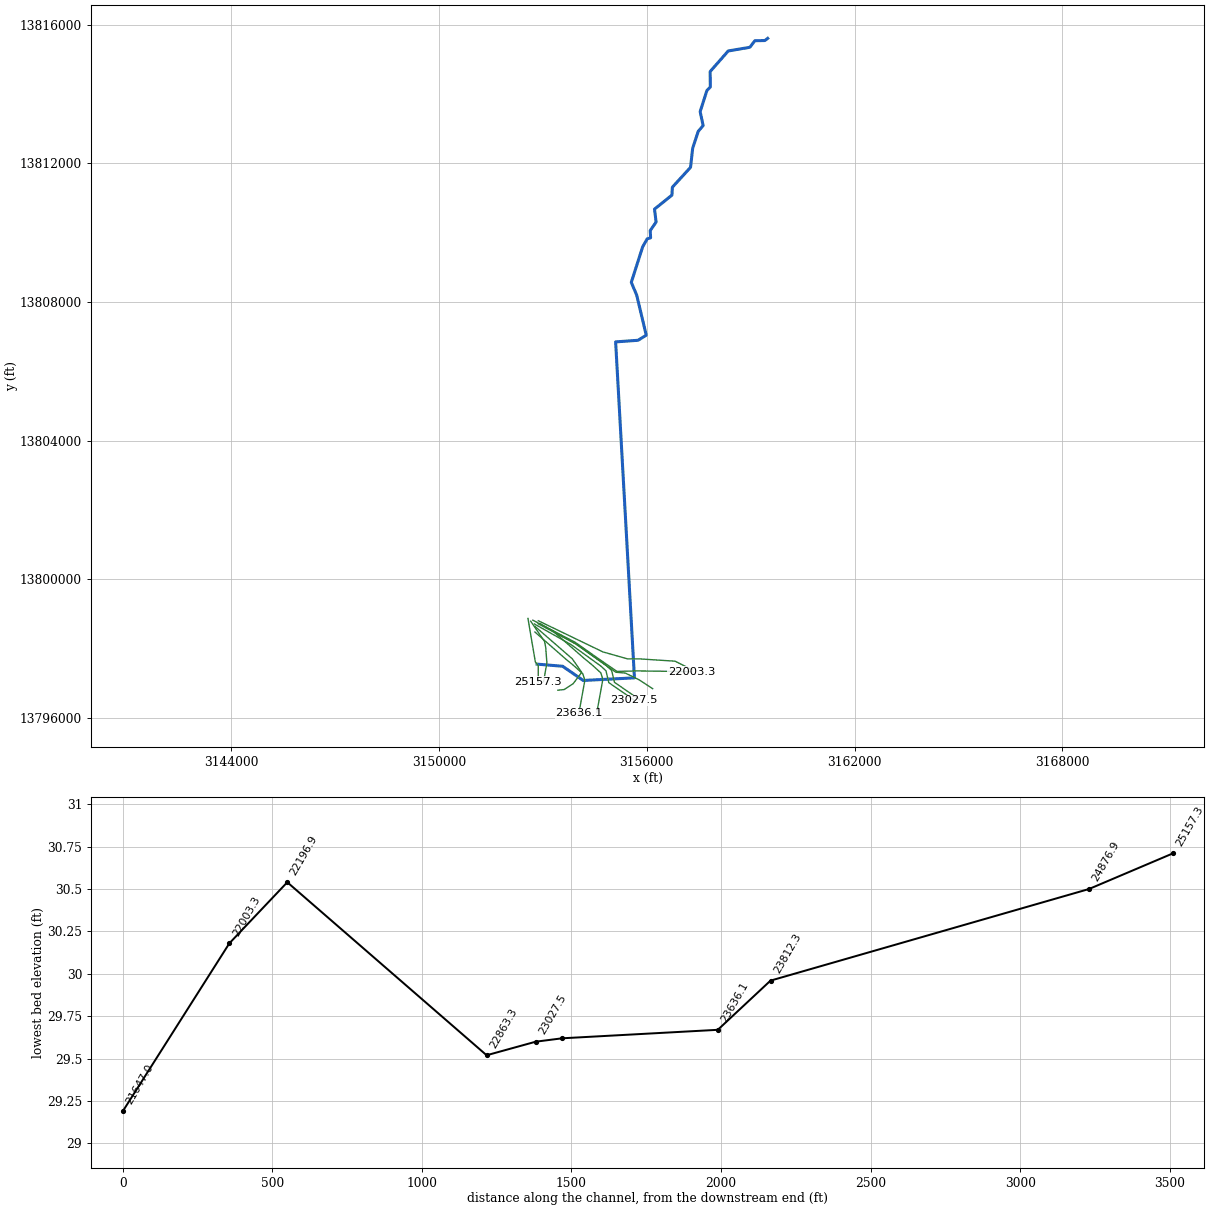
--- C106-01-00.PRJ (project) ---

Proj Title=C106-01-00
Current Plan=p02
Default Exp/Contr=0.3,0.1
English Units
Geom File=g01
Flow File=f01
Flow File=f02
Plan File=p01
Plan File=p02
Y Axis Title=Elevation
X Axis Title(PF)=Main Channel Distance
X Axis Title(XS)=Station
BEGIN DESCRIPTION:
Sims Bayou Watershed
Berry Creek
HCFCD Unit C106-01-00
Flood Hazard Model
10, 2, 1, 0.2% Event
Filename C106-01-00.prj
Prepared by:  Watershed Concepts  Date:
Reviewed by:                      Date:
STATUS FINAL
END DESCRIPTION:
DSS Export Rating Curves= 0
DSS Export Rating Curve Sorted= 0
DSS Export Volume Flow Curves= 0
DXF OffsetX= 0
DXF OffsetY= 0
DXF ScaleX= 1
DXF ScaleY= 10

--- C106-01-00.p02 (plan) ---

Plan Title=Effective Floodway 2015
Program Version=4.10
Short Identifier=RiskMAP FW
Geom File=g01
Flow File=f02
Subcritical Flow
K Sum by GR= 0
Std Step Tol= 0.01
Critical Tol= 0.01
Num of Std Step Trials= 20
Max Error Tol= 0.3
Flow Tol Ratio= 0.001
Split Flow NTrial= 30
Split Flow Tol= 0.02
Split Flow Ratio= 0.02
Log Output Level= 0
Friction Slope Method= 1
Unsteady Friction Slope Method= 2
Unsteady Bridges Friction Slope Method= 1
Parabolic Critical Depth
Global Vel Dist= 0 , 0 , 0
Global Log Level= 0
CheckData=True
Encroach Param=-1 ,0,0, 2
Encroach River=C106-01-00
Encroach Reach=C106-01-00_0009
Encroach Node=25157.3
       1    4950  5025.8
Encroach Node=24876.9
       1    4950  5025.8
Encroach Node=23812.3
       1    4940    5040
Encroach Node=23636.1
       1    4900    5060
Encroach Node=23115.9
       1    4900    5060
Encroach Node=23027.5
       1    4900    5040
Encroach Node=22863.3
       1    4900    5040
Encroach Node=22196.9
       1    4910 5022.22
Encroach Node=22003.3
       1    4956    5036
Encroach Node=21647.0
       1    4890    5030
Encroach Node=21625.0
       1    4890    5030
Encroach Node=20941.0
       1    4920    5230
Encroach Node=19919.1
       1    4920    5230
Encroach Node=19005.0
       1    4800    5062
Encroach Node=18924.0
       1    4800    5062
Encroach Node=17521.5
       1    4435    5260
Encroach Node=16874.6
       1    4410    5225
Encroach Node=15938.0
       1    4620    5290
Encroach Node=15804.5
       1    4620    5290
Encroach Node=15750.9
       1    4650    5290
Encroach Node=15416.4
       1    4700    5300
Encroach Node=15021.9
       1    4810    5480
Encroach Node=14860.6
       1    4910    5570
Encroach Node=14747.6
       1    4910    5570
Encroach Node=14358.4
       1    4800    5725
Encroach Node=13854.3
       1    4700    5250
Encroach Node=13790.4
       1    4620    5250
Encroach Node=13330.4
       1    4760    5250
Encroach Node=13309.6
       1    4770    5200
Encroach Node=13112.9
       1    4850    5200
Encroach Node=13045.4
       1    4850    5200
Encroach Node=12963.8
       1    4850    5200
Encroach Node=12877.2
       1    4850    5175
Encroach Node=12719.3
       1    4910    5175
Encroach Node=12638.3
       1    4910    5175
Encroach Node=12604.9
       1    4910    5175
Encroach Node=12465.9
       1    4810    5250
Encroach Node=12399.3
       1    4810    5250
Encroach Node=11481.3
       1    4456  5024.2
Encroach Node=11252.3
       1    4505  5035.9
Encroach Node=11176.0
       1    4531  5035.9
Encroach Node=11098.0
       1    4584  5035.9
Encroach Node=11055.7
       1    4600  5053.8
Encroach Node=11012.7
       1    4600  5053.8
Encroach Node=10820.4
       1    4700 5061.13
Encroach Node=10799.4
       1    4700 5061.13
Encroach Node=10716.6
       1    4956  5019.4
Encroach Node=10031.4
       1    4960  5019.4
Encroach Node=9741.3
       1  4932.9  5067.4
Encroach Node=9615.9
       1  4932.9  5067.4
Encroach Node=9217.3
       1  4932.9  5067.4
Encroach Node=8841.0
       1 4952.28 5065.08
Encroach Node=8317.5
       1 4952.28 5064.98
Encroach Node=8227.6
       1 4952.28 5065.08
Encroach Node=8149.1
       1 4952.28 5065.08
Encroach Node=8128.1
       1 4952.28 5065.08
Encroach Node=8116.6
       1  4952.3  5065.1
Encroach Node=8005.0
       1  4952.3  5065.1
Encroach Node=7718.0
       1  4961.1  5040.6
Encroach Node=7023.5
       1  4961.1  5040.6
Encroach Node=6254.5
       1  4978.7  5037.5
Encroach Node=5559.2
       1  4978.7  5037.5
Encroach Node=4816.6
       1  4905.1  5075.2
Encroach Node=4148.6
       1  4934.2  5089.9
Encroach Node=3395.5
       1  4952.6  5026.8
Encroach Node=2880.4
       1    4896  5087.3
Encroach Node=2728.4
       1  4949.8  5069.4
Encroach Node=2692.4
       1  4949.8  5069.4
Encroach Node=2620.7
       1  4954.6  5024.1
Encroach Node=2448.5
       1  4954.6  5024.1
Encroach Node=2252.3
       1 4981.56  5026.1
Encroach Node=1697.6
       1  4975.8  5026.1
Encroach Node=883.9
       1  4984.5 5025.82
BEGIN DESCRIPTION:
FEMA Effective Risk Map Study Floodway May 02, 2019
END DESCRIPTION:
Computation Interval=1HOUR
Output Interval=1HOUR
Run HTab= 0
Run UNet= 0
Run PostProcess= 0
Run WQNet= 0
UNET Theta= 1
UNET Theta Warmup= 1
UNET ZTol= 0.02
UNET ZSATol= 0.1
UNET MxIter= 20
UNET MaxInSteps= 20
UNET DtIC= 0
UNET DtMin= 0
UNET MaxCRTS= 20
UNET WFStab= 2
UNET SFStab= 1
UNET WFX= 1
UNET SFX= 1
UNET DSS MLevel= 4
UNET DZMax Abort= 100
UNET Convert EG Bridges=-1
UNET Use Existing IB Tables=-1
UNET Froude Reduction=False
UNET Froude Limit= 1
UNET Froude Power= 10
UNET Time Slicing=0,0, 5
UNET Junction Losses=0
Instantaneous Interval=1HOUR
Write IC File= 0
IC Time=0,,
Write IC File at Sim End=0
Echo Input=False
Echo Parameters=False
Echo Output=False
Write Detailed= 0
WQ AD Non Conservative
WQ ULTIMATE=-1
WQ Max Comp Step=1HOUR
WQ Output Interval=15MIN
WQ Output Selected Increments= 0
WQ Output face flow=0
WQ Output face velocity=0
WQ Output face area=0
WQ Output face dispersion=0
WQ Output cell volume=0
WQ Output cell surface area=0
WQ Output cell continuity=0
WQ Output cumulative cell continuity=0
WQ Output face conc=0
WQ Output face dconc_dx=0
WQ Output face courant=0
WQ Output face peclet=0
WQ Output face adv mass=0
WQ Output face disp mass=0
WQ Output cell mass=0
WQ Output cell source sink temp=0
WQ Output cell source sink nsm=0
WQ Output MaxMinRange=-1
WQ Daily Max Min Mean=-1
WQ Daily Range=0
WQ Daily Time=0
WQ Create Restart=0
WQ Fixed Restart=0
WQ System Summary=0
WQ Use Fixed Temperature=0
Sorting and Armoring Iterations= 10
XS Update Threshold= 0.02
Hydraulics Update Threshold= 0.02
Energy Slope Method= 1
Volume Change Method= 0
XS Weighting Method= 0
Number of US Weighted Cross Sections= 1
Number of DS Weighted Cross Sections= 1
Upstream XS Weight=0.25
Main XS Weight=0.5
Downstream XS Weight=0.25
Number of DS XS's Weighted with US Boundary= 1
Upstream Boundary Weight= 1
Weight of XSs Associated with US Boundary= 0
Number of US XS's Weighted with DS Boundary= 1
Downstream Boundary Weight= 0.5
Weight of XSs Associated with DS Boundary= 0.5
Sediment Output Level= 4
Mass or Volume Output= 0
Output Increment Type= 1
Profile and TS Output Increment= 10
XS Output Flag= 0
XS Output Increment= 10
Disregard all LS=0
Disregard all Conn=0
Disregard all Breaches=0
Disregard all Pumps=0

--- C106-01-00.p01 (plan) ---

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Plan Title=Effective Multi-Profile 2015
Short Identifier=RiskMAP MP
Geom File=g01
Flow File=f01
Encroach Param=-1 ,0,0, 0
FEMA Effective Risk Map Study Multi-Profile May 02, 2019
UNET ZSATol= 0.05
UNET MaxInSteps= 0

--- C106-01-00.f02 (steady flow) ---

Flow Title=Effective Floodway 2015
Program Version=4.10
Number of Profiles= 2
Profile Names=1PCT_100yr,Floodway
River Rch & RM=C106-01-00,C106-01-00_0009 ,25157.3
     886     886
River Rch & RM=C106-01-00,C106-01-00_0009 ,20941
    1848    1848
River Rch & RM=C106-01-00,C106-01-00_0009 ,15938
    2135    2135
River Rch & RM=C106-01-00,C106-01-00_0009 ,14358.4
    2234    2234
River Rch & RM=C106-01-00,C106-01-00_0009 ,10820.4
    2474    2474
River Rch & RM=C106-01-00,C106-01-00_0009 ,10716.6
    2482    2482
River Rch & RM=C106-01-00,C106-01-00_0009 ,10031.4
    2531    2531
River Rch & RM=C106-01-00,C106-01-00_0009 ,8841
    2620    2620
River Rch & RM=C106-01-00,C106-01-00_0009 ,7718
    2706    2706
River Rch & RM=C106-01-00,C106-01-00_0009 ,2728.4
    3125    3125
Boundary for River Rch & Prof#=C106-01-00,C106-01-00_0009 , 1
Up Type= 0
Dn Type= 3
Dn Slope=0.0069
Boundary for River Rch & Prof#=C106-01-00,C106-01-00_0009 , 2
Up Type= 0
Dn Type= 3
Dn Slope=0.0069
DSS Import GetInterval= 0
DSS Import GetPeak= 0
DSS Import FillOption= 0

--- C106-01-00.f01 (steady flow) ---

Flow Title=Effective Multi-Profile 2015
Program Version=4.10
Number of Profiles= 6
Profile Names=10PCT_10yr,4PCT_25yr,2PCT_50yr,1PCT_100yr,1PCT_Plus,0.2PCT_500yr
River Rch & RM=C106-01-00,C106-01-00_0009 ,25157.3
     498     630     752     886    1063    1281
River Rch & RM=C106-01-00,C106-01-00_0009 ,20941
    1042    1315    1570    1848    2217    2675
River Rch & RM=C106-01-00,C106-01-00_0009 ,15938
    1212    1523    1812    2135    2562    3094
River Rch & RM=C106-01-00,C106-01-00_0009 ,14358.4
    1271    1596    1895    2234    2681    3240
River Rch & RM=C106-01-00,C106-01-00_0009 ,10820.4
    1415    1770    2098    2474    2969    3591
River Rch & RM=C106-01-00,C106-01-00_0009 ,10716.6
    1419    1776    2104    2482    2978    3602
River Rch & RM=C106-01-00,C106-01-00_0009 ,10031.4
    1449    1812    2146    2531    3038    3675
River Rch & RM=C106-01-00,C106-01-00_0009 ,8841
    1502    1876    2220    2620    3144    3804
River Rch & RM=C106-01-00,C106-01-00_0009 ,7718
    1554    1939    2293    2706    3247    3931
River Rch & RM=C106-01-00,C106-01-00_0009 ,2728.4
    1807    2245    2645    3125    3750    4545
Boundary for River Rch & Prof#=C106-01-00,C106-01-00_0009 , 1
Up Type= 0
Dn Type= 3
Dn Slope=0.0069
Boundary for River Rch & Prof#=C106-01-00,C106-01-00_0009 , 2
Up Type= 0
Dn Type= 3
Dn Slope=0.0069
Boundary for River Rch & Prof#=C106-01-00,C106-01-00_0009 , 3
Up Type= 0
Dn Type= 3
Dn Slope=0.0069
Boundary for River Rch & Prof#=C106-01-00,C106-01-00_0009 , 4
Up Type= 0
Dn Type= 3
Dn Slope=0.0069
DSS Import GetInterval= 0
DSS Import GetPeak= 0
DSS Import FillOption= 0

--- C106-01-00.g01 (geometry) ---

Geom Title=C106-01-00 2015
Program Version=4.10

River Reach=C106-01-00      ,C106-01-00_0009
Reach XY= 30
      3152835.25     13797557.57      3153574.58     13797495.99
      3154167.85     13797086.34      3155646.75     13797161.91
      3155103.75       13806849.       3155751.1     13806895.31
       3155987.5       13807042.      3155711.81     13808197.45
        3155556.       13808565.       3155883.5       13809589.
      3156014.25     13809819.83      3156113.36     13809850.81
      3156101.79      13810059.4      3156271.93      13810304.1
      3156226.05     13810676.87      3156728.81     13811080.23
      3156742.19     13811309.63      3157265.99     13811881.21
      3157327.16     13812431.77      3157489.11     13812921.52
       3157629.2     13813085.56      3157543.96     13813489.35
      3157738.17     13814096.83      3157837.57     13814198.14
      3157831.84     13814643.56      3158353.96     13815237.42
       3158978.7     13815344.25      3159123.95     13815533.56
      3159410.98     13815538.12      3159492.99     13815601.91

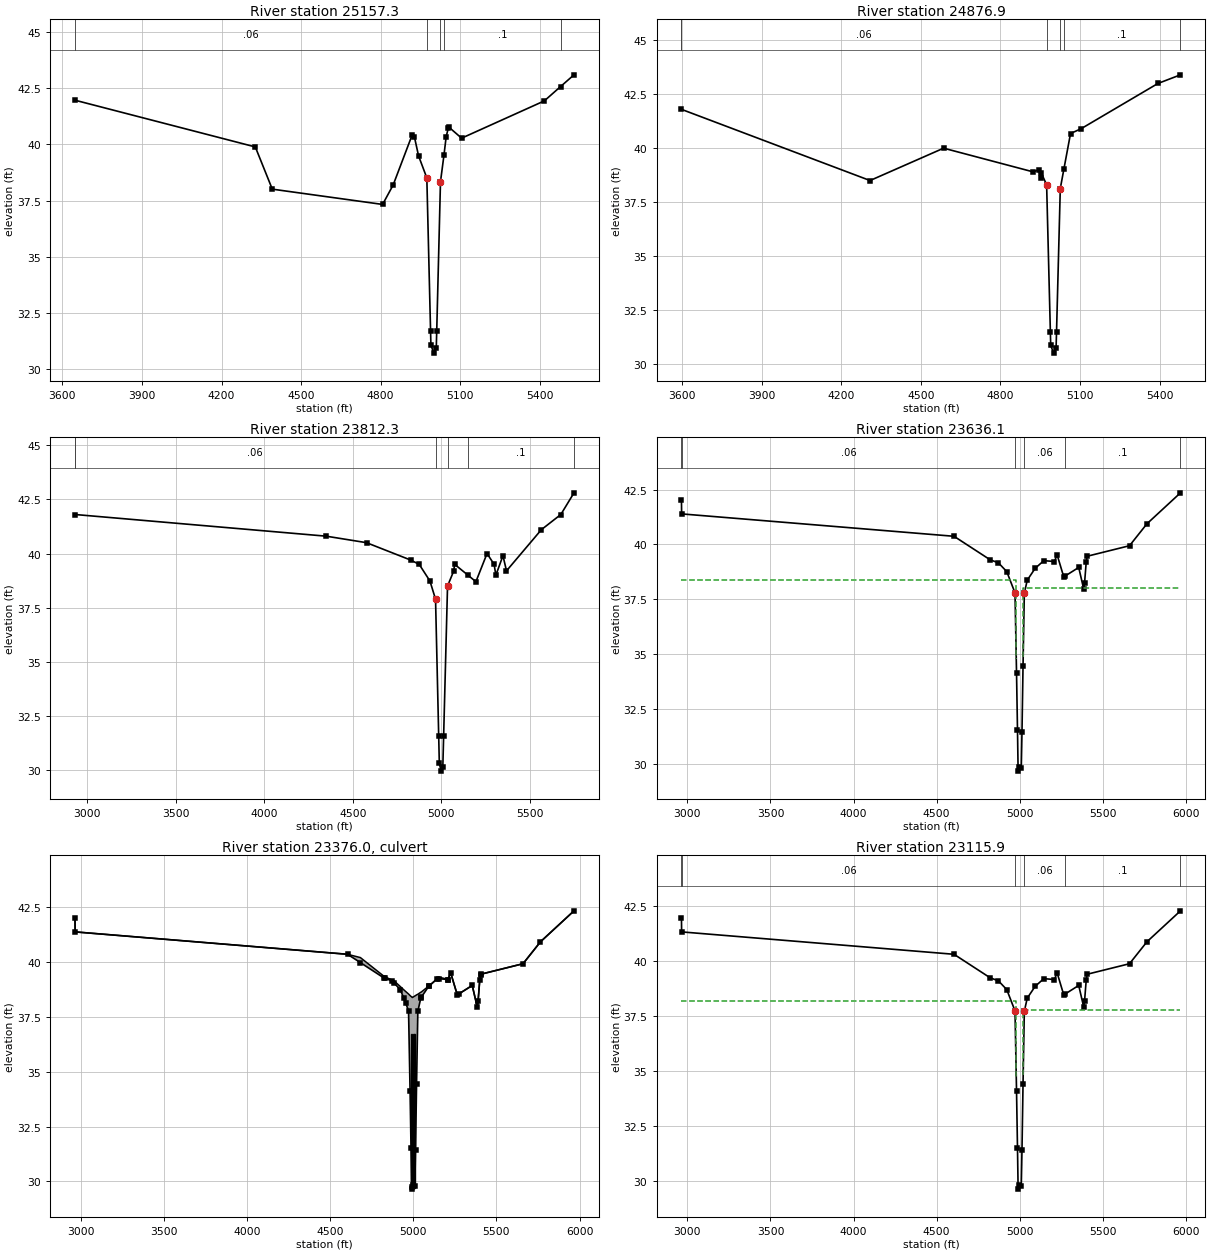
Type RM Length L Ch R = 1 ,25157.3 ,328.2,280.4,258.6
BEGIN DESCRIPTION:
Cross Section 25157.3-Interpolated
END DESCRIPTION:
XS GIS Cut Line= 4
      3152572.87     13798875.45      3152786.13     13797621.72
      3152870.15     13797511.86      3152870.15      13797040.1
#Sta/Elev= 23
  3647.5   41.97  4327.5   39.89  4391.5   38.01  4807.5   37.33  4847.5    38.2
  4919.2   40.43  4927.2   40.35  4943.2   39.49  4974.3   38.51  4988.4   31.69
  4989.7   31.07  5000.6   30.71  5009.9   30.95  5011.6   31.68  5025.8   38.34
  5039.2   39.55  5047.2   40.34  5055.2   40.73  5057.5   40.77  5105.5   40.28
  5417.5   41.94  5478.9   42.58  5529.3    43.1
#Mann= 5 , 1 , 0
  3647.5     .06       0  4974.3    .015       0  5025.8     .06       0
  5039.2      .1       0  5478.9      .2       0
#XS Ineff= 2 , 0
       0  4919.2   40.43               0
Permanent Ineff=
       F       F
Bank Sta=4974.3,5025.8
XS Rating Curve= 0 ,0
Exp/Cntr=0.3,0.1

Type RM Length L Ch R = 1 ,24876.9 ,1186.5,1064.6,988.9
BEGIN DESCRIPTION:
Cross Section 24876.9
END DESCRIPTION:
XS GIS Cut Line= 5
      3152651.14     13798796.42      3153053.02     13798209.82
       3153086.2      13798035.6      3153119.16     13797598.69
      3153024.88     13797051.88
#Sta/Elev= 19
  3597.5    41.8  4308.5    38.5  4585.9      40    4924    38.9    4944      39
    4954    38.6  4954.2   38.85  4974.3    38.3  4988.4   31.48  4989.7   30.86
  5000.6    30.5  5009.9   30.74  5011.6   31.47  5025.8   38.13  5039.2   39.02
  5064.4   40.68    5104    40.9    5394      43  5478.9    43.4
#Mann= 6 , 1 , 0
  3597.5      .2       0  3597.5     .06       0  4974.3    .015       0
  5025.8     .06       0  5039.2      .1       0  5478.9      .2       0
#XS Ineff= 2 , 0
       0  4585.9      40               0
Permanent Ineff=
       F       F
Bank Sta=4974.3,5025.8
XS Rating Curve= 0 ,0
Exp/Cntr=0.3,0.1

Type RM Length L Ch R = 1 ,23812.3 ,104.2,176.2,302.5
BEGIN DESCRIPTION:
Cross Section 23812.3
END DESCRIPTION:
XS GIS Cut Line= 6
      3152781.67     13798640.17      3153853.92     13797709.81
      3154124.23     13797320.44      3153876.44      13796992.2
        3153619.     13796824.87      3153435.58     13796805.56
#Sta/Elev= 25
  2930.5    41.8  4350.1    40.8    4578    40.5  4827.1    39.7  4875.8    39.5
  4936.6   38.73  4968.2   37.89  4986.1   31.56  4989.5   30.32  4999.8   29.96
  5009.4   30.17  5013.9   31.57    5036    38.5  5070.3   39.18  5076.3    39.5
  5153.1   38.99  5196.3    38.7  5259.2      40  5299.2    39.5  5309.2      39
  5349.2    39.9  5369.2    39.2  5566.3    41.1  5676.3    41.8  5750.7    42.8
#Mann= 6 , 1 , 0
  2930.5      .2       0  2930.5     .06       0  4968.2    .015       0
    5036     .06       0  5153.1      .1       0  5750.7      .2       0
#XS Ineff= 2 , 0
       0                    5289       0    39.6
Permanent Ineff=
       F       F
Bank Sta=4968.2,5036
XS Rating Curve= 0 ,0
Exp/Cntr=0.5,0.3

Type RM Length L Ch R = 1 ,23636.1 ,520.2,520.2,520.2
BEGIN DESCRIPTION:
Upstream Section of Bridge/Culvert/Weir
END DESCRIPTION:
XS GIS Cut Line= 6
      3152771.83     13798484.93      3153667.56      13797700.9
      3153896.41     13797513.87      3154158.26     13797276.22
      3154215.14     13797088.93      3154043.02     13796137.48
#Sta/Elev= 30
  2964.7   42.02  2965.7   41.39  4604.5   40.37  4821.7    39.3  4871.6   39.16
  4921.9   38.76  4971.5   37.79  4980.6   34.15  4986.4   31.54  4990.2   29.67
    4997   29.86  5009.1   29.81  5013.5   31.47  5019.7   34.46  5027.4   37.77
    5045   38.37  5092.7   38.91  5144.9   39.26  5208.7   39.22  5224.7   39.53
  5264.7   38.52  5273.1   38.56  5354.7   38.95  5384.7   37.97  5389.7   38.22
  5399.7   39.18  5405.3   39.46  5660.3   39.94  5765.3   40.94  5966.9   42.35
#Mann= 6 , 1 , 0
  2964.7      .2       0  2965.7     .06       0  4971.5    .015       0
  5027.4     .06       0  5273.1      .1       0  5966.9      .2       0
#XS Ineff= 2 , 0
       0    4979    38.4  5020.7       0      38
Permanent Ineff=
       F       F
Bank Sta=4971.5,5027.4
XS Rating Curve= 0 ,0
Exp/Cntr=0.5,0.3

Type RM Length L Ch R = 2 ,23376.0 ,,,
BEGIN DESCRIPTION:
HOBBY AIRPORT RUNWAY
Structure ID: C61-15
END DESCRIPTION:
Bridge Culvert--1,0,-1,-1, 0
Deck Dist Width WeirC Skew NumUp NumDn MinLoCord MaxHiCord MaxSubmerge Is_Ogee
10,500.2,3,0, 41, 41, , , 0.95, 0, 1,1,,
  2964.7  2965.7  4604.5  4681.8  4821.7  4827.1  4871.6  4884.2  4921.9  4941.6
  4953.4  4971.5  4980.6  4986.4  4990.2    4994    4997  5009.1  5013.5  5019.7
  5027.4    5045  5048.1  5092.7  5092.9  5144.9    5152  5208.6  5208.7  5224.7
  5264.7  5273.1  5354.7  5384.7  5389.7  5399.7  5404.7  5405.3  5660.3  5765.3
  5966.9
      42   41.37   40.35    40.2   39.36   39.33   39.18   39.14   38.88   38.74
   38.66   38.54   38.47   38.43   38.41   38.38   38.39   38.45   38.47    38.5
   38.53   38.62   38.63    38.9    38.9   39.24   39.31   39.21   39.21   39.51
    38.5   38.54   38.93   37.95    38.2   39.16   39.42   39.44   39.92   40.92
   42.33
      42   41.37   40.35   39.97   39.28   39.26   39.14   39.04   38.74   38.37
   38.15   37.77   34.13   31.52   29.65   29.76   29.84   29.79   31.45   34.44
   37.75   38.35   38.39   38.89   38.89   39.24   39.24    39.2    39.2   39.51
    38.5   38.54   38.93   37.95    38.2   39.16   39.42   39.44   39.92   40.92
   42.33
  2964.7  2965.7  4604.5  4681.8  4821.7  4827.1  4871.6  4884.2  4921.9  4941.6
  4953.4  4971.5  4980.6  4986.4  4990.2    4994    4997  5009.1  5013.5  5019.7
  5027.4    5045  5048.1  5092.7  5092.9  5144.9    5152  5208.6  5208.7  5224.7
  5264.7  5273.1  5354.7  5384.7  5389.7  5399.7  5404.7  5405.3  5660.3  5765.3
  5966.9
      42   41.37   40.35    40.2   39.36   39.33   39.18   39.14   38.88   38.74
   38.66   38.54   38.47   38.43   38.41   38.38   38.39   38.45   38.47    38.5
   38.53   38.62   38.63    38.9    38.9   39.24   39.31   39.21   39.21   39.51
    38.5   38.54   38.93   37.95    38.2   39.16   39.42   39.44   39.92   40.92
   42.33
   41.97   41.34   40.32   39.94   39.25   39.23   39.11   39.01   38.71   38.34
   38.12   37.74    34.1   31.49   29.62   29.73   29.81   29.76   31.42   34.41
   37.72   38.32   38.36   38.86   38.86   39.21   39.21   39.17   39.17   39.48
   38.47   38.51    38.9   37.92   38.17   39.13   39.39   39.41   39.89   40.89
    42.3
BR Coef= 1 , 0 , 0 ,1.25, 0 ,,,0.8,-1,2,0,
WSPro=,,,, 1 ,,,, 0 ,,,, 0 ,,,,-1 ,-1 ,-1 , 0 , 0 , 0 , 0 , 0
Culvert=2,7,6,500.2,0.015,0.4,1,8,1,29.72,4992.1,29.64,4992.1,Culvert #1  , 0 ,10
Culvert Bottom n=0.015
Culvert=2,7,6,500.2,0.015,0.4,1,8,1,29.72,4999.8,29.64,4999.8,Culvert #2  , 0 ,10
Culvert Bottom n=0.015
Culvert=2,7,6,500.2,0.015,0.4,1,8,1,29.72,5007.6,29.64,5007.6,Culvert #3  , 0 ,10
Culvert Bottom n=0.015
BR U #Sta/Elev= 41
  2964.7      42  2965.7   41.37  4604.5   40.35  4681.8   39.97  4821.7   39.28
  4827.1   39.26  4871.6   39.14  4884.2   39.04  4921.9   38.74  4941.6   38.37
  4953.4   38.15  4971.5   37.77  4980.6   34.13  4986.4   31.52  4990.2   29.65
    4994   29.76    4997   29.84  5009.1   29.79  5013.5   31.45  5019.7   34.44
  5027.4   37.75    5045   38.35  5048.1   38.39  5092.7   38.89  5092.9   38.89
  5144.9   39.24    5152   39.24  5208.6    39.2  5208.7    39.2  5224.7   39.51
  5264.7    38.5  5273.1   38.54  5354.7   38.93  5384.7   37.95  5389.7    38.2
  5399.7   39.16  5404.7   39.42  5405.3   39.44  5660.3   39.92  5765.3   40.92
  5966.9   42.33
BR U #Mann= 6
  2964.7      .2  2965.7     .06  4971.5    .015  5027.4     .06  5273.1      .1
  5966.9      .2
BR U Banks=4971.5,5027.4
BR D #Sta/Elev= 41
  2964.7   41.97  2965.7   41.34  4604.5   40.32  4681.8   39.94  4821.7   39.25
  4827.1   39.23  4871.6   39.11  4884.2   39.01  4921.9   38.71  4941.6   38.34
  4953.4   38.12  4971.5   37.74  4980.6    34.1  4986.4   31.49  4990.2   29.62
    4994   29.73    4997   29.81  5009.1   29.76  5013.5   31.42  5019.7   34.41
  5027.4   37.72    5045   38.32  5048.1   38.36  5092.7   38.86  5092.9   38.86
  5144.9   39.21    5152   39.21  5208.6   39.17  5208.7   39.17  5224.7   39.48
  5264.7   38.47  5273.1   38.51  5354.7    38.9  5384.7   37.92  5389.7   38.17
  5399.7   39.13  5404.7   39.39  5405.3   39.41  5660.3   39.89  5765.3   40.89
  5966.9    42.3
BR D #Mann= 6
  2964.7      .2  2965.7     .06  4971.5    .015  5027.4     .06  5273.1      .1
  5966.9      .2
BR D Banks=4971.5,5027.4
BC Design=,, 0 ,, 0 ,,,,,,
BC HTab HWMax=42.35
BC Use User HTab Curves=0
BC User HTab FreeFlow(D)= 0

Type RM Length L Ch R = 1 ,23115.9 ,84.2,88.4,95.5
BEGIN DESCRIPTION:
Downstream Section of Bridge/Culvert/Weir
END DESCRIPTION:
XS GIS Cut Line= 6
      3153291.24     13798513.44      3154186.98     13797729.42
      3154415.83     13797542.39      3154677.68     13797304.74
      3154734.56     13797117.45      3154562.43     13796165.99
#Sta/Elev= 30
  2964.7   41.97  2965.7   41.34  4604.5   40.32  4821.7   39.25  4871.6   39.11
  4921.9   38.71  4971.5   37.74  4980.6    34.1  4986.4   31.49  4990.2   29.62
    4997   29.81  5009.1   29.76  5013.5   31.42  5019.7   34.41  5027.4   37.72
    5045   38.32  5092.7   38.86  5144.9   39.21  5208.7   39.17  5224.7   39.48
  5264.7   38.47  5273.1   38.51  5354.7    38.9  5384.7   37.92  5389.7   38.17
  5399.7   39.13  5405.3   39.41  5660.3   39.89  5765.3   40.89  5966.9    42.3
#Mann= 6 , 1 , 0
  2964.7      .2       0  2965.7     .06       0  4971.5    .015       0
  5027.4     .06       0  5273.1      .1       0  5966.9      .2       0
#XS Ineff= 2 , 0
       0    4979    38.2  5020.7       0    37.8
Permanent Ineff=
       F       F
Bank Sta=4971.5,5027.4
XS Rating Curve= 0 ,0
Exp/Cntr=0.5,0.3

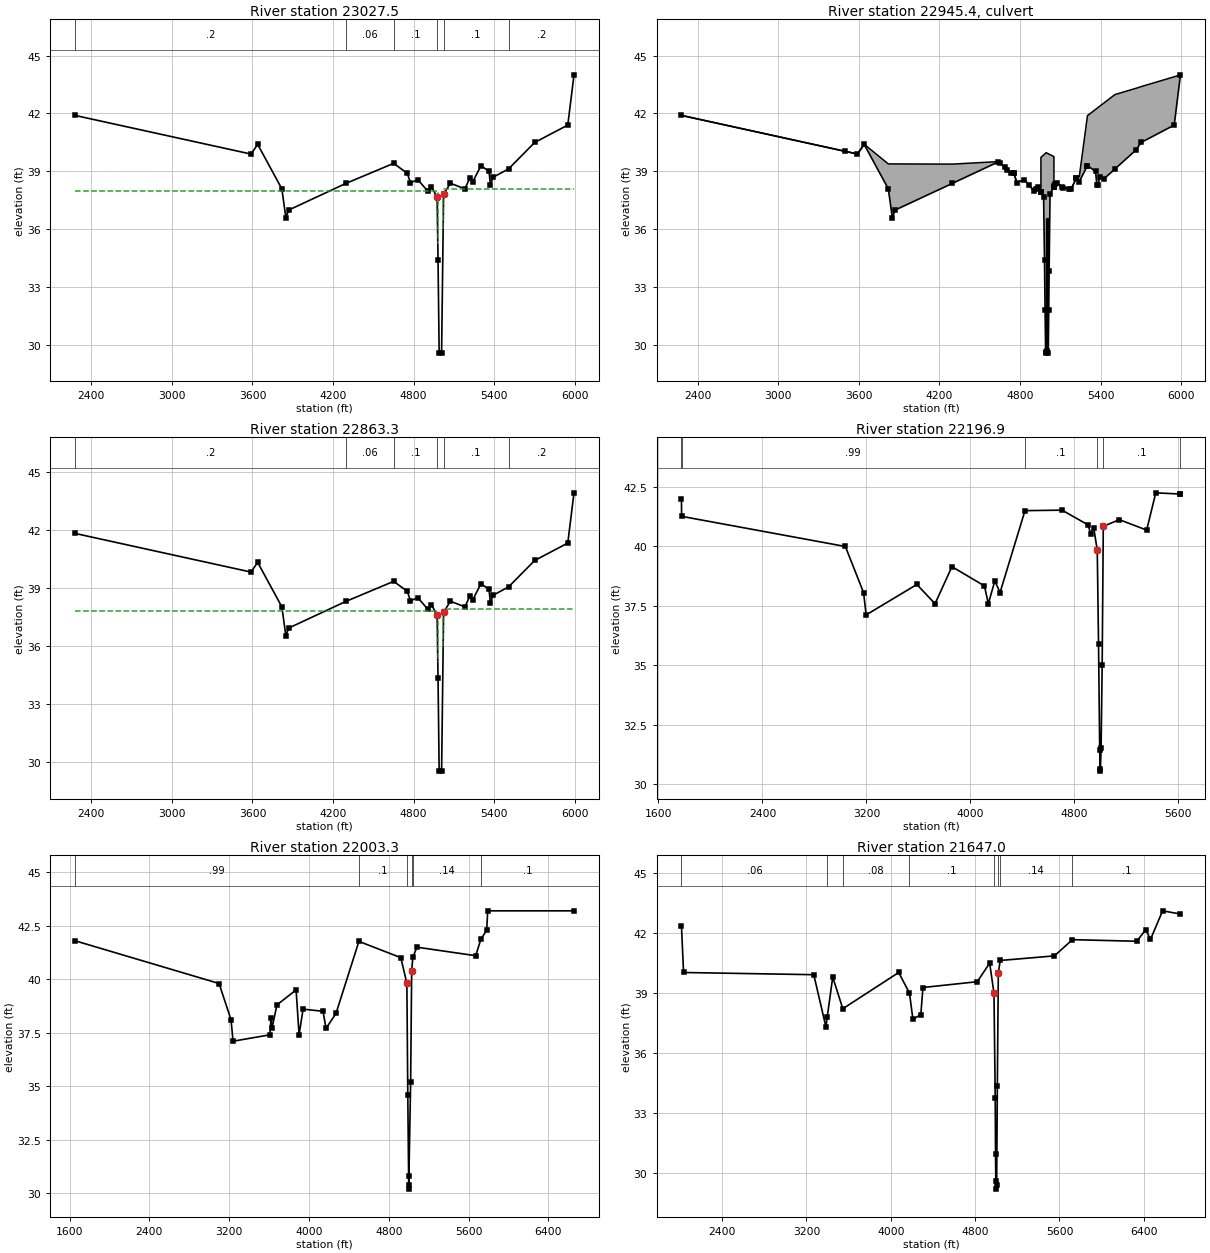
Type RM Length L Ch R = 1 ,23027.5 ,164.2,164.2,164.2
BEGIN DESCRIPTION:
Upstream Section of Bridge/Culvert/Weir
END DESCRIPTION:
XS GIS Cut Line= 6
      3152756.83      13798716.4      3153818.34     13798120.03
      3154678.79     13797500.26      3154824.22     13797366.14
       3154906.6     13797023.74      3155636.46     13796520.77
#Sta/Elev= 30
  2277.7    41.9  3588.8    39.9  3638.8    40.4  3818.8    38.1  3848.8    36.6
  3868.8      37  4295.3   38.38    4652   39.42  4753.5    38.9  4776.8   38.42
  4832.8   38.57  4906.7   37.97  4933.5   38.22  4975.6   37.66  4982.4    34.4
  4990.8    29.6  5008.9    29.6  5023.7   37.82  5074.5   38.39  5182.3    38.1
  5220.4   38.67  5241.4   38.47  5302.4    39.3  5362.5      39  5372.5    38.3
  5392.5    38.7  5507.4   39.13  5702.5    40.5  5948.9    41.4  5995.3      44
#Mann= 6 , 1 , 0
  2277.7      .2       0  4295.3     .06       0    4652      .1       0
  4975.6    .015       0  5023.7      .1       0  5507.4      .2       0
#XS Ineff= 2 , 0
       0  4980.6      38  5020.5       0    38.1
Permanent Ineff=
       F       F
Bank Sta=4975.6,5023.7
XS Rating Curve= 0 ,0
Exp/Cntr=0.5,0.3

Type RM Length L Ch R = 2 ,22945.4 ,,,
BEGIN DESCRIPTION:
MONROE STREET
Structure ID: C61-14
END DESCRIPTION:
Bridge Culvert--1,0,-1,-1, 0
Deck Dist Width WeirC Skew NumUp NumDn MinLoCord MaxHiCord MaxSubmerge Is_Ogee
10,144.2,3,0, 59, 59, , , 0.95, 0, 1,1,,
  2277.7  3495.3  3588.8  3638.8  3818.8  3848.8  3868.8  4295.3  4639.5    4652
  4685.3  4705.3    4734  4753.4  4753.5  4776.8  4832.8  4865.9  4906.7  4920.3
  4933.5 4955.59  4955.7 4955.81  4975.6  4982.4  4986.7  4990.8  4994.7  4998.5
  5008.9  5013.2  5016.7  5023.7 5052.49  5052.6 5052.71  5054.9  5064.2  5074.5
  5109.8    5123  5167.4  5182.3  5220.4  5220.5  5241.4  5302.4  5302.5  5362.5
  5372.5  5382.5  5392.5  5422.5  5507.4  5662.5  5702.5  5948.9  5995.3
    41.9   40.05   39.91   40.41   39.39   39.39   39.39   39.38   39.51   39.43
   39.22   39.09   38.91   38.91   38.91   38.43   38.58   38.31   37.98   38.11
   38.23   38.13   39.73   39.73   39.85   39.89   39.92   39.95   39.97   39.96
   39.92   39.91   39.89   39.87   39.77   39.77   38.22   38.25   38.38    38.4
   38.23   38.16   38.12   38.11   38.68   38.68   38.73   41.89   41.89   42.21
   42.26   42.32   42.37   42.53   42.98    43.3   43.39    43.9      44
    41.9   40.04    39.9    40.4    38.1    36.6      37   38.38    39.5   39.42
   39.21   39.08    38.9    38.9    38.9   38.42   38.57    38.3   37.97    38.1
   38.22   37.93   37.92   37.92   37.66    34.4   31.83    29.6   29.67   29.73
    29.6   31.84   33.87   37.82   38.21   38.21   38.21   38.24   38.37   38.39
   38.22   38.15   38.11    38.1   38.67   38.67   38.47    39.3    39.3      39
    38.3    38.3    38.7    38.6   39.13    40.1    40.5    41.4      44
  2277.7  3495.3  3588.8  3638.8  3818.8  3848.8  3868.8  4295.3  4639.5    4652
  4685.3  4705.3    4734  4753.4  4753.5  4776.8  4832.8  4865.9  4906.7  4920.3
  4933.5 4955.59  4955.7 4955.81  4975.6  4982.4  4986.7  4990.8  4994.7  4998.5
  5008.9  5013.2  5016.7  5023.7 5052.49  5052.6 5052.71  5054.9  5064.2  5074.5
  5109.8    5123  5167.4  5182.3  5220.4  5220.5  5241.4  5302.4  5302.5  5362.5
  5372.5  5382.5  5392.5  5422.5  5507.4  5662.5  5702.5  5948.9  5995.3
    41.9   40.05   39.91   40.41   39.39   39.39   39.39   39.38   39.51   39.43
   39.22   39.09   38.91   38.91   38.91   38.43   38.58   38.31   37.98   38.11
   38.23   38.13   39.73   39.73   39.85   39.89   39.92   39.95   39.97   39.96
   39.92   39.91   39.89   39.87   39.77   39.77   38.22   38.25   38.38    38.4
   38.23   38.16   38.12   38.11   38.68   38.68   38.73   41.89   41.89   42.21
   42.26   42.32   42.37   42.53   42.98    43.3   43.39    43.9      44
    41.8   39.94    39.8    40.3      38    36.5    36.9   38.28    39.4   39.32
   39.11   38.98    38.8    38.8    38.8   38.32   38.47    38.2   37.87      38
   38.12   37.83   37.82   37.82   37.56    34.3   31.73    29.5   29.57   29.63
    29.5   31.74   33.77   37.72   38.11   38.11   38.11   38.14   38.27   38.29
   38.12   38.05   38.01      38   38.57   38.57   38.37    39.2    39.2    38.9
    38.2    38.2    38.6    38.5   39.03      40    40.4    41.3    43.9
BR Coef= 1 , 0 , 0 ,1.25, 0 ,,,0.8,-1,2,0,
WSPro=,,,, 1 ,,,, 0 ,,,, 0 ,,,,-1 ,-1 ,-1 , 0 , 0 , 0 , 0 , 0
Culvert=2,7,6,144.2,0.015,0.4,1,8,1,29.6,4993.7,29.81,4993.7,Culvert #1  , 0 ,10
Culvert Bottom n=0.015
Culvert=2,7,6,144.2,0.015,0.4,1,8,1,29.6,5000.7,29.81,5000.7,Culvert #2  , 0 ,10
Culvert Bottom n=0.015
Culvert=2,7,6,144.2,0.015,0.4,1,8,1,29.6,5007.4,29.81,5007.4,Culvert #3  , 0 ,10
Culvert Bottom n=0.015
BR U #Sta/Elev= 59
  2277.7    41.9  3495.3   40.04  3588.8    39.9  3638.8    40.4  3818.8    38.1
  3848.8    36.6  3868.8      37  4295.3   38.38  4639.5    39.5    4652   39.42
  4685.3   39.21  4705.3   39.08    4734    38.9  4753.4    38.9  4753.5    38.9
  4776.8   38.42  4832.8   38.57  4865.9    38.3  4906.7   37.97  4920.3    38.1
  4933.5   38.22 4955.59   37.93  4955.7   37.92 4955.81   37.92  4975.6   37.66
  4982.4    34.4  4986.7   31.83  4990.8    29.6  4994.7   29.67  4998.5   29.73
  5008.9    29.6  5013.2   31.84  5016.7   33.87  5023.7   37.82 5052.49   38.21
  5052.6   38.21 5052.71   38.21  5054.9   38.24  5064.2   38.37  5074.5   38.39
  5109.8   38.22    5123   38.15  5167.4   38.11  5182.3    38.1  5220.4   38.67
  5220.5   38.67  5241.4   38.47  5302.4    39.3  5302.5    39.3  5362.5      39
  5372.5    38.3  5382.5    38.3  5392.5    38.7  5422.5    38.6  5507.4   39.13
  5662.5    40.1  5702.5    40.5  5948.9    41.4  5995.3      44
BR U #Mann= 6
  2277.7      .2  4295.3     .06    4652      .1  4975.6    .015  5023.7      .1
  5507.4      .2
BR U Banks=4975.6,5023.7
BR D #Sta/Elev= 59
  2277.7    41.8  3495.3   39.94  3588.8    39.8  3638.8    40.3  3818.8      38
  3848.8    36.5  3868.8    36.9  4295.3   38.28  4639.5    39.4    4652   39.32
  4685.3   39.11  4705.3   38.98    4734    38.8  4753.4    38.8  4753.5    38.8
  4776.8   38.32  4832.8   38.47  4865.9    38.2  4906.7   37.87  4920.3      38
  4933.5   38.12 4955.59   37.83  4955.7   37.82 4955.81   37.82  4975.6   37.56
  4982.4    34.3  4986.7   31.73  4990.8    29.5  4994.7   29.57  4998.5   29.63
  5008.9    29.5  5013.2   31.74  5016.7   33.77  5023.7   37.72 5052.49   38.11
  5052.6   38.11 5052.71   38.11  5054.9   38.14  5064.2   38.27  5074.5   38.29
  5109.8   38.12    5123   38.05  5167.4   38.01  5182.3      38  5220.4   38.57
  5220.5   38.57  5241.4   38.37  5302.4    39.2  5302.5    39.2  5362.5    38.9
  5372.5    38.2  5382.5    38.2  5392.5    38.6  5422.5    38.5  5507.4   39.03
  5662.5      40  5702.5    40.4  5948.9    41.3  5995.3    43.9
BR D #Mann= 6
  2277.7      .2  4295.3     .06    4652      .1  4975.6    .015  5023.7      .1
  5507.4      .2
BR D Banks=4975.6,5023.7
BC Design=,, 0 ,, 0 ,,,,,,
BC HTab HWMax=44
BC Use User HTab Curves=0
BC User HTab FreeFlow(D)= 0

Type RM Length L Ch R = 1 ,22863.3 ,650.1,666.4,710.2
BEGIN DESCRIPTION:
Downstream Section of Bridge/Culvert/Weir
END DESCRIPTION:
XS GIS Cut Line= 6
      3152920.79      13798725.4       3153982.3     13798129.03
      3154842.75     13797509.26      3154988.18     13797375.14
      3155070.56     13797032.74      3155800.41     13796529.77
#Sta/Elev= 30
  2277.7   41.82  3588.8   39.82  3638.8   40.32  3818.8   38.02  3848.8   36.52
  3868.8   36.92  4295.3    38.3    4652   39.34  4753.5   38.82  4776.8   38.34
  4832.8   38.49  4906.7   37.89  4933.5   38.14  4975.6   37.58  4982.4   34.32
  4990.8   29.52  5008.9   29.52  5023.7   37.74  5074.5   38.31  5182.3   38.02
  5220.4   38.59  5241.4   38.39  5302.4   39.22  5362.5   38.92  5372.5   38.22
  5392.5   38.62  5507.4   39.05  5702.5   40.42  5948.9   41.32  5995.3   43.92
#Mann= 6 , 1 , 0
  2277.7      .2       0  4295.3     .06       0    4652      .1       0
  4975.6    .015       0  5023.7      .1       0  5507.4      .2       0
#XS Ineff= 2 , 0
       0  4980.6    37.8  5020.5       0    37.9
Permanent Ineff=
       F       F
Bank Sta=4975.6,5023.7
XS Rating Curve= 0 ,0
Exp/Cntr=0.5,0.3

Type RM Length L Ch R = 1 ,22196.9 ,39.6,193.6,235.9
BEGIN DESCRIPTION:
Cross Section 22196.9-Interpolated
END DESCRIPTION:
XS GIS Cut Line= 6
      3152863.86       13798724.      3153947.12     13798141.43
      3155110.18     13797322.97      3155384.31     13797299.48
      3155779.22     13797106.42      3156173.08     13796849.89
#Sta/Elev= 30
  1776.8      42  1777.8   41.27  3037.8      40  3177.8   38.06  3197.8   37.12
  3587.8    38.4  3727.8   37.59  3857.8   39.15  4107.8   38.34  4137.8   37.59
  4187.8   38.55  4227.8   38.06  4419.8   41.51  4705.1   41.53  4905.1   40.91
 4925.22   40.54 4948.42   40.79 4975.82   39.85 4985.72    35.9 4994.72   31.41
 4997.22   30.62 4999.52   30.54 5005.32    31.5 5013.62   35.01 5022.22   40.85
    5146   41.13    5356   40.69    5426   42.26  5611.8   42.21    5616   42.21
#Mann= 6 , 1 , 0
  1776.8      .2       0  1777.8     .99       0  4419.8      .1       0
 4975.82     .04       0 5022.22      .1       0  5611.8     .14       0
Bank Sta=4975.82,5022.22
XS Rating Curve= 0 ,0
Exp/Cntr=0.3,0.1

Type RM Length L Ch R = 1 ,22003.3 ,364.8,356.3,296.4
BEGIN DESCRIPTION:
Cross Section 22003.3
END DESCRIPTION:
XS GIS Cut Line= 6
      3152713.62     13798824.88      3153940.72     13798184.93
      3154587.84     13797728.63      3155141.14     13797347.79
      3155719.44     13797361.72      3157294.09     13797340.82
#Sta/Elev= 30
  1654.9    41.8  3098.8    39.8  3218.8    38.1  3238.8    37.1  3608.8    37.4
  3618.8    38.2  3628.8    37.7  3678.8    38.8  3870.6    39.5  3900.6    37.4
  3940.6    38.6  4140.6    38.5  4170.6    37.7  4270.6    38.4    4500   41.77
  4919.8   41.01  4980.8   39.81  4989.9    34.6  4999.1   30.37  5001.1   30.18
  5001.2   30.78  5018.5   35.17  5028.9    40.4  5040.9   41.02  5080.8    41.5
  5670.8    41.1  5721.5   41.86  5780.8    42.3  5790.8    43.2  6655.6    43.2
#Mann= 6 , 1 , 0
  1654.9     .99       0    4500      .1       0  4980.8     .04       0
  5028.9      .1       0  5040.9     .14       0  5721.5      .1       0
Bank Sta=4980.8,5028.9
XS Rating Curve= 0 ,0
Exp/Cntr=0.5,0.3

Type RM Length L Ch R = 1 ,21647.0 ,22,22,22
BEGIN DESCRIPTION:
Upstream Section of Bridge/Culvert/Weir
END DESCRIPTION:
XS GIS Cut Line= 6
      3152871.57     13798808.19      3154735.43     13797910.15
      3155447.01     13797709.23      3155781.87     13797709.23
      3156819.94     13797642.26      3157311.68     13797396.39
#Sta/Elev= 30
  2014.4   42.33  2034.4   40.01  3269.4    39.9  3384.4    37.3  3396.6   37.77
  3449.4   39.78  3544.8    38.2  4074.9   40.01  4177.4   38.98  4209.9   37.67
  4284.9   37.91  4304.9   39.26  4820.1   39.55 4937.97   40.48 4978.77   38.97
 4990.57   33.73 4993.47   30.95 4995.97   29.59 4999.87   29.19 5004.07   29.38
 5010.67   34.36 5019.87   39.98  5037.7   40.61  5551.8   40.84  5722.8   41.65
  6333.1   41.57  6418.1   42.15  6463.1   41.66  6578.1   43.09  6747.6   42.93
#Mann= 8 , 1 , 0
  2014.4     .06       0  3396.6      .1       0  3544.8     .08       0
  4177.4      .1       0 4978.77     .04       0 5019.87      .1       0
  5037.7     .14       0  5722.8      .1       0
#XS Ineff= 2 , 0
       0    4938    39.3  5013.4       0      36
Permanent Ineff=
       F       F
Bank Sta=4978.77,5019.87
XS Rating Curve= 0 ,0
Exp/Cntr=0.5,0.3