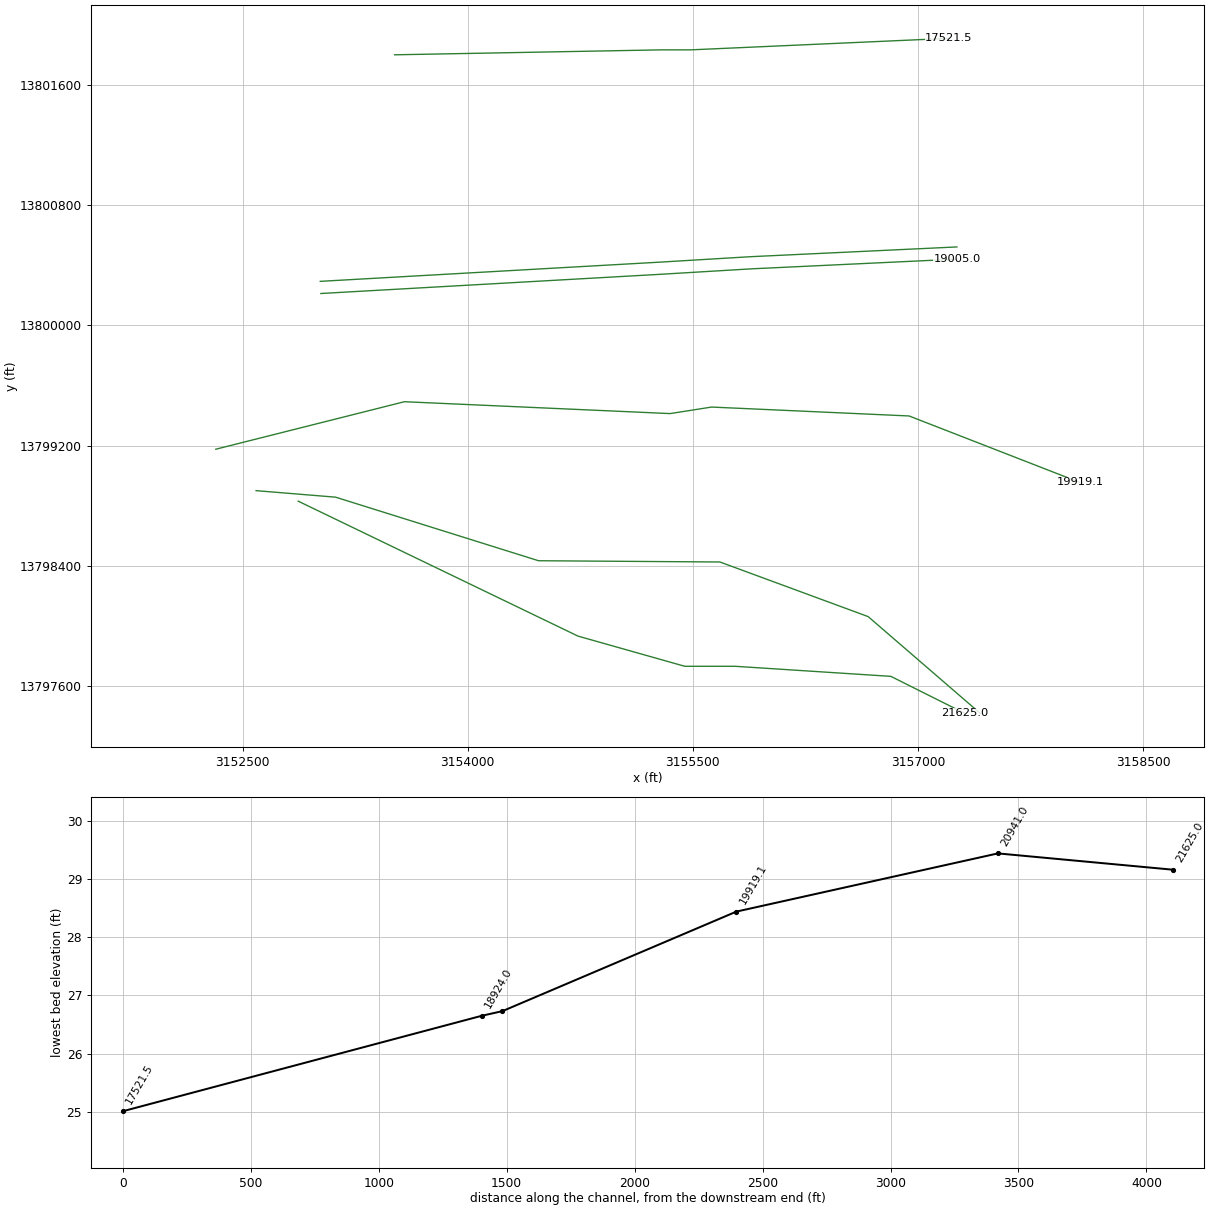
HEC-RAS study C106-01-00.PRJ: C106-01-00

--- C106-01-00.g01 (geometry) --- (continued)

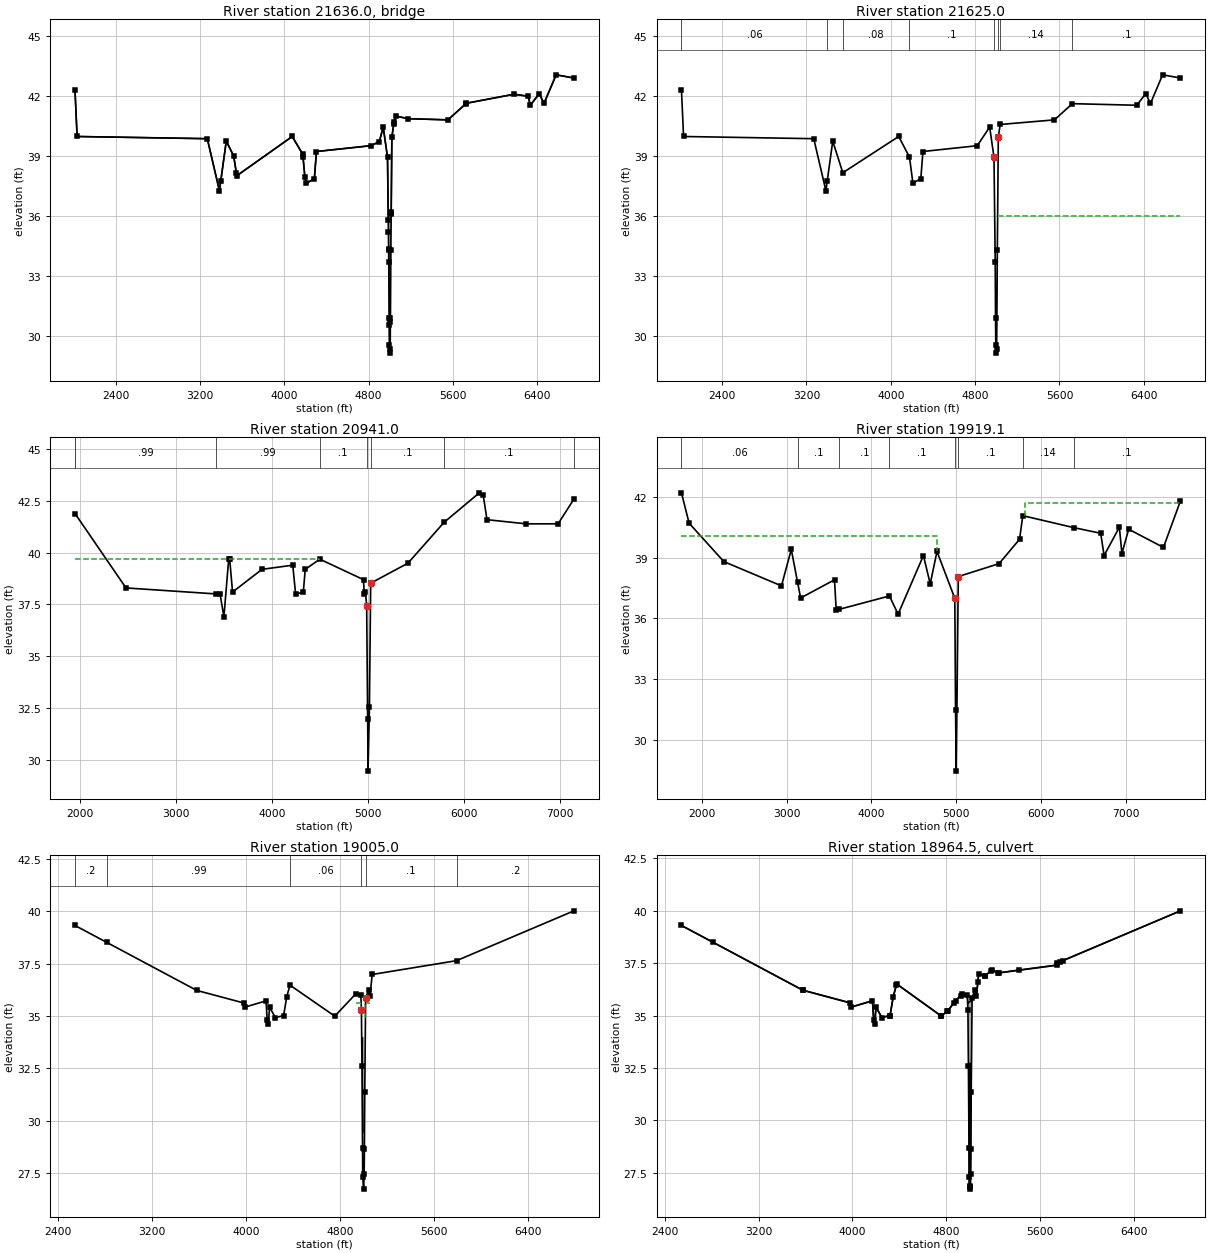
Type RM Length L Ch R = 3 ,21636.0 ,,,
BEGIN DESCRIPTION:
18" PIPELINE
END DESCRIPTION:
Bridge Culvert--1,0,-1,-1, 0
Deck Dist Width WeirC Skew NumUp NumDn MinLoCord MaxHiCord MaxSubmerge Is_Ogee
10,2,2.6,0, 51, 51, , , 0.95, 0, 1,1,,
  2014.4  2034.4  3269.4  3384.4  3396.6  3449.4  3519.4  3544.8  3549.4  4074.9
  4174.9  4177.4  4194.9  4209.9  4284.9  4304.9  4820.1 4900.87 4937.97 4978.77
 4985.87 4987.17 4989.13 4989.22 4990.57 4993.47 4994.37 4995.97 4999.87 5004.07
 5005.67 5006.47 5010.67 5013.56 5013.67 5013.77 5019.87  5037.7 5040.97 5058.87
  5171.8  5551.8  5722.8  5726.8  6178.1  6313.1  6333.1  6418.1  6463.1  6578.1
  6747.6
    42.3   39.98   39.87   37.27   37.74   39.75   39.01   38.17   38.02   39.98
   39.09   38.95   37.95   37.64   37.88   39.23   39.52   39.72   40.45   38.94
    35.8   35.75   35.76   35.76   35.77    35.8    35.8   35.81   35.84   35.87
   35.88   35.89   35.92   36.11   36.17   36.22   39.95   40.58   40.69      41
   40.87   40.81   41.62   41.64   42.09   41.99   41.54   42.12   41.63   43.06
    42.9
    42.3   39.98   39.87   37.27   37.74   39.75   39.01   38.17   38.02   39.98
   39.09   38.95   37.95   37.64   37.88   39.23   39.52   39.72   40.45   38.94
   35.79   35.21   34.34    34.3   34.27    34.3    34.3   34.31   34.34   34.37
   34.38   34.39   34.42    36.1   36.16   36.22   39.95   40.58   40.69      41
   40.87   40.81   41.62   41.64   42.09   41.99   41.54   42.12   41.63   43.06
    42.9
  2014.4  2034.4  3269.4  3384.4  3396.6  3449.4  3519.4  3544.8  3549.4  4074.9
  4174.9  4177.4  4194.9  4209.9  4284.9  4304.9  4820.1 4900.87 4937.97 4978.77
 4985.87 4987.17 4989.13 4989.22 4990.57 4993.47 4994.37 4995.97 4999.87 5004.07
 5005.67 5006.47 5010.67 5013.56 5013.67 5013.77 5019.87  5037.7 5040.97 5058.87
  5171.8  5551.8  5722.8  5726.8  6178.1  6313.1  6333.1  6418.1  6463.1  6578.1
  6747.6
    42.3   39.98   39.87   37.27   37.74   39.75   39.01   38.17   38.02   39.98
   39.09   38.95   37.95   37.64   37.88   39.23   39.52   39.72   40.45   38.94
    35.8   35.75   35.76   35.76   35.77    35.8    35.8   35.81   35.84   35.87
   35.88   35.89   35.92   36.11   36.17   36.22   39.95   40.58   40.69      41
   40.87   40.81   41.62   41.64   42.09   41.99   41.54   42.12   41.63   43.06
    42.9
    42.3   39.98   39.87   37.27   37.74   39.75   39.01   38.17   38.02   39.98
   39.09   38.95   37.95   37.64   37.88   39.23   39.52   39.72   40.45   38.94
   35.79   35.21   34.34    34.3   34.27    34.3    34.3   34.31   34.34   34.37
   34.38   34.39   34.42    36.1   36.16   36.22   39.95   40.58   40.69      41
   40.87   40.81   41.62   41.64   42.09   41.99   41.54   42.12   41.63   43.06
    42.9
Pier Skew, UpSta & Num, DnSta & Num=  ,4994.4, 2 ,4994.4, 2 , 0 , 0 , 0 ,,
      .3      .3
   29.48    35.3
      .3      .3
   29.48    35.3
Pier Skew, UpSta & Num, DnSta & Num=  ,5005.7, 2 ,5005.7, 2 , 0 , 0 , 0 ,,
      .3      .3
   29.59   35.38
      .3      .3
   29.59   35.38
BR Coef= 1 , 1 , 0 ,1.25, 0 ,,,0.8,0,2,0,
WSPro=,,,, 1 ,,,, 0 ,,,, 0 ,,,,-1 ,-1 ,-1 , 0 , 0 , 0 , 0 , 0
BR U #Sta/Elev= 51
  2014.4    42.3  2034.4   39.98  3269.4   39.87  3384.4   37.27  3396.6   37.74
  3449.4   39.75  3519.4   39.01  3544.8   38.17  3549.4   38.02  4074.9   39.98
  4174.9   39.09  4177.4   38.95  4194.9   37.95  4209.9   37.64  4284.9   37.88
  4304.9   39.23  4820.1   39.52 4900.87   39.72 4937.97   40.45 4978.77   38.94
 4985.87   35.79 4987.17   35.21 4989.13   34.34 4989.22    34.3 4990.57    33.7
 4993.47   30.92 4994.37   30.58 4995.97   29.56 4999.87   29.16 5004.07   29.35
 5005.67   30.72 5006.47   30.92 5010.67   34.33 5013.56    36.1 5013.67   36.16
 5013.77   36.22 5019.87   39.95  5037.7   40.58 5040.97   40.69 5058.87      41
  5171.8   40.87  5551.8   40.81  5722.8   41.62  5726.8   41.64  6178.1   42.09
  6313.1   41.99  6333.1   41.54  6418.1   42.12  6463.1   41.63  6578.1   43.06
  6747.6    42.9
BR U #Mann= 8
  2014.4     .06  3396.6      .1  3544.8     .08  4177.4      .1 4978.77     .04
 5019.87      .1  5037.7     .14  5722.8      .1
BR U Banks=4978.77,5019.87
BR D #Sta/Elev= 51
  2014.4    42.3  2034.4   39.98  3269.4   39.87  3384.4   37.27  3396.6   37.74
  3449.4   39.75  3519.4   39.01  3544.8   38.17  3549.4   38.02  4074.9   39.98
  4174.9   39.09  4177.4   38.95  4194.9   37.95  4209.9   37.64  4284.9   37.88
  4304.9   39.23  4820.1   39.52 4900.87   39.72 4937.97   40.45 4978.77   38.94
 4985.87   35.79 4987.17   35.21 4989.13   34.34 4989.22    34.3 4990.57    33.7
 4993.47   30.92 4994.37   30.58 4995.97   29.56 4999.87   29.16 5004.07   29.35
 5005.67   30.72 5006.47   30.92 5010.67   34.33 5013.56    36.1 5013.67   36.16
 5013.77   36.22 5019.87   39.95  5037.7   40.58 5040.97   40.69 5058.87      41
  5171.8   40.87  5551.8   40.81  5722.8   41.62  5726.8   41.64  6178.1   42.09
  6313.1   41.99  6333.1   41.54  6418.1   42.12  6463.1   41.63  6578.1   43.06
  6747.6    42.9
BR D #Mann= 8
  2014.4     .06  3396.6      .1  3544.8     .08  4177.4      .1 4978.77     .04
 5019.87      .1  5037.7     .14  5722.8      .1
BR D Banks=4978.77,5019.87
BC Design=,, 0 ,, 0 ,,,,,,
BC HTab HWMax=43.09
BC Use User HTab Curves=0
BC User HTab FreeFlow(D)= 0

Type RM Length L Ch R = 1 ,21625.0 ,669.8,684,683.1
BEGIN DESCRIPTION:
Downstream Section of Bridge/Culvert/Weir
END DESCRIPTION:
XS GIS Cut Line= 6
      3152870.67     13798830.17      3154734.53     13797932.13
      3155446.11     13797731.21      3155780.97     13797731.21
      3156819.04     13797664.24      3157310.78     13797418.37
#Sta/Elev= 30
  2014.4    42.3  2034.4   39.98  3269.4   39.87  3384.4   37.27  3396.6   37.74
  3449.4   39.75  3544.8   38.17  4074.9   39.98  4177.4   38.95  4209.9   37.64
  4284.9   37.88  4304.9   39.23  4820.1   39.52 4937.97   40.45 4978.77   38.94
 4990.57    33.7 4993.47   30.92 4995.97   29.56 4999.87   29.16 5004.07   29.35
 5010.67   34.33 5019.87   39.95  5037.7   40.58  5551.8   40.81  5722.8   41.62
  6333.1   41.54  6418.1   42.12  6463.1   41.63  6578.1   43.06  6747.6    42.9
#Mann= 8 , 1 , 0
  2014.4     .06       0  3396.6      .1       0  3544.8     .08       0
  4177.4      .1       0 4978.77     .04       0 5019.87      .1       0
  5037.7     .14       0  5722.8      .1       0
#XS Ineff= 2 , 0
       0    4938    39.3  5013.4       0      36
Permanent Ineff=
       F       F
Bank Sta=4978.77,5019.87
XS Rating Curve= 0 ,0
Exp/Cntr=0.5,0.3

Type RM Length L Ch R = 1 ,20941.0 ,1015.4,1021.9,1025.2
BEGIN DESCRIPTION:
Cross Section 20941.0
END DESCRIPTION:
XS GIS Cut Line= 6
       3152590.1     13798900.24      3153119.39     13798856.93
      3154471.69     13798433.82      3155680.12     13798425.39
      3156667.94     13798061.87      3157414.74     13797417.81
#Sta/Elev= 30
  1947.6    41.9  2478.6    38.3  3418.2   38.01  3458.6      38  3498.6    36.9
  3548.6    39.7  3558.6    39.7  3588.6    38.1  3895.6    39.2  4215.6    39.4
  4245.6      38  4325.6    38.1  4345.6    39.2  4497.6   39.69  4952.9    38.7
  4959.4      38  4972.5   38.08  4985.5   37.44  4995.8   31.98  4999.8   29.44
  5014.1   32.52  5027.4   38.53  5416.2    39.5  5791.2   41.47  6158.8    42.9
  6198.8    42.8  6238.8    41.6  6648.8    41.4  6978.8    41.4  7144.9    42.6
#Mann= 8 , 1 , 0
  1947.6      .2       0  1947.6     .99       0  3418.2     .99       0
  4497.6      .1       0  4985.5     .04       0  5027.4      .1       0
  5791.2      .1       0  7144.9      .2       0
#XS Ineff= 2 , 0
       0  4492.9    39.7               0
Permanent Ineff=
       F       F
Bank Sta=4985.5,5027.4
XS Rating Curve= 0 ,0
Exp/Cntr=0.3,0.1

Type RM Length L Ch R = 1 ,19919.1 ,749.7,914.1,758.3
BEGIN DESCRIPTION:
Cross Section 19919.1
END DESCRIPTION:
XS GIS Cut Line= 6
      3152321.53     13799176.13      3153578.04     13799492.23
      3155348.21     13799413.21       3155624.8     13799456.67
      3156940.58      13799397.4      3158078.55     13798954.86
#Sta/Elev= 30
  1757.9    42.2  1847.9    40.7  2257.9    38.8  2937.9    37.6  3053.6    39.4
  3127.1    37.8  3163.6      37  3563.6    37.9  3583.6    36.4  3618.9   36.44
  4211.9    37.1  4313.6    36.2  4612.8    39.1  4692.8    37.7  4772.8    39.3
    4983   36.98  4991.6   31.48  4999.9   28.44  5024.3   38.06  5505.7    38.7
  5746.4    39.9  5785.3   41.07  6385.3   40.48  6704.3    40.2  6744.3    39.1
  6924.3    40.5  6954.3    39.2  7034.3    40.4  7444.3    39.5  7645.3    41.8
#Mann= 8 , 1 , 0
  1757.9     .06       0  3127.1      .1       0  3618.9      .1       0
  4211.9      .1       0    4983     .04       0  5024.3      .1       0
  5785.3     .14       0  6385.3      .1       0
#XS Ineff= 2 , 0
       0  4772.8   40.05    5808       0    41.7
Permanent Ineff=
       F       F
Bank Sta=4983,5024.3
XS Rating Curve= 0 ,0
Exp/Cntr=0.5,0.3

Type RM Length L Ch R = 1 ,19005.0 ,81,81,81
BEGIN DESCRIPTION:
Upstream Section of Bridge/Culvert/Weir
END DESCRIPTION:
XS GIS Cut Line= 4
      3153021.42     13800212.49      3155279.56     13800340.07
      3155886.47     13800376.48      3157263.39     13800441.55
#Sta/Elev= 30
  2544.1   39.32  2815.4   38.51  3580.3   36.22  3980.3   35.62  3990.3   35.42
  4170.3   35.72  4180.3   34.82  4190.3   34.62  4200.3   35.42  4250.3   34.92
  4320.3   35.02  4346.9   35.92  4374.4   36.47  4755.8   34.99  4933.7   36.05
  4977.5   36.01  4982.7   35.28  4987.1   32.59  4992.2   28.68  4993.7   27.29
  5001.1   26.73    5006   27.43  5007.9   28.64    5011   31.39  5018.5   35.86
  5043.1   36.23  5055.4   35.96  5074.3   36.98  5792.3   37.64  6792.3   40.02
#Mann= 6 ,-1 , 0
  2544.1      .2       0  2815.4     .99       0  4374.4     .06       0
  4982.7    .035       0  5018.5      .1       0  5792.3      .2       0
#XS Ineff= 3 ,-1
  2544.1  4933.7   36.05  4933.7  4982.2    35.6  5016.9  5055.4    35.6
Permanent Ineff=
       F       F       F
#Block Obstruct= 2 , 0
       0  4991.2      34  5007.9       0      34
Bank Sta=4982.7,5018.5
XS Rating Curve= 0 ,0
Exp/Cntr=0.5,0.3

Type RM Length L Ch R = 2 ,18964.5 ,,,
BEGIN DESCRIPTION:
SCRANTON ROAD
Structure ID: C61-13
END DESCRIPTION:
Bridge Culvert--1,0,-1,-1, 0
Deck Dist Width WeirC Skew NumUp NumDn MinLoCord MaxHiCord MaxSubmerge Is_Ogee
10,61,3,0, 52, 52, , , 0.95, 0, 1,1,,
  2544.1  2815.4  3580.3  3580.4  3980.3  3990.3  4170.3  4180.3  4190.3  4200.3
  4250.3  4315.4  4320.3  4346.9  4374.4  4376.9  4753.8  4755.8  4806.8  4813.4
  4865.6  4877.1  4920.7  4933.7  4977.5  4982.7  4987.1  4992.2  4993.7  4997.7
  4998.8  5001.1    5006  5007.9    5011  5018.5  5043.1  5055.4  5067.4  5074.3
  5125.2  5127.7  5181.2  5186.9  5239.5  5243.4  5413.8  5738.3    5741  5763.8
  5792.3  6792.3
    39.3   38.49    36.2   36.21   35.61   35.41   35.71   34.81   34.72   35.41
   34.91      35   35.01   35.91   36.46   36.51   34.99   34.98   35.21   35.24
   35.63   35.71   35.96   36.04      36   35.57    35.6   35.63   35.64   35.66
   35.67   35.67   35.67   35.67   35.67   35.85   36.22   35.95    36.6   36.97
    36.9    36.9   37.15   37.18   37.05   37.04   37.17   37.41   37.51   37.56
   37.63      40
    39.3   38.49    36.2    36.2    35.6    35.4    35.7    34.8    34.6    35.4
    34.9   34.99      35    35.9   36.45    36.5   34.98   34.97    35.2   35.23
   35.62    35.7   35.95   36.03   35.99   35.26   32.57   28.66   27.27   26.86
   26.81   26.71   27.41   28.62   31.37   35.84   36.21   35.94   36.59   36.96
   36.89   36.89   37.14   37.17   37.04   37.03   37.16    37.4    37.5   37.55
   37.62      40
  2544.1  2815.4  3580.3  3580.4  3980.3  3990.3  4170.3  4180.3  4190.3  4200.3
  4250.3  4315.4  4320.3  4346.9  4374.4  4376.9  4753.8  4755.8  4806.8  4813.4
  4865.6  4877.1  4920.7  4933.7  4977.5  4982.7  4987.1  4992.2  4993.7  4997.7
  4998.8  5001.1    5006  5007.9    5011  5018.5  5043.1  5055.4  5067.4  5074.3
  5125.2  5127.7  5181.2  5186.9  5239.5  5243.4  5413.8  5738.3    5741  5763.8
  5792.3  6792.3
    39.3   38.49    36.2   36.21   35.61   35.41   35.71   34.81   34.72   35.41
   34.91      35   35.01   35.91   36.46   36.51   34.99   34.98   35.21   35.24
   35.63   35.71   35.96   36.04      36   35.57    35.6   35.63   35.64   35.66
   35.67   35.67   35.67   35.67   35.67   35.85   36.22   35.95    36.6   36.97
    36.9    36.9   37.15   37.18   37.05   37.04   37.17   37.41   37.51   37.56
   37.63      40
   39.25   38.44   36.15   36.15   35.55   35.35   35.65   34.75   34.55   35.35
   34.85   34.94   34.95   35.85    36.4   36.45   34.93   34.92   35.15   35.18
   35.57   35.65    35.9   35.98   35.94   35.21   32.52   28.61   27.22   26.81
   26.76   26.66   27.36   28.57   31.32   35.79   36.16   35.89   36.54   36.91
   36.84   36.84   37.09   37.12   36.99   36.98   37.11   37.35   37.45    37.5
   37.57   39.95
BR Coef= 1 , 0 , 0 ,1.25, 0 ,,,0.8,-1,2,0,
WSPro=,,,, 1 ,,,, 0 ,,,, 0 ,,,,-1 ,-1 ,-1 , 0 , 0 , 0 , 0 , 0
Culvert=1,6,,61,0.015,0.2,1,1,3,26.74,4995.2,26.61,4995.2,Culvert #1  , 0 ,10
Culvert Bottom n=0.015
Culvert=1,6,,61,0.015,0.2,1,1,3,26.74,5003.9,26.61,5003.9,Culvert #2  , 0 ,10
Culvert Bottom n=0.015
BR U #Sta/Elev= 52
  2544.1    39.3  2815.4   38.49  3580.3    36.2  3580.4    36.2  3980.3    35.6
  3990.3    35.4  4170.3    35.7  4180.3    34.8  4190.3    34.6  4200.3    35.4
  4250.3    34.9  4315.4   34.99  4320.3      35  4346.9    35.9  4374.4   36.45
  4376.9    36.5  4753.8   34.98  4755.8   34.97  4806.8    35.2  4813.4   35.23
  4865.6   35.62  4877.1    35.7  4920.7   35.95  4933.7   36.03  4977.5   35.99
  4982.7   35.26  4987.1   32.57  4992.2   28.66  4993.7   27.27  4997.7   26.86
  4998.8   26.81  5001.1   26.71    5006   27.41  5007.9   28.62    5011   31.37
  5018.5   35.84  5043.1   36.21  5055.4   35.94  5067.4   36.59  5074.3   36.96
  5125.2   36.89  5127.7   36.89  5181.2   37.14  5186.9   37.17  5239.5   37.04
  5243.4   37.03  5413.8   37.16  5738.3    37.4    5741    37.5  5763.8   37.55
  5792.3   37.62  6792.3      40
BR U #Mann= 6
  2544.1      .2  2815.4     .99  4374.4     .06  4982.7    .035  5018.5      .1
  5792.3      .2
BR U Banks=4982.7,5018.5
BR D #Sta/Elev= 52
  2544.1   39.25  2815.4   38.44  3580.3   36.15  3580.4   36.15  3980.3   35.55
  3990.3   35.35  4170.3   35.65  4180.3   34.75  4190.3   34.55  4200.3   35.35
  4250.3   34.85  4315.4   34.94  4320.3   34.95  4346.9   35.85  4374.4    36.4
  4376.9   36.45  4753.8   34.93  4755.8   34.92  4806.8   35.15  4813.4   35.18
  4865.6   35.57  4877.1   35.65  4920.7    35.9  4933.7   35.98  4977.5   35.94
  4982.7   35.21  4987.1   32.52  4992.2   28.61  4993.7   27.22  4997.7   26.81
  4998.8   26.76  5001.1   26.66    5006   27.36  5007.9   28.57    5011   31.32
  5018.5   35.79  5043.1   36.16  5055.4   35.89  5067.4   36.54  5074.3   36.91
  5125.2   36.84  5127.7   36.84  5181.2   37.09  5186.9   37.12  5239.5   36.99
  5243.4   36.98  5413.8   37.11  5738.3   37.35    5741   37.45  5763.8    37.5
  5792.3   37.57  6792.3   39.95
BR D #Mann= 6
  2544.1      .2  2815.4     .99  4374.4     .06  4982.7    .035  5018.5      .1
  5792.3      .2
BR D Banks=4982.7,5018.5
BC Design=,, 0 ,, 0 ,,,,,,
BC HTab HWMax=40.02
BC Use User HTab Curves=0
BC User HTab FreeFlow(D)= 0

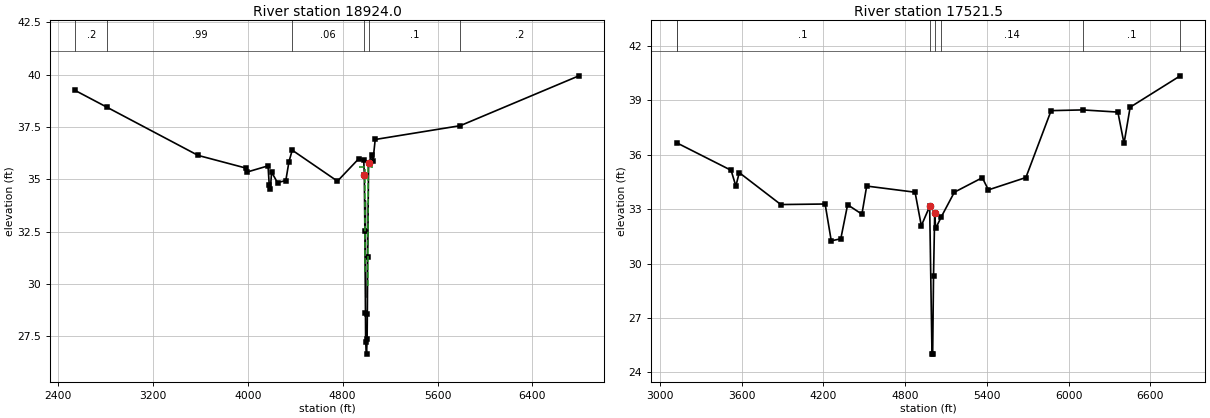
Type RM Length L Ch R = 1 ,18924.0 ,1492,1402.5,1388.7
BEGIN DESCRIPTION:
Downstream Section of Bridge/Culvert/Weir
END DESCRIPTION:
XS GIS Cut Line= 4
       3153017.5     13800293.39      3155275.64     13800420.97
      3155882.55     13800457.38      3157259.47     13800522.46
#Sta/Elev= 30
  2544.1   39.24  2815.4   38.43  3580.3   36.14  3980.3   35.54  3990.3   35.34
  4170.3   35.64  4180.3   34.74  4190.3   34.54  4200.3   35.34  4250.3   34.84
  4320.3   34.94  4346.9   35.84  4374.4   36.39  4755.8   34.91  4933.7   35.97
  4977.5   35.93  4982.7    35.2  4987.1   32.51  4992.2    28.6  4993.7   27.21
  5001.1   26.65    5006   27.35  5007.9   28.56    5011   31.31  5018.5   35.78
  5043.1   36.15  5055.4   35.88  5074.3    36.9  5792.3   37.56  6792.3   39.94
#Mann= 6 ,-1 , 0
  2544.1      .2       0  2815.4     .99       0  4374.4     .06       0
  4982.7    .035       0  5018.5      .1       0  5792.3      .2       0
#XS Ineff= 3 ,-1
  2544.1  4933.7   35.97  4933.7  4989.7    35.6  5009.4  5055.4    35.6
Permanent Ineff=
       F       F       F
#Block Obstruct= 2 , 0
       0  4991.2      34  5007.9       0      34
Bank Sta=4982.7,5018.5
XS Rating Curve= 0 ,0
Exp/Cntr=0.5,0.3

Type RM Length L Ch R = 1 ,17521.5 ,663.3,646.9,646
BEGIN DESCRIPTION:
Cross Section 17521.5
END DESCRIPTION:
XS GIS Cut Line= 4
      3153512.76     13801801.32      3155288.37      13801834.2
      3155485.66      13801834.2      3157206.47     13801910.92
#Sta/Elev= 30
  3123.3   36.67  3523.3   35.15  3558.3   34.28  3583.3   35.02  3888.3   33.26
  4213.3   33.29  4258.3   31.26  4328.3   31.37  4378.3   33.25  4483.3   32.73
  4518.3   34.28  4873.3   33.94  4919.2   32.09  4980.4   33.16  4997.5   25.01
  5002.5   25.01  5008.7    29.3  5017.5   32.82  5024.2   31.94  5065.7   32.58
  5161.5   33.94  5366.5   34.74  5411.5   34.07  5686.5   34.75  5871.5   38.44
  6102.9   38.48  6361.5   38.36  6406.5   36.63  6451.5   38.63    6819   40.36
#Mann= 7 , 1 , 0
  3123.3      .2       0  3123.3      .1       0  4980.4     .04       0
  5017.5      .1       0  5065.7     .14       0  6102.9      .1       0
    6819      .2       0
Bank Sta=4980.4,5017.5
XS Rating Curve= 0 ,0
Exp/Cntr=0.3,0.1