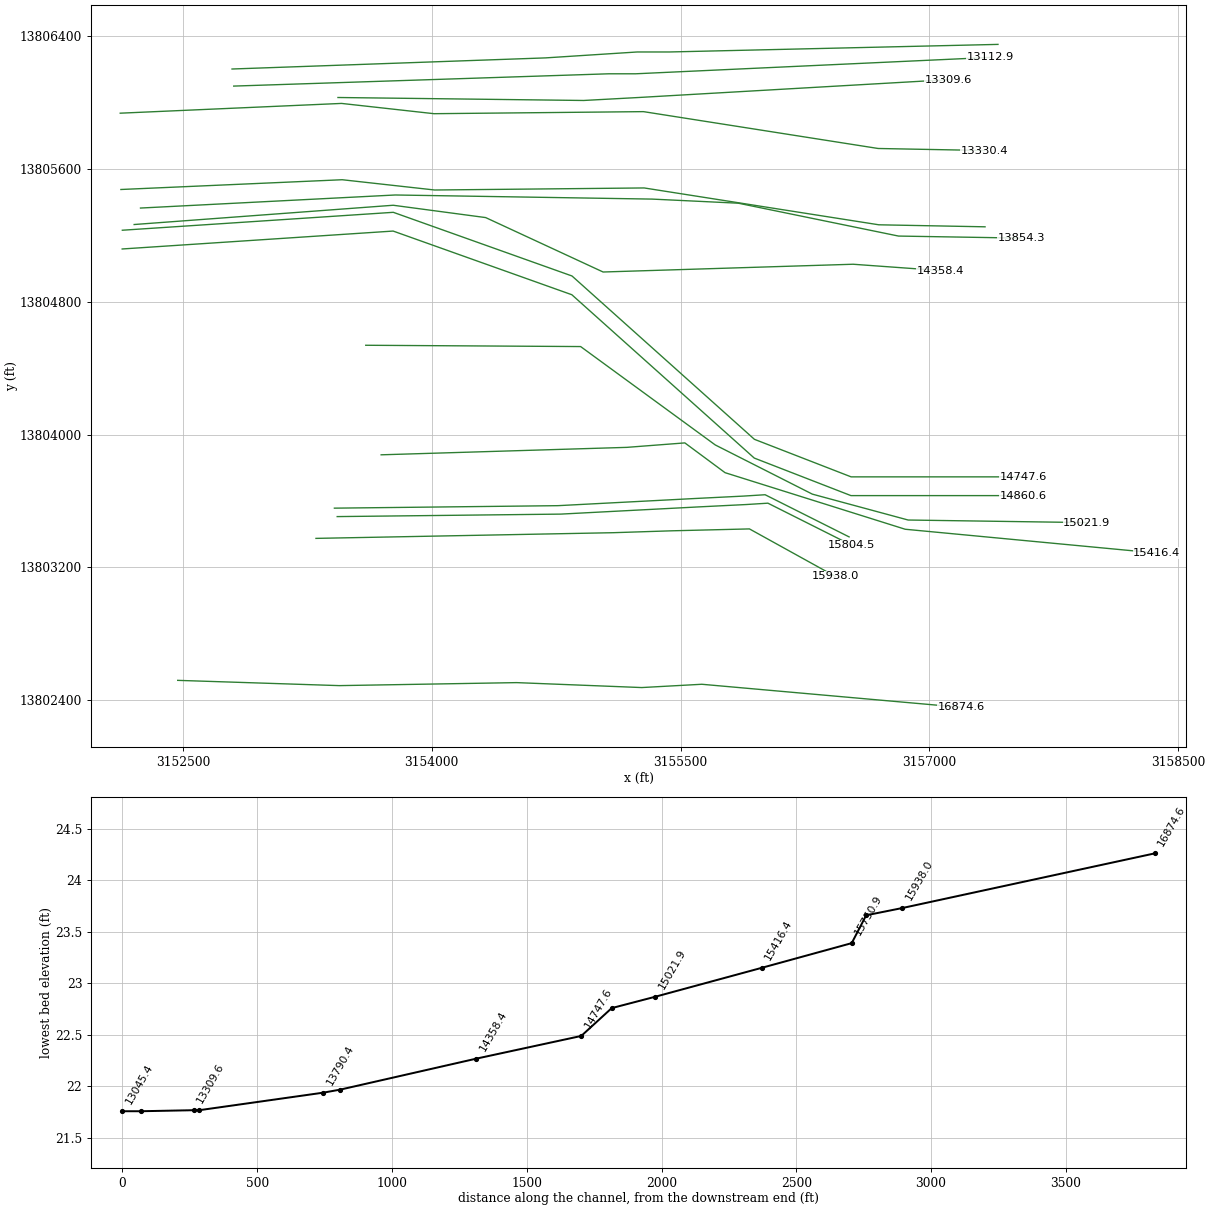
HEC-RAS study C106-01-00.PRJ: C106-01-00

--- C106-01-00.g01 (geometry) --- (continued)

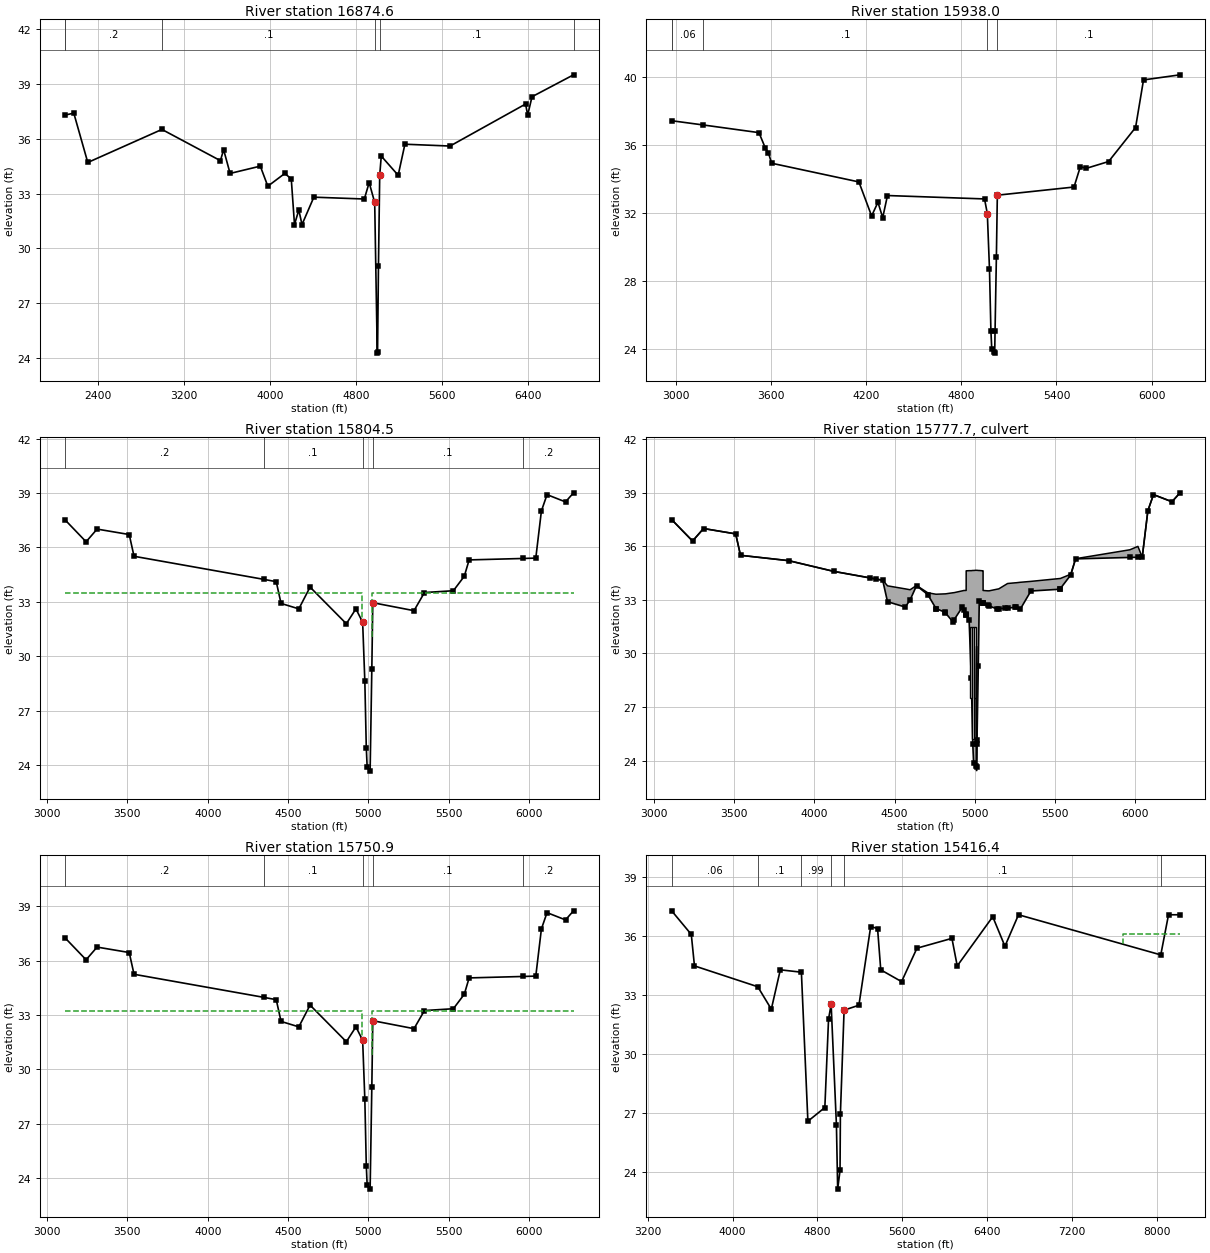
Type RM Length L Ch R = 1 ,16874.6 ,926.9,936.6,954.7
BEGIN DESCRIPTION:
Cross Section 16874.6
END DESCRIPTION:
XS GIS Cut Line= 6
      3152468.58      13802518.3      3153442.31     13802486.57
      3154511.51     13802504.66      3155265.67     13802474.89
      3155627.86     13802494.74      3157190.76     13802355.81
#Sta/Elev= 30
  2096.3    37.3  2176.3    37.4  2306.3    34.7  2996.3   36.51  3540.5    34.8
  3570.5    35.4  3630.5    34.1  3911.7    34.5  3981.7    33.4  4139.9    34.1
  4199.9    33.8  4229.9    31.3  4269.9    32.1  4299.9    31.3  4409.9    32.8
  4879.9    32.7  4924.7    33.6  4976.2   32.51  5000.1   24.26  5002.8    24.3
  5011.3   29.04  5022.9   34.01  5037.4   35.05  5194.7      34  5257.4    35.7
  5677.4    35.6    6380    37.9    6400    37.3    6440    38.3  6826.5    39.5
#Mann= 6 , 1 , 0
  2096.3      .2       0  2096.3      .2       0  2996.3      .1       0
  4976.2     .04       0  5022.9      .1       0  6826.5      .2       0
Bank Sta=4976.2,5022.9
XS Rating Curve= 0 ,0
Exp/Cntr=0.3,0.1

Type RM Length L Ch R = 1 ,15938.0 ,114,133.5,132.5
BEGIN DESCRIPTION:
Cross Section 15938.0-Interpolated
END DESCRIPTION:
XS GIS Cut Line= 5
        3153302.      13803374.1       3155093.4     13803408.34
      3155447.11     13803419.75      3155914.93     13803431.16
      3156431.18     13803145.57
#Sta/Elev= 28
  2975.1    37.4  3174.6   37.15  3525.1    36.7  3565.1    35.8  3585.1    35.5
  3605.1    34.9  4155.1    33.8  4235.1    31.8  4275.1    32.6  4305.1    31.7
  4335.1      33  4946.8    32.8  4964.4   31.94    4978   28.68    4987   25.03
  4992.4   23.97  5005.8    23.8  5010.9   23.73  5013.1   25.02  5021.5   29.37
  5027.5   33.02  5510.7    33.5  5550.7    34.7  5588.7    34.6  5728.7      35
  5898.7      37  5948.7    39.8  6178.7    40.1
#Mann= 5 , 1 , 0
  2975.1      .2       0  2975.1     .06       0  3174.6      .1       0
  4964.4     .04       0  5027.5      .1       0
Bank Sta=4964.4,5027.5
XS Rating Curve= 0 ,0
Exp/Cntr=0.5,0.3

Type RM Length L Ch R = 1 ,15804.5 ,53.6,53.6,53.6
BEGIN DESCRIPTION:
Upstream Section of Bridge/Culvert/Weir
END DESCRIPTION:
XS GIS Cut Line= 6
       3153429.9     13803505.43      3154777.29      13803520.4
      3155604.74     13803563.65      3155896.58     13803578.17
       3156026.1     13803586.31      3156532.37     13803332.17
#Sta/Elev= 30
  3112.7   37.51  3242.7   36.31  3311.2   37.01  3511.2   36.71  3541.2   35.51
  4347.3   34.24  4426.4   34.11  4456.4   32.91    4567   32.61    4637   33.81
  4862.8   31.79  4922.5   32.61  4964.4   31.87    4978   28.61    4987   24.96
  4992.4    23.9  5010.9   23.66  5021.5    29.3  5027.5   32.95  5284.1   32.51
  5349.1   33.51  5529.1   33.61  5597.2   34.41  5627.2   35.31  5965.2   35.39
  6042.2   35.41  6077.2   38.01  6112.2   38.91  6227.2   38.51  6277.2   39.01
#Mann= 5 , 1 , 0
  3112.7      .2       0  4347.3      .1       0  4964.4     .04       0
  5027.5      .1       0  5965.2      .2       0
#XS Ineff= 2 , 0
       0  4962.7    33.5  5024.4       0    33.5
Permanent Ineff=
       F       F
Bank Sta=4964.4,5027.5
XS Rating Curve= 0 ,0
Exp/Cntr=0.5,0.3

Type RM Length L Ch R = 2 ,15777.7 ,,,
BEGIN DESCRIPTION:
PANAIR ROAD
Structure ID: C61-12
END DESCRIPTION:
Bridge Culvert--1,0,-1,-1, 0
Deck Dist Width WeirC Skew NumUp NumDn MinLoCord MaxHiCord MaxSubmerge Is_Ogee
10,33.6,3,0, 60, 60, , , 0.95, 0, 1,1,,
  3112.7  3242.7  3311.2  3511.2  3541.2  3841.2  4121.6  4347.3  4387.3  4426.4
  4456.4    4567    4597    4637    4707    4758  4760.2    4814  4816.4  4862.8
  4871.7  4922.5  4932.3 4945.99  4946.1 4946.21  4964.4    4978    4987  4992.4
  5005.8  5010.9  5013.1  5013.5  5021.5  5027.5 5051.19  5051.3 5051.41  5080.7
  5089.2  5137.2    5149  5189.2  5203.8  5252.1  5254.7  5284.1  5349.1  5529.1
  5531.8  5597.2  5627.2  5965.2  6015.2  6042.2  6077.2  6112.2  6227.2  6277.2
    37.5    36.3      37    36.7    35.5    35.2    34.6   34.24   34.17   34.11
   33.79   33.62   33.57   33.81    33.4   33.32   33.32   33.34   33.34    33.4
   33.41   33.51   33.53   33.53   34.63   34.63   34.64   34.64   34.65   34.65
   34.66   34.66   34.66   34.66   34.65   34.65   34.63   34.63   33.53   33.51
   33.51    33.6   33.62   33.84   33.92   33.96   33.96   33.99   34.04    34.2
    34.2   34.44   35.31   35.81      36    35.4      38    38.9    38.5      39
    37.5    36.3      37    36.7    35.5    35.2    34.6   34.23   34.16    34.1
    32.9    32.6      33    33.8    33.3   32.52   32.51   32.31   32.28   31.78
    31.9    32.6   32.43   32.19   32.18   32.18   31.86    28.6   24.95   23.89
   23.72   23.65   24.94   25.15   29.29   32.94   32.83   32.83   32.83   32.69
   32.66    32.5   32.51   32.53   32.54   32.59   32.58    32.5    33.5    33.6
   33.63    34.4    35.3   35.38   35.39    35.4      38    38.9    38.5      39
  3112.7  3242.7  3311.2  3511.2  3541.2  3841.2  4121.6  4347.3  4387.3  4426.4
  4456.4    4567    4597    4637    4707    4758  4760.2    4814  4816.4  4862.8
  4871.7  4922.5  4932.3 4945.99  4946.1 4946.21  4964.4    4978    4987  4992.4
  5005.8  5010.9  5013.1  5013.5  5021.5  5027.5 5051.19  5051.3 5051.41  5080.7
  5089.2  5137.2    5149  5189.2  5203.8  5252.1  5254.7  5284.1  5349.1  5529.1
  5531.8  5597.2  5627.2  5965.2  6015.2  6042.2  6077.2  6112.2  6227.2  6277.2
    37.5    36.3      37    36.7    35.5    35.2    34.6   34.24   34.17   34.11
   33.79   33.62   33.57   33.81    33.4   33.32   33.32   33.34   33.34    33.4
   33.41   33.51   33.53   33.53   34.63   34.63   34.64   34.64   34.65   34.65
   34.66   34.66   34.66   34.66   34.65   34.65   34.63   34.63   33.53   33.51
   33.51    33.6   33.62   33.84   33.92   33.96   33.96   33.99   34.04    34.2
    34.2   34.44   35.31   35.81      36    35.4      38    38.9    38.5      39
   37.25   36.05   36.75   36.45   35.25   34.95   34.35   33.98   33.91   33.85
   32.65   32.35   32.75   33.55   33.05   32.27   32.26   32.06   32.03   31.53
   31.65   32.35   32.18   31.94   31.93   31.93   31.61   28.35    24.7   23.64
   23.47    23.4   24.69    24.9   29.04   32.69   32.58   32.58   32.58   32.44
   32.41   32.25   32.26   32.28   32.29   32.34   32.33   32.25   33.25   33.35
   33.38   34.15   35.05   35.13   35.14   35.15   37.75   38.65   38.25   38.75
BR Coef= 1 , 0 , 0 ,1.25, 0 ,,,0.8,-1,2,0,
WSPro=,,,, 1 ,,,, 0 ,,,, 0 ,,,,-1 ,-1 ,-1 , 0 , 0 , 0 , 0 , 0
Culvert=2,4,10,33.6,0.015,0.4,1,8,1,27.5,4977.7,27.45,4977.7,Culvert #1  , 0 ,10
Culvert Bottom n=0.015
Culvert=2,6.3,10,33.6,0.015,0.4,1,8,1,25.2,4988.7,25.15,4988.7,Culvert #2  , 0 ,10
Culvert Bottom n=0.015
Culvert=2,4,10,33.6,0.015,0.4,1,8,1,27.5,4999.6,27.45,4999.6,Culvert #3  , 0 ,10
Culvert Bottom n=0.015
Culvert=1,7,,33.6,0.015,0.5,1,1,3,23.41,5010.8,23.1,5010.8,Culvert #4  , 0 ,10
Culvert Bottom n=0.015
BR U #Sta/Elev= 60
  3112.7    37.5  3242.7    36.3  3311.2      37  3511.2    36.7  3541.2    35.5
  3841.2    35.2  4121.6    34.6  4347.3   34.23  4387.3   34.16  4426.4    34.1
  4456.4    32.9    4567    32.6    4597      33    4637    33.8    4707    33.3
    4758   32.52  4760.2   32.51    4814   32.31  4816.4   32.28  4862.8   31.78
  4871.7    31.9  4922.5    32.6  4932.3   32.43 4945.99   32.19  4946.1   32.18
 4946.21   32.18  4964.4   31.86    4978    28.6    4987   24.95  4992.4   23.89
  5005.8   23.72  5010.9   23.65  5013.1   24.94  5013.5   25.15  5021.5   29.29
  5027.5   32.94 5051.19   32.83  5051.3   32.83 5051.41   32.83  5080.7   32.69
  5089.2   32.66  5137.2    32.5    5149   32.51  5189.2   32.53  5203.8   32.54
  5252.1   32.59  5254.7   32.58  5284.1    32.5  5349.1    33.5  5529.1    33.6
  5531.8   33.63  5597.2    34.4  5627.2    35.3  5965.2   35.38  6015.2   35.39
  6042.2    35.4  6077.2      38  6112.2    38.9  6227.2    38.5  6277.2      39
BR U #Mann= 5
  3112.7      .2  4347.3      .1  4964.4     .04  5027.5      .1  5965.2      .2
BR U Banks=4964.4,5027.5
BR D #Sta/Elev= 60
  3112.7   37.25  3242.7   36.05  3311.2   36.75  3511.2   36.45  3541.2   35.25
  3841.2   34.95  4121.6   34.35  4347.3   33.98  4387.3   33.91  4426.4   33.85
  4456.4   32.65    4567   32.35    4597   32.75    4637   33.55    4707   33.05
    4758   32.27  4760.2   32.26    4814   32.06  4816.4   32.03  4862.8   31.53
  4871.7   31.65  4922.5   32.35  4932.3   32.18 4945.99   31.94  4946.1   31.93
 4946.21   31.93  4964.4   31.61    4978   28.35    4987    24.7  4992.4   23.64
  5005.8   23.47  5010.9    23.4  5013.1   24.69  5013.5    24.9  5021.5   29.04
  5027.5   32.69 5051.19   32.58  5051.3   32.58 5051.41   32.58  5080.7   32.44
  5089.2   32.41  5137.2   32.25    5149   32.26  5189.2   32.28  5203.8   32.29
  5252.1   32.34  5254.7   32.33  5284.1   32.25  5349.1   33.25  5529.1   33.35
  5531.8   33.38  5597.2   34.15  5627.2   35.05  5965.2   35.13  6015.2   35.14
  6042.2   35.15  6077.2   37.75  6112.2   38.65  6227.2   38.25  6277.2   38.75
BR D #Mann= 5
  3112.7      .2  4347.3      .1  4964.4     .04  5027.5      .1  5965.2      .2
BR D Banks=4964.4,5027.5
BC Design=,, 0 ,, 0 ,,,,,,
BC HTab HWMax=39.01
BC Use User HTab Curves=0
BC User HTab FreeFlow(D)= 0

Type RM Length L Ch R = 1 ,15750.9 ,351.1,334.5,264.5
BEGIN DESCRIPTION:
Downstream Section of Bridge/Culvert/Weir
END DESCRIPTION:
XS GIS Cut Line= 6
      3153413.06     13803556.32      3154760.45     13803571.28
       3155587.9     13803614.53      3155879.74     13803629.05
      3156009.26     13803637.19      3156515.52     13803383.06
#Sta/Elev= 30
  3112.7   37.24  3242.7   36.04  3311.2   36.74  3511.2   36.44  3541.2   35.24
  4347.3   33.97  4426.4   33.84  4456.4   32.64    4567   32.34    4637   33.54
  4862.8   31.52  4922.5   32.34  4964.4    31.6    4978   28.34    4987   24.69
  4992.4   23.63  5010.9   23.39  5021.5   29.03  5027.5   32.68  5284.1   32.24
  5349.1   33.24  5529.1   33.34  5597.2   34.14  5627.2   35.04  5965.2   35.12
  6042.2   35.14  6077.2   37.74  6112.2   38.64  6227.2   38.24  6277.2   38.74
#Mann= 5 , 1 , 0
  3112.7      .2       0  4347.3      .1       0  4964.4     .04       0
  5027.5      .1       0  5965.2      .2       0
#XS Ineff= 2 , 0
       0  4962.7    33.2  5024.4       0    33.2
Permanent Ineff=
       F       F
Bank Sta=4964.4,5027.5
XS Rating Curve= 0 ,0
Exp/Cntr=0.5,0.3

Type RM Length L Ch R = 1 ,15416.4 ,628.5,394.5,107
BEGIN DESCRIPTION:
Cross Section 15416.4-Interpolated
END DESCRIPTION:
XS GIS Cut Line= 6
       3153694.8     13803877.85      3155175.52     13803922.72
      3155525.51     13803949.64       3155767.8     13803770.16
      3156853.66     13803429.15      3158370.27     13803285.56
#Sta/Elev= 30
  3425.4    37.3  3610.4    36.1  3640.4    34.5  4237.7   33.44  4365.4    32.3
  4450.4    34.3  4649.1   34.18  4710.4    26.6  4870.4    27.3  4905.4    31.8
  4929.8   32.54  4979.7   26.41  4991.4   23.15  5013.7    24.1  5017.1   26.97
  5051.9   32.25  5191.8    32.5  5302.8    36.5  5367.8    36.4  5397.8    34.3
  5594.3    33.7  5739.3    35.4  6069.3    35.9  6119.3    34.5  6454.3      37
  6569.3    35.5  6697.5    37.1  8039.6   35.06  8112.5    37.1  8220.9    37.1
#Mann= 6 , 1 , 0
  3425.4     .06       0  4237.7      .1       0  4649.1     .99       0
  4929.8     .04       0  5051.9      .1       0  8039.6      .2       0
#XS Ineff= 2 , 0
       0                  7682.8       0    36.1
Permanent Ineff=
       F       F
Bank Sta=4929.8,5051.9
XS Rating Curve= 0 ,0
Exp/Cntr=0.3,0.1

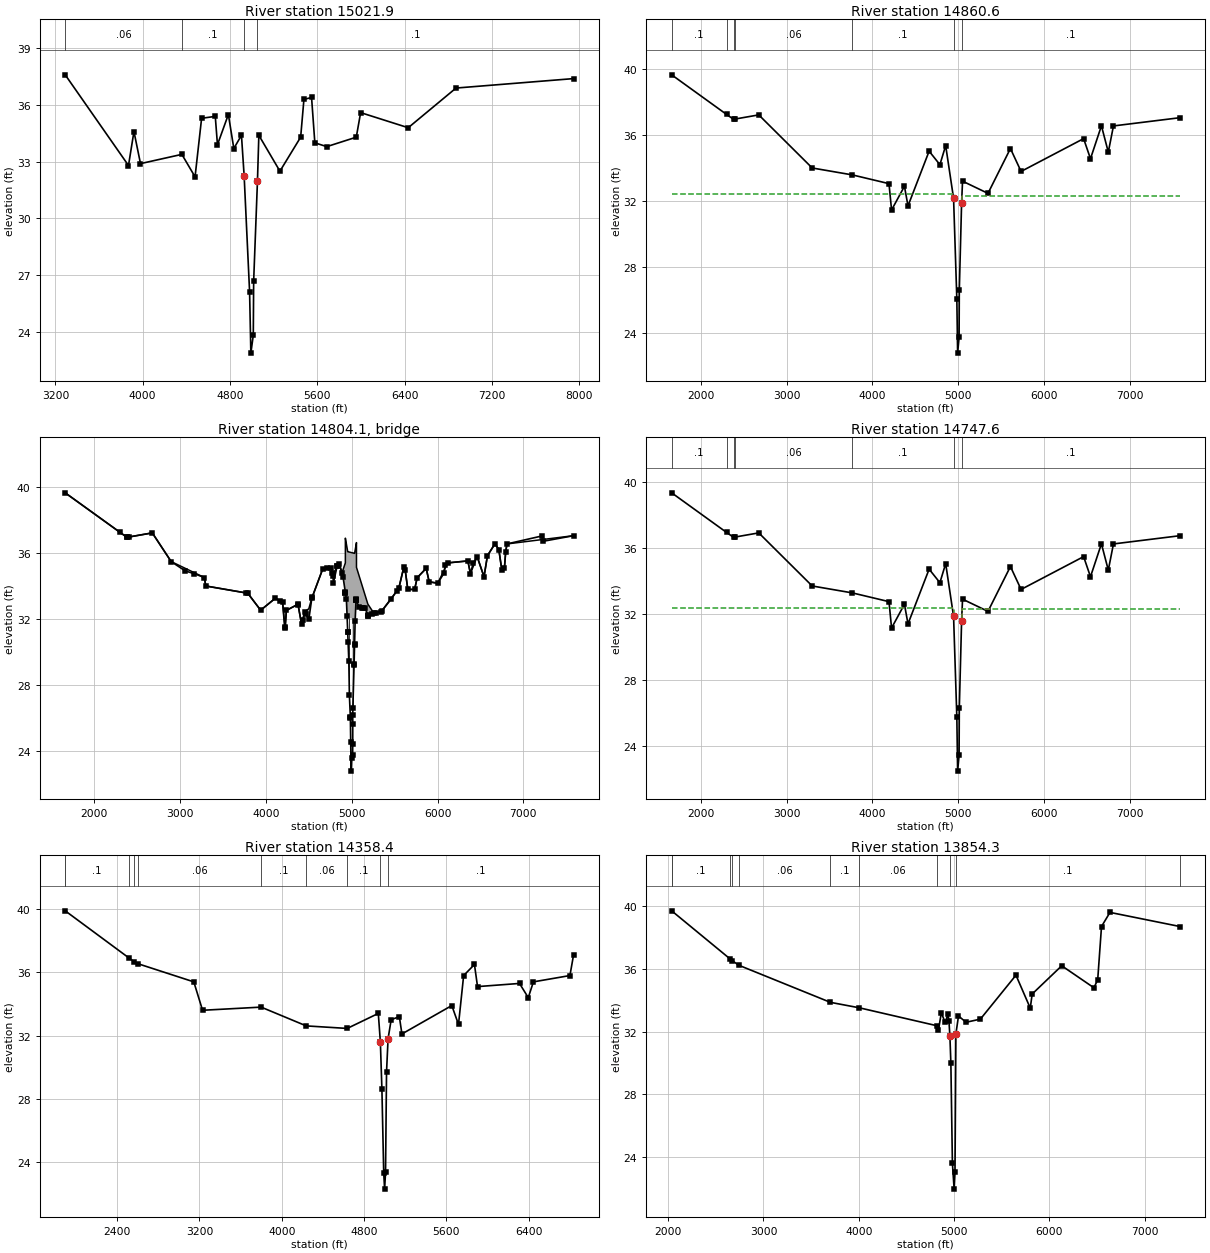
Type RM Length L Ch R = 1 ,15021.9 ,378.1,161.3,70.7
BEGIN DESCRIPTION:
Cross Section 15021.9-Interpolated
END DESCRIPTION:
XS GIS Cut Line= 6
      3153601.99     13804538.15      3154897.26     13804530.34
      3155708.75     13803937.33      3156293.96     13803640.82
      3156871.37     13803484.76      3157948.21     13803469.16
#Sta/Elev= 30
    3290    37.6    3870    32.8    3920    34.6    3980    32.9  4359.1   33.39
    4480    32.2    4540    35.3  4665.3    35.4  4685.3    33.9  4785.3    35.5
  4835.3    33.7  4905.3    34.4  4929.8   32.26  4979.7   26.13  4991.4   22.87
  5013.7   23.82  5017.1   26.69  5051.9   31.97  5064.6    34.4  5257.8    32.5
  5447.8    34.3  5477.8    36.3  5547.8    36.4  5577.8      34  5687.5    33.8
  5957.5    34.3  5997.5    35.6  6433.6    34.8  6871.7    36.9  7948.6    37.4
#Mann= 4 , 1 , 0
    3290     .06       0  4359.1      .1       0  4929.8     .04       0
  5051.9      .1       0
Bank Sta=4929.8,5051.9
XS Rating Curve= 0 ,0
Exp/Cntr=0.5,0.3

Type RM Length L Ch R = 1 ,14860.6 ,113,113,113
BEGIN DESCRIPTION:
Upstream Section of Bridge/Culvert/Weir
END DESCRIPTION:
XS GIS Cut Line= 6
      3152133.84     13805118.56      3153767.12     13805226.54
      3154844.34     13804842.71      3155943.84     13803858.22
      3156526.71     13803631.92      3157566.21     13803631.92
#Sta/Elev= 30
  1660.9   39.64  2300.1   37.24  2382.4   36.94  2401.6   36.96  2675.9   37.21
  3298.6   33.99  3766.3   33.57  4193.6   33.04  4223.6   31.44  4373.6   32.88
  4415.1   31.69  4661.3   35.01  4786.9   34.19 4854.23   35.35 4946.23   32.15
 4984.35   26.02 4993.41   22.76 5010.49   23.71  5013.1   26.58 5039.76   31.86
 5050.79   33.19  5347.2   32.45  5608.8   35.17  5732.9   33.78  6461.8   35.77
  6541.8   34.55  6669.5   36.55  6749.5   34.95  6809.5   36.54  7585.1   37.04
#Mann= 7 , 1 , 0
  1660.9      .1       0  2300.1     .06       0  2382.4      .1       0
  2401.6     .06       0  3766.3      .1       0 4946.23     .04       0
 5039.76      .1       0
#XS Ineff= 2 , 0
       0  4946.6    32.4    5041       0    32.3
Permanent Ineff=
       F       F
Bank Sta=4946.23,5039.76
XS Rating Curve= 0 ,0
Exp/Cntr=0.5,0.3

Type RM Length L Ch R = 3 ,14804.1 ,,,
BEGIN DESCRIPTION:
AIRPORT ROAD, SKEW ANGLE OF 40 DEGREES
Structure ID: C61-11
END DESCRIPTION:
Bridge Culvert--1,0,-1,-1, 0
Deck Dist Width WeirC Skew NumUp NumDn MinLoCord MaxHiCord MaxSubmerge Is_Ogee
10,93,2.6,0, 60, 60, , , 0.95, 0, 1,1,,
  1660.9  2380.9  2675.9  2895.9  3283.6  3298.6  3788.6  3938.6  4108.6  4193.6
  4223.6  4238.6  4373.6  4415.1  4450.1  4500.1  4535.1  4661.3  4756.2  4781.2
  4786.9  4831.4 4854.23  4885.9 4925.89    4926 4937.88 4953.34 4953.43 5033.13
 5033.24 5039.76 5050.79  5055.4 5055.51  5188.1  5258.2  5347.2  5548.8  5608.8
  5623.8  5653.8  5732.9  5762.9  5867.9  5902.9  6002.9  6118.5  6353.5  6383.5
  6461.8  6541.8  6581.8  6669.5  6714.5  6749.5  6779.5  6794.5  6809.5  7585.1
   39.63   36.93    37.2   35.46   34.49   33.98   33.54   32.51   33.23   33.03
   31.43    32.5   32.87   31.68   32.41    32.6   33.25   35.01    35.1   34.67
   34.68   35.23   35.35   34.77   35.38   36.88   36.53   36.06   36.06   35.96
   35.96   36.15   36.48   36.61   35.11   32.88   32.33   32.45   33.84   35.16
   34.92   33.77   33.77   34.48   35.05   34.23   34.15   35.38    35.5   34.73
   35.76   34.54   35.82   36.54   36.19   34.94   35.06   36.06   36.53   37.03
   39.63   36.93    37.2   35.46   34.49   33.98   33.54   32.51   33.23   33.03
   31.43    32.5   32.87   31.68   32.41   31.95   33.24      35   35.09   34.58
   34.18   35.22   35.34   34.76   33.59   33.58   33.17   31.17   32.06   31.96
   30.45   31.85   33.18   33.12   33.11   32.22   32.32   32.44   33.84   35.16
   34.92   33.77   33.77   34.48   35.05   34.23   34.15   35.38    35.5   34.73
   35.76   34.54   35.82   36.54   36.19   34.94   35.06   36.06   36.53   37.03
  1660.9  2380.9  2675.9  2895.9  3283.6  3298.6  3788.6  3938.6  4108.6  4193.6
  4223.6  4238.6  4373.6  4415.1  4450.1  4500.1  4535.1  4661.3  4756.2  4781.2
  4786.9  4831.4 4854.23  4885.9 4925.89    4926 4937.88 4953.34 4953.43 5033.13
 5033.24 5039.76 5050.79  5055.4 5055.51  5188.1  5258.2  5347.2  5548.8  5608.8
  5623.8  5653.8  5732.9  5762.9  5867.9  5902.9  6002.9  6118.5  6353.5  6383.5
  6461.8  6541.8  6581.8  6669.5  6714.5  6749.5  6779.5  6794.5  6809.5  7585.1
   39.63   36.93    37.2   35.46   34.49   33.98   33.54   32.51   33.23   33.03
   31.43    32.5   32.87   31.68   32.41    32.6   33.25   35.01    35.1   34.67
   34.68   35.23   35.35   34.77   35.38   36.88   36.53   36.06   36.06   35.96
   35.96   36.15   36.48   36.61   35.11   32.88   32.33   32.45   33.84   35.16
   34.92   33.77   33.77   34.48   35.05   34.23   34.15   35.38    35.5   34.73
   35.76   34.54   35.82   36.54   36.19   34.94   35.06   36.06   36.53   37.03
   39.38   36.68   36.95   35.21   34.24   33.73   33.29   32.26   32.98   32.78
   31.18   32.25   32.62   31.43   32.16    31.7   32.99   34.75   34.84   34.33
   33.93   34.97   35.09   34.51   33.34   33.33   32.92   30.92   31.81   31.71
    30.2    31.6   32.93   32.87   32.86   31.97   32.07   32.19   33.59   34.91
   34.67   33.52   33.52   34.23    34.8   33.98    33.9   35.13   35.25   34.48
   35.51   34.29   35.57   36.29   35.94   34.69   34.81   35.81   36.28   36.78
Pier Skew, UpSta & Num, DnSta & Num=  ,4972.8, 2 ,4972.8, 2 , 0 , 0 , 0 ,,
     1.5     1.5
   26.27   32.91
     1.5     1.5
   26.02   32.66
Pier Skew, UpSta & Num, DnSta & Num=  ,5013.1, 2 ,5013.1, 2 , 0 , 0 , 0 ,,
     1.5     1.5
   25.23   32.82
     1.5     1.5
   24.98   32.57
Abutment Skew #Up #Dn= , 2 , 2
 4953.23 4984.45
   32.06   25.97
 4953.23 4984.45
   31.81   25.72
Abutment Skew #Up #Dn= , 2 , 2
 5012.18 5033.33
   26.15   31.96
 5012.18 5033.33
    25.9   31.71
BR Coef= 1 , 1 , 0 ,1.25, 0 ,,,0.8,0,2,0,
WSPro=,,,, 1 ,,,, 0 ,,,, 0 ,,,,-1 ,-1 ,-1 , 0 , 0 , 0 , 0 , 0
BR U #Sta/Elev= 110
  1660.9   39.63  2300.1   37.23  2380.9   36.93  2382.4   36.93  2401.6   36.95
  2675.9    37.2  2895.9   35.46  3060.9   34.89  3163.6   34.73  3283.6   34.49
  3298.6   33.98  3766.3   33.56  3788.6   33.54  3938.6   32.51  4108.6   33.23
  4163.6   33.09  4193.6   33.03  4218.6    31.5  4223.6   31.43  4238.6    32.5
  4373.6   32.87  4375.1   32.83  4415.1   31.68  4435.1   31.89  4450.1   32.41
  4465.6   32.27  4500.1   31.95  4535.1   33.24  4541.3   33.32  4661.3      35
  4713.1   35.05  4756.2   35.09  4772.7   34.75  4781.2   34.58  4786.9   34.18
  4829.8   35.18  4831.4   35.22 4854.23   35.34  4885.9   34.76 4899.04   34.52
 4925.89   33.59    4926   33.58 4926.11   33.58 4937.88   33.17 4946.23   32.14
 4953.34   31.17 4953.43   31.16  4957.5   30.61 4966.37    29.4 4972.81   27.36
 4984.35   26.01 4984.45   25.97 4988.13   24.51 4993.41   22.75 5000.77   23.57
 5010.49    23.7 5011.87   24.39 5012.08   25.58 5012.18   26.15  5013.1   26.57
  5027.4    29.2  5027.5   29.22 5033.13   30.43 5033.24   30.45 5039.76   31.85
 5050.79   33.18 5055.29   33.12  5055.4   33.12 5055.51   33.11 5083.19   32.73
 5117.73   32.62  5134.4   32.62 5156.65   32.62  5188.1   32.22 5192.42   32.17
  5192.5   32.17    5241   32.28  5258.2   32.32    5278   32.35  5341.8   32.43
  5347.2   32.44  5457.2   33.17  5529.7    33.7  5548.8   33.84  5608.8   35.16
  5623.8   34.92  5653.8   33.77  5732.9   33.77  5762.9   34.48  5867.9   35.05
  5902.9   34.23  6002.9   34.15  6077.9   34.78  6087.9   35.26  6118.5   35.38
  6353.5    35.5  6383.5   34.73  6416.8   35.38  6461.8   35.76  6541.8   34.54
  6581.8   35.82  6669.5   36.54  6714.5   36.19  6749.5   34.94  6779.5   35.06
  6794.5   36.06  6809.5   36.53  7214.5   37.01  7229.5   36.69  7585.1   37.03
BR U #Mann= 7
  1660.9      .1  2300.1     .06  2382.4      .1  2401.6     .06  3766.3      .1
 4946.23     .04 5039.76      .1
BR U Banks=4946.23,5039.76
BR D #Sta/Elev= 110
  1660.9   39.38  2300.1   36.98  2380.9   36.68  2382.4   36.68  2401.6    36.7
  2675.9   36.95  2895.9   35.21  3060.9   34.64  3163.6   34.48  3283.6   34.24
  3298.6   33.73  3766.3   33.31  3788.6   33.29  3938.6   32.26  4108.6   32.98
  4163.6   32.84  4193.6   32.78  4218.6   31.25  4223.6   31.18  4238.6   32.25
  4373.6   32.62  4375.1   32.58  4415.1   31.43  4435.1   31.64  4450.1   32.16
  4465.6   32.02  4500.1    31.7  4535.1   32.99  4541.3   33.07  4661.3   34.75
  4713.1    34.8  4756.2   34.84  4772.7    34.5  4781.2   34.33  4786.9   33.93
  4829.8   34.93  4831.4   34.97 4854.23   35.09  4885.9   34.51 4899.04   34.27
 4925.89   33.34    4926   33.33 4926.11   33.33 4937.88   32.92 4946.23   31.89
 4953.34   30.92 4953.43   30.91  4957.5   30.36 4966.37   29.15 4972.81   27.11
 4984.35   25.76 4984.45   25.72 4988.13   24.26 4993.41    22.5 5000.77   23.32
 5010.49   23.45 5011.87   24.14 5012.08   25.33 5012.18    25.9  5013.1   26.32
  5027.4   28.95  5027.5   28.97 5033.13   30.18 5033.24    30.2 5039.76    31.6
 5050.79   32.93 5055.29   32.87  5055.4   32.87 5055.51   32.86 5083.19   32.48
 5117.73   32.37  5134.4   32.37 5156.65   32.37  5188.1   31.97 5192.42   31.92
  5192.5   31.92    5241   32.03  5258.2   32.07    5278    32.1  5341.8   32.18
  5347.2   32.19  5457.2   32.92  5529.7   33.45  5548.8   33.59  5608.8   34.91
  5623.8   34.67  5653.8   33.52  5732.9   33.52  5762.9   34.23  5867.9    34.8
  5902.9   33.98  6002.9    33.9  6077.9   34.53  6087.9   35.01  6118.5   35.13
  6353.5   35.25  6383.5   34.48  6416.8   35.13  6461.8   35.51  6541.8   34.29
  6581.8   35.57  6669.5   36.29  6714.5   35.94  6749.5   34.69  6779.5   34.81
  6794.5   35.81  6809.5   36.28  7214.5   36.76  7229.5   36.44  7585.1   36.78
BR D #Mann= 7
  1660.9      .1  2300.1     .06  2382.4      .1  2401.6     .06  3766.3      .1
 4946.23     .04 5039.76      .1
BR D Banks=4946.23,5039.76
BC Design=,, 0 ,, 0 ,,,,,,
BC HTab HWMax=39.64
BC Use User HTab Curves=0
BC User HTab FreeFlow(D)= 0

Type RM Length L Ch R = 1 ,14747.6 ,292.9,389.2,461.2
BEGIN DESCRIPTION:
Downstream Section of Bridge/Culvert/Weir
END DESCRIPTION:
XS GIS Cut Line= 6
      3152134.82     13805231.56       3153768.1     13805339.54
      3154845.32     13804955.71      3155944.82     13803971.22
      3156527.69     13803744.92       3157567.2     13803744.92
#Sta/Elev= 30
  1660.9   39.37  2300.1   36.97  2382.4   36.67  2401.6   36.69  2675.9   36.94
  3298.6   33.72  3766.3    33.3  4193.6   32.77  4223.6   31.17  4373.6   32.61
  4415.1   31.42  4661.3   34.74  4786.9   33.92 4854.23   35.08 4946.23   31.88
 4984.35   25.75 4993.41   22.49 5010.49   23.44  5013.1   26.31 5039.76   31.59
 5050.79   32.92  5347.2   32.18  5608.8    34.9  5732.9   33.51  6461.8    35.5
  6541.8   34.28  6669.5   36.28  6749.5   34.68  6809.5   36.27  7585.1   36.77
#Mann= 7 , 1 , 0
  1660.9      .1       0  2300.1     .06       0  2382.4      .1       0
  2401.6     .06       0  3766.3      .1       0 4946.23     .04       0
 5039.76      .1       0
#XS Ineff= 2 , 0
       0  4946.6    32.4    5041       0    32.3
Permanent Ineff=
       F       F
Bank Sta=4946.23,5039.76
XS Rating Curve= 0 ,0
Exp/Cntr=0.5,0.3

Type RM Length L Ch R = 1 ,14358.4 ,301.6,504.1,472.1
BEGIN DESCRIPTION:
Cross Section 14358.4-Interpolated
END DESCRIPTION:
XS GIS Cut Line= 6
      3152206.04     13805265.95      3153767.61      13805382.1
      3154324.79     13805307.81      3155032.73     13804979.75
      3156539.57     13805026.53      3157063.28     13804988.74
#Sta/Elev= 30
  1895.3    39.9  2511.7   36.93  2566.9   36.66  2601.8   36.55  3145.3    35.4
  3230.3    33.6  3799.7    33.8  4238.6   32.61  4636.3   32.45  4938.6    33.4
  4958.6    31.6  4973.6    28.6  4991.2    23.3  4999.8   22.27  5008.9   23.33
  5018.6    29.7  5033.6    31.8  5063.6      33  5143.1    33.2  5168.1    32.1
  5653.1    33.9  5718.1    32.7  5768.1    35.8  5873.1    36.5  5903.1    35.1
  6311.2    35.3  6396.2    34.4  6446.2    35.4  6801.2    35.8  6836.2    37.1
#Mann= 10 , 1 , 0
  1895.3      .2       0  1895.3      .1       0  2511.7     .06       0
  2566.9      .1       0  2601.8     .06       0  3799.7      .1       0
  4238.6     .06       0  4636.3      .1       0  4958.6     .04       0
  5033.6      .1       0
Bank Sta=4958.6,5033.6
XS Rating Curve= 0 ,0
Exp/Cntr=0.3,0.1

Type RM Length L Ch R = 1 ,13854.3 ,53,63.9,65
BEGIN DESCRIPTION:
Cross Section 13854.3-Interpolated
END DESCRIPTION:
XS GIS Cut Line= 6
       3152244.3     13805365.24      3153779.99     13805444.01
      3155327.72     13805419.24      3155847.75     13805394.48
      3156813.54     13805196.37      3157551.94     13805184.06
#Sta/Elev= 30
  2037.2    39.7  2651.1   36.63    2671   36.53  2742.7   36.23  3701.8   33.87
  4006.9   33.52  4818.5   32.38  4835.3    32.1  4865.3    33.2  4905.3    32.6
  4935.3    33.1  4945.3    32.7  4955.6    31.7  4965.6      30  4981.7   23.63
  4999.8   21.97  5008.9   23.03  5018.5   31.87  5045.6      33  5125.1    32.6
  5275.1    32.8  5648.4    35.6  5798.4    33.5  5818.4    34.4  6128.4    36.2
  6465.6    34.8  6505.6    35.3  6545.6    38.7  6634.4    39.6  7368.9    38.7
#Mann= 11 , 1 , 0
  2037.2      .2       0  2037.2      .1       0  2651.1     .06       0
    2671      .1       0  2742.7     .06       0  3701.8      .1       0
  4006.9     .06       0  4818.5      .1       0  4955.6     .04       0
  5018.5      .1       0  7368.9      .2       0
Bank Sta=4955.6,5018.5
XS Rating Curve= 0 ,0
Exp/Cntr=0.5,0.3

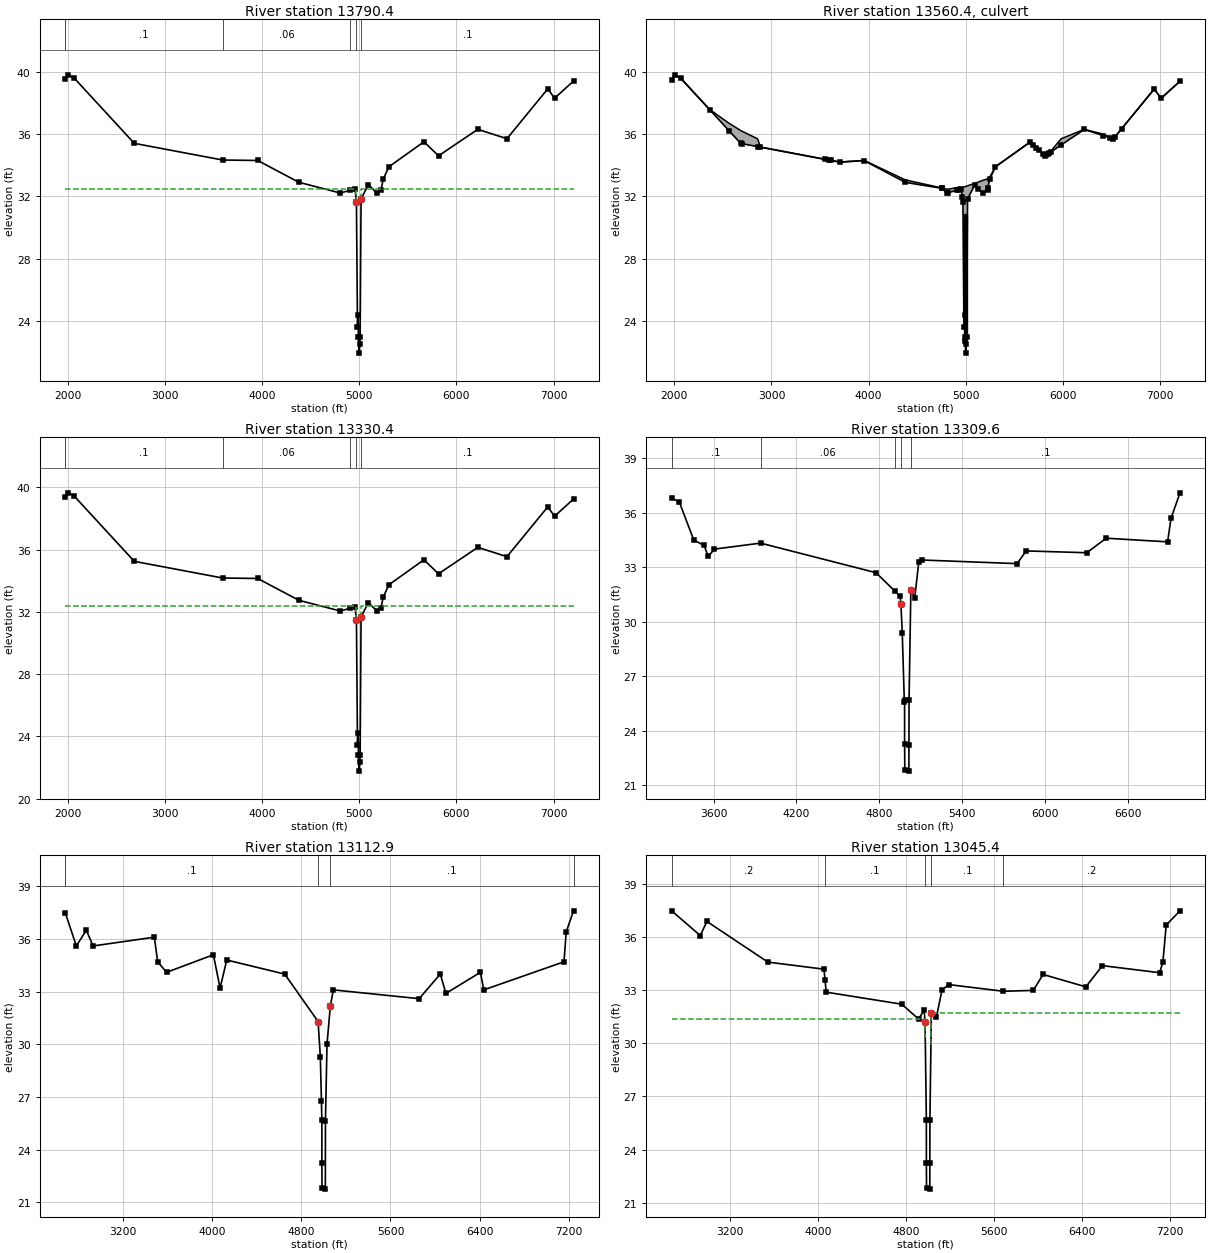
Type RM Length L Ch R = 1 ,13790.4 ,460,460,460
BEGIN DESCRIPTION:
Upstream Section of Bridge/Culvert/Weir
END DESCRIPTION:
XS GIS Cut Line= 6
      3152126.18      13805477.1      3153460.14     13805535.94
      3154017.32     13805474.04      3155280.26     13805486.42
      3156694.77     13805264.31      3157335.07     13805252.15
#Sta/Elev= 30
  1972.6   39.51  2003.8   39.81  2063.8   39.61  2683.8   35.41  3593.3   34.34
  3954.2   34.31  4378.2   32.91  4805.5   32.22  4905.2    32.4  4955.9   32.49
  4970.9   31.63  4981.7    23.6  4988.3   24.38  4991.2   22.97  4999.8   21.94
  5006.9   22.53  5008.9      23  5018.5   31.84    5094   32.76  5181.5   32.22
    5225   32.44    5246   33.11    5306   33.91  5665.9   35.51  5815.9   34.61
  6220.5   36.31  6520.5   35.71  6940.8   38.91  7010.8   38.31  7205.9   39.41
#Mann= 6 , 1 , 0
  1972.6      .2       0  1972.6      .1       0  3593.3     .06       0
  4905.2      .1       0  4970.9    .015       0  5018.5      .1       0
#XS Ineff= 2 , 0
       0    4969    32.5    5020       0    32.5
Permanent Ineff=
       F       F
Bank Sta=4970.9,5018.5
XS Rating Curve= 0 ,0
Exp/Cntr=0.5,0.3

Type RM Length L Ch R = 2 ,13560.4 ,,,
BEGIN DESCRIPTION:
MONROE STREET CULVERT
Structure ID: C61-10
END DESCRIPTION:
Bridge Culvert--1,0,-1,-1, 0
Deck Dist Width WeirC Skew NumUp NumDn MinLoCord MaxHiCord MaxSubmerge Is_Ogee
10,440,3,0, 59, 59, , , 0.95, 0, 1,1,,
  1972.6  2003.8  2063.8  2362.6  2562.6  2683.8  2692.6  2856.9  2886.9  3549.4
  3593.3    3611  3704.1  3954.2  4378.2  4755.8  4755.9  4805.5  4815.7  4905.2
    4928  4955.9  4965.5  4970.9  4981.7  4988.3  4991.2    4994  4999.8  5006.9
  5008.9  5018.5    5094  5129.5  5181.5    5225  5228.9    5246    5306  5665.9
  5695.5  5725.5  5755.5  5795.5  5815.9  5825.5  5845.5  5855.5  5875.5  5981.7
  6220.5    6415    6485  6520.5    6535    6605  6940.8  7010.8  7205.9
    39.5   39.81   39.61   37.59    36.7   36.23    36.2    35.7   35.17   34.39
   34.34   34.32   34.21   34.31   33.06   32.54   32.54   32.47   32.46   32.56
   32.59   32.57   32.56   32.57    32.6   32.61   32.62   32.62   32.64   32.65
   32.66   32.68   32.84   32.92   33.04   33.13   33.14   33.22   33.91   35.51
    35.4   35.15   34.97   34.73   34.61   34.65   34.73   34.78    34.9    35.7
   36.31      36   35.78   35.71   35.82   36.35    38.9    38.3    39.4
    39.5    39.8    39.6   37.58   36.22    35.4   35.39    35.2   35.16   34.38
   34.33   34.31    34.2    34.3    32.9   32.52   32.52   32.21   32.23   32.39
   32.43   32.48   31.93   31.62   23.59   24.37   22.96   22.73   21.93   22.52
   22.99   31.83   32.75   32.45   32.21   32.43   32.55    33.1    33.9    35.5
   35.32   35.14   34.96   34.72    34.6   34.64   34.72   34.77   34.85    35.3
    36.3   35.91   35.77    35.7   35.81   36.34    38.9    38.3    39.4
  1972.6  2003.8  2063.8  2362.6  2562.6  2683.8  2692.6  2856.9  2886.9  3549.4
  3593.3    3611  3704.1  3954.2  4378.2  4755.8  4755.9  4805.5  4815.7  4905.2
    4928  4955.9  4965.5  4970.9  4981.7  4988.3  4991.2    4994  4999.8  5006.9
  5008.9  5018.5    5094  5129.5  5181.5    5225  5228.9    5246    5306  5665.9
  5695.5  5725.5  5755.5  5795.5  5815.9  5825.5  5845.5  5855.5  5875.5  5981.7
  6220.5    6415    6485  6520.5    6535    6605  6940.8  7010.8  7205.9
    39.5   39.81   39.61   37.59    36.7   36.23    36.2    35.7   35.17   34.39
   34.34   34.32   34.21   34.31   33.06   32.54   32.54   32.47   32.46   32.56
   32.59   32.57   32.56   32.57    32.6   32.61   32.62   32.62   32.64   32.65
   32.66   32.68   32.84   32.92   33.04   33.13   33.14   33.22   33.91   35.51
    35.4   35.15   34.97   34.73   34.61   34.65   34.73   34.78    34.9    35.7
   36.31      36   35.78   35.71   35.82   36.35    38.9    38.3    39.4
   39.34   39.64   39.44   37.42   36.06   35.24   35.23   35.04      35   34.22
   34.17   34.15   34.04   34.14   32.74   32.36   32.36   32.05   32.07   32.23
   32.27   32.32   31.77   31.46   23.43   24.21    22.8   22.57   21.77   22.36
   22.83   31.67   32.59   32.29   32.05   32.27   32.39   32.94   33.74   35.34
   35.16   34.98    34.8   34.56   34.44   34.48   34.56   34.61   34.69   35.14
   36.14   35.75   35.61   35.54   35.65   36.18   38.74   38.14   39.24
BR Coef= 1 , 0 , 0 ,1.25, 0 ,,,0.8,-1,2,0,
WSPro=,,,, 1 ,,,, 0 ,,,, 0 ,,,,-1 ,-1 ,-1 , 0 , 0 , 0 , 0 , 0
Culvert=2,8,10,440,0.015,0.4,1,8,1,22.86,4984,21.65,4984,Culvert #1  , 0 ,10
Culvert Bottom n=0.015
Culvert=2,8,10,440,0.015,0.4,1,8,1,22.86,4994.9,21.65,4994.9,Culvert #2  , 0 ,10
Culvert Bottom n=0.015
Culvert=2,8,10,440,0.015,0.4,1,8,1,22.86,5005.2,21.65,5005.2,Culvert #3  , 0 ,10
Culvert Bottom n=0.015
BR U #Sta/Elev= 59
  1972.6    39.5  2003.8    39.8  2063.8    39.6  2362.6   37.58  2562.6   36.22
  2683.8    35.4  2692.6   35.39  2856.9    35.2  2886.9   35.16  3549.4   34.38
  3593.3   34.33    3611   34.31  3704.1    34.2  3954.2    34.3  4378.2    32.9
  4755.8   32.52  4755.9   32.52  4805.5   32.21  4815.7   32.23  4905.2   32.39
    4928   32.43  4955.9   32.48  4965.5   31.93  4970.9   31.62  4981.7   23.59
  4988.3   24.37  4991.2   22.96    4994   22.73  4999.8   21.93  5006.9   22.52
  5008.9   22.99  5018.5   31.83    5094   32.75  5129.5   32.45  5181.5   32.21
    5225   32.43  5228.9   32.55    5246    33.1    5306    33.9  5665.9    35.5
  5695.5   35.32  5725.5   35.14  5755.5   34.96  5795.5   34.72  5815.9    34.6
  5825.5   34.64  5845.5   34.72  5855.5   34.77  5875.5   34.85  5981.7    35.3
  6220.5    36.3    6415   35.91    6485   35.77  6520.5    35.7    6535   35.81
    6605   36.34  6940.8    38.9  7010.8    38.3  7205.9    39.4
BR U #Mann= 6
  1972.6      .2  1972.6      .1  3593.3     .06  4905.2      .1  4970.9    .015
  5018.5      .1
BR U Banks=4970.9,5018.5
BR D #Sta/Elev= 59
  1972.6   39.34  2003.8   39.64  2063.8   39.44  2362.6   37.42  2562.6   36.06
  2683.8   35.24  2692.6   35.23  2856.9   35.04  2886.9      35  3549.4   34.22
  3593.3   34.17    3611   34.15  3704.1   34.04  3954.2   34.14  4378.2   32.74
  4755.8   32.36  4755.9   32.36  4805.5   32.05  4815.7   32.07  4905.2   32.23
    4928   32.27  4955.9   32.32  4965.5   31.77  4970.9   31.46  4981.7   23.43
  4988.3   24.21  4991.2    22.8    4994   22.57  4999.8   21.77  5006.9   22.36
  5008.9   22.83  5018.5   31.67    5094   32.59  5129.5   32.29  5181.5   32.05
    5225   32.27  5228.9   32.39    5246   32.94    5306   33.74  5665.9   35.34
  5695.5   35.16  5725.5   34.98  5755.5    34.8  5795.5   34.56  5815.9   34.44
  5825.5   34.48  5845.5   34.56  5855.5   34.61  5875.5   34.69  5981.7   35.14
  6220.5   36.14    6415   35.75    6485   35.61  6520.5   35.54    6535   35.65
    6605   36.18  6940.8   38.74  7010.8   38.14  7205.9   39.24
BR D #Mann= 6
  1972.6      .2  1972.6      .1  3593.3     .06  4905.2      .1  4970.9    .015
  5018.5      .1
BR D Banks=4970.9,5018.5
BC Design=,, 0 ,, 0 ,,,,,,
BC HTab HWMax=39.81
BC Use User HTab Curves=0
BC User HTab FreeFlow(D)= 0

Type RM Length L Ch R = 1 ,13330.4 ,20.7,20.8,20.9
BEGIN DESCRIPTION:
Downstream Section of Bridge/Culvert/Weir
END DESCRIPTION:
XS GIS Cut Line= 6
      3152122.05     13805937.08        3153456.     13805995.92
      3154013.18     13805934.02      3155276.12      13805946.4
      3156690.63     13805724.29      3157330.94     13805712.13
#Sta/Elev= 30
  1972.6   39.34  2003.8   39.64  2063.8   39.44  2683.8   35.24  3593.3   34.17
  3954.2   34.14  4378.2   32.74  4805.5   32.05  4905.2   32.23  4955.9   32.32
  4970.9   31.46  4981.7   23.43  4988.3   24.21  4991.2    22.8  4999.8   21.77
  5006.9   22.36  5008.9   22.83  5018.5   31.67    5094   32.59  5181.5   32.05
    5225   32.27    5246   32.94    5306   33.74  5665.9   35.34  5815.9   34.44
  6220.5   36.14  6520.5   35.54  6940.8   38.74  7010.8   38.14  7205.9   39.24
#Mann= 6 , 1 , 0
  1972.6      .2       0  1972.6      .1       0  3593.3     .06       0
  4905.2      .1       0  4970.9    .015       0  5018.5      .1       0
#XS Ineff= 2 , 0
       0    4969    32.4    5020       0    32.4
Permanent Ineff=
       F       F
Bank Sta=4970.9,5018.5
XS Rating Curve= 0 ,0
Exp/Cntr=0.5,0.3

Type RM Length L Ch R = 1 ,13309.6 ,207.9,196.7,188.7
BEGIN DESCRIPTION:
Cross Section 13309.6-Interpolated
END DESCRIPTION:
XS GIS Cut Line= 5
      3153434.55     13806031.62      3153434.56     13806031.62
      3154915.27     13806013.67      3155247.31     13806031.62
      3157114.16     13806139.17
#Sta/Elev= 30
  3296.5    36.8  3351.5    36.6  3456.5    34.5  3531.5    34.2  3561.5    33.6
  3606.5      34  3940.3   34.33  4777.3    32.7  4911.8    31.7  4952.3    31.4
  4957.3      31  4967.3    29.4  4982.3    25.6  4984.2   25.69  4984.3   23.25
  4985.8   21.83  5015.5   21.77  5015.7   23.23  5016.5   25.67  5029.6   31.75
  5057.3    31.3  5087.3    33.3  5107.3    33.4  5799.8    33.2  5864.8    33.9
  6304.8    33.8  6444.8    34.6  6889.8    34.4  6914.8    35.7  6979.8    37.1
#Mann= 5 , 1 , 0
  3296.5      .1       0  3940.3     .06       0  4911.8      .1       0
  4957.3     .04       0  5029.6      .1       0
Bank Sta=4957.3,5029.6
XS Rating Curve= 0 ,0
Exp/Cntr=0.3,0.1

Type RM Length L Ch R = 1 ,13112.9 ,55.8,67.5,47.8
BEGIN DESCRIPTION:
Cross Section 13112.9-Interpolated
END DESCRIPTION:
XS GIS Cut Line= 4
      3152806.15     13806100.38       3155067.7     13806174.53
      3155228.66     13806174.53      3157365.25     13806273.34
#Sta/Elev= 30
  2680.6    37.5  2780.6    35.6  2870.6    36.5  2930.6    35.6  3480.6    36.1
  3510.6    34.7  3590.6    34.1  4010.6    35.1  4070.6    33.2  4130.6    34.8
  4650.6      34  4950.4    31.3  4970.4    29.3  4980.4    26.8  4984.2   25.68
  4984.3   23.24  4985.8   21.82  5015.5   21.76  5016.5   25.66  5030.4      30
  5060.4    32.2  5087.5    33.1  5857.5    32.6  6047.5      34  6097.5    32.9
  6407.5    34.1  6437.5    33.1  7157.5    34.7  7177.5    36.4  7243.2    37.6
#Mann= 5 , 1 , 0
  2680.6      .2       0  2680.6      .1       0  4950.4     .04       0
  5060.4      .1       0  7243.2      .2       0
Bank Sta=4950.4,5060.4
XS Rating Curve= 0 ,0
Exp/Cntr=0.5,0.3

Type RM Length L Ch R = 1 ,13045.4 ,81.6,81.6,81.6
BEGIN DESCRIPTION:
Upstream Section of Bridge/Culvert/Weir
END DESCRIPTION:
XS GIS Cut Line= 5
      3152796.04     13806203.35      3154685.44     13806270.35
      3155238.03       13806306.      3155431.15       13806306.
      3157412.98     13806351.71
#Sta/Elev= 30
  2669.5    37.5  2929.5    36.1  2989.5    36.9  3543.8    34.6  4053.8    34.2
  4063.5   33.57  4073.8    32.9  4759.9   32.22  4913.9   31.38  4963.8   31.89
  4972.3   31.22  4984.2   25.68  4984.3   23.24  4985.8   21.82  5015.5   21.76
  5015.7   23.22  5016.5   25.66  5029.6   31.74  5074.9   31.47    5126   33.01
  5185.9   33.33    5685   32.95  5955.2      33  6045.2    33.9  6433.9    33.2
  6583.9    34.4  7103.9      34  7133.9    34.6  7163.9    36.7  7289.3    37.5
#Mann= 5 , 1 , 0
  2669.5      .2       0  4063.5      .1       0  4972.3    .015       0
  5029.6      .1       0    5685      .2       0
#XS Ineff= 2 , 0
       0  4974.3    31.4  5025.6       0    31.7
Permanent Ineff=
       F       F
Bank Sta=4972.3,5029.6
XS Rating Curve= 0 ,0
Exp/Cntr=0.5,0.3