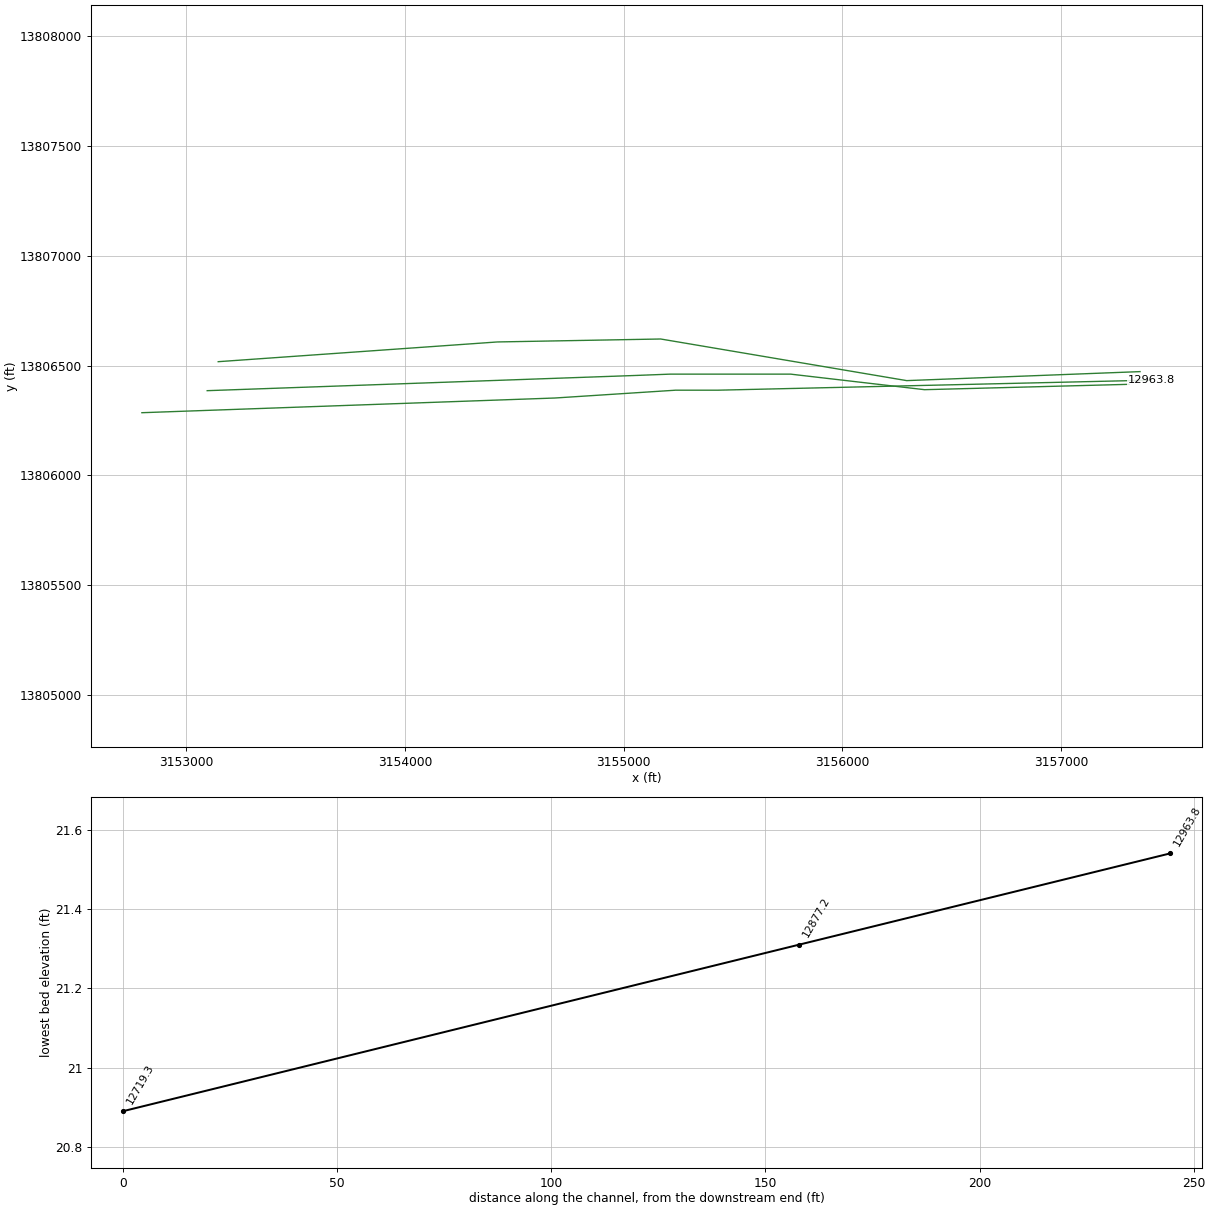
HEC-RAS study C106-01-00.PRJ: C106-01-00

--- C106-01-00.g01 (geometry) --- (continued)

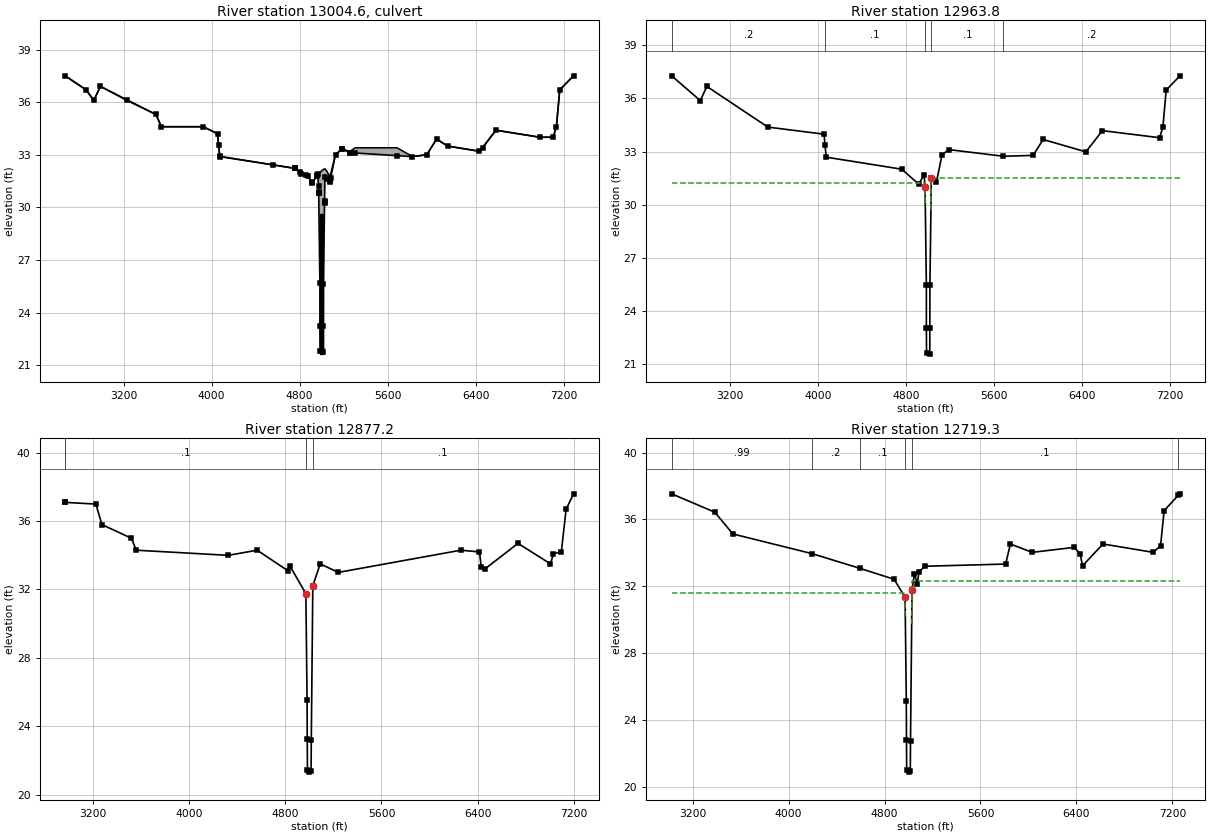
Type RM Length L Ch R = 2 ,13004.6 ,,,
BEGIN DESCRIPTION:
WYNLEA ROAD
Structure ID: C61-9
END DESCRIPTION:
Bridge Culvert--1,0,-1,-1, 0
Deck Dist Width WeirC Skew NumUp NumDn MinLoCord MaxHiCord MaxSubmerge Is_Ogee
10,61.6,3,0, 40, 40, , , 0.95, 0, 1,1,,
  2669.5  2859.5  2929.5  2989.5  3493.8  3543.8  3923.8  4053.8  4073.8  4759.9
  4816.1  4873.5  4913.9  4963.8  4972.3  4984.2  4984.3  4985.8  5015.5  5015.7
  5016.5  5029.6  5050.7  5074.9    5126  5185.9  5253.7  5306.9    5685  5825.2
  5955.2  6045.2  6143.9  6433.9  6583.9  6983.9  7103.9  7133.9  7163.9  7289.3
    37.5    36.7    36.1    36.9    35.3    34.6    34.6    34.2   32.91   32.23
   31.93    31.8   31.39    31.9   31.91      32      32   32.01   32.16   32.16
   32.17    32.2   32.04   31.74   33.02   33.34   33.19    33.4    33.4    32.9
      33    33.9    33.5    33.2    34.4      34      34    34.6    36.7    37.5
    37.5    36.7    36.1    36.9    35.3    34.6    34.6    34.2    32.9   32.22
   31.92   31.79   31.38   31.89   31.22   25.68   23.24   21.82   21.76   23.22
   25.66   31.74   31.61   31.47   33.01   33.33   33.13    33.1   32.95    32.9
      33    33.9    33.5    33.2    34.4      34      34    34.6    36.7    37.5
  2669.5  2859.5  2929.5  2989.5  3493.8  3543.8  3923.8  4053.8  4073.8  4759.9
  4816.1  4873.5  4913.9  4963.8  4972.3  4984.2  4984.3  4985.8  5015.5  5015.7
  5016.5  5029.6  5050.7  5074.9    5126  5185.9  5253.7  5306.9    5685  5825.2
  5955.2  6045.2  6143.9  6433.9  6583.9  6983.9  7103.9  7133.9  7163.9  7289.3
    37.5    36.7    36.1    36.9    35.3    34.6    34.6    34.2   32.91   32.23
   31.93    31.8   31.39    31.9   31.91      32      32   32.01   32.16   32.16
   32.17    32.2   32.04   31.74   33.02   33.34   33.19    33.4    33.4    32.9
      33    33.9    33.5    33.2    34.4      34      34    34.6    36.7    37.5
   37.31   36.51   35.91   36.71   35.11   34.41   34.41   34.01   32.71   32.03
   31.73    31.6   31.19    31.7   31.03   25.49   23.05   21.63   21.57   23.03
   25.47   31.55   31.42   31.28   32.82   33.14   32.94   32.91   32.76   32.71
   32.81   33.71   33.31   33.01   34.21   33.81   33.81   34.41   36.51   37.31
BR Coef= 1 , 0 , 0 ,1.25, 0 ,,,0.8,-1,2,0,
WSPro=,,,, 1 ,,,, 0 ,,,, 0 ,,,,-1 ,-1 ,-1 , 0 , 0 , 0 , 0 , 0
Culvert=2,8,10,61.6,0.015,0.4,1,8,1,21.64,4989.4,21.35,4989.4,Culvert #1  , 0 ,10
Culvert Bottom n=0.015
Culvert=2,8,10,61.6,0.015,0.4,1,8,1,21.64,5000.3,21.35,5000.3,Culvert #2  , 0 ,10
Culvert Bottom n=0.015
Culvert=2,8,10,61.6,0.015,0.4,1,8,1,21.64,5010.7,21.35,5010.7,Culvert #3  , 0 ,10
Culvert Bottom n=0.015
BR U #Sta/Elev= 63
  2669.5    37.5  2859.5    36.7  2929.5    36.1  2989.5    36.9  3229.5    36.1
  3493.8    35.3  3543.8    34.6  3923.8    34.6  4053.8    34.2  4063.5   33.57
  4073.5   32.92  4073.8    32.9  4560.1   32.42  4756.6   32.22  4759.8   32.22
  4759.9   32.22  4799.6   32.01  4816.1   31.92  4855.2   31.83  4873.5   31.79
  4908.8   31.43  4913.9   31.38  4955.1    31.8  4956.6   31.82  4963.8   31.89
  4972.3   31.22 4972.99    30.9  4973.1   30.85 4973.21    30.8  4984.2   25.68
  4984.3   23.24  4985.8   21.82  4999.9   21.82  5015.5   21.76  5015.7   23.22
  5016.5   25.66 5026.39   30.25  5026.5    30.3 5026.61   30.35  5029.6   31.74
  5050.7   31.61  5074.9   31.47  5075.4   31.49  5081.9   31.68    5126   33.01
  5185.9   33.33    5189   33.32  5253.7   33.13    5256   33.12  5306.9    33.1
    5685   32.95  5825.2    32.9  5955.2      33  6045.2    33.9  6143.9    33.5
  6433.9    33.2  6463.9    33.4  6583.9    34.4  6983.9      34  7103.9      34
  7133.9    34.6  7163.9    36.7  7289.3    37.5
BR U #Mann= 5
  2669.5      .2  4063.5      .1  4972.3    .015  5029.6      .1    5685      .2
BR U Banks=4972.3,5029.6
BR D #Sta/Elev= 63
  2669.5   37.31  2859.5   36.51  2929.5   35.91  2989.5   36.71  3229.5   35.91
  3493.8   35.11  3543.8   34.41  3923.8   34.41  4053.8   34.01  4063.5   33.38
  4073.5   32.73  4073.8   32.71  4560.1   32.23  4756.6   32.03  4759.8   32.03
  4759.9   32.03  4799.6   31.82  4816.1   31.73  4855.2   31.64  4873.5    31.6
  4908.8   31.24  4913.9   31.19  4955.1   31.61  4956.6   31.63  4963.8    31.7
  4972.3   31.03 4972.99   30.71  4973.1   30.66 4973.21   30.61  4984.2   25.49
  4984.3   23.05  4985.8   21.63  4999.9   21.63  5015.5   21.57  5015.7   23.03
  5016.5   25.47 5026.39   30.06  5026.5   30.11 5026.61   30.16  5029.6   31.55
  5050.7   31.42  5074.9   31.28  5075.4    31.3  5081.9   31.49    5126   32.82
  5185.9   33.14    5189   33.13  5253.7   32.94    5256   32.93  5306.9   32.91
    5685   32.76  5825.2   32.71  5955.2   32.81  6045.2   33.71  6143.9   33.31
  6433.9   33.01  6463.9   33.21  6583.9   34.21  6983.9   33.81  7103.9   33.81
  7133.9   34.41  7163.9   36.51  7289.3   37.31
BR D #Mann= 5
  2669.5      .2  4063.5      .1  4972.3    .015  5029.6      .1    5685      .2
BR D Banks=4972.3,5029.6
BC Design=,, 0 ,, 0 ,,,,,,
BC HTab HWMax=37.5
BC Use User HTab Curves=0
BC User HTab FreeFlow(D)= 0

Type RM Length L Ch R = 1 ,12963.8 ,86,86.6,87
BEGIN DESCRIPTION:
Downstream Section of Bridge/Culvert/Weir
END DESCRIPTION:
XS GIS Cut Line= 5
      3152796.11     13806284.95       3154685.5     13806351.95
      3155238.09      13806387.6      3155431.21      13806387.6
      3157413.04     13806433.31
#Sta/Elev= 30
  2669.5   37.28  2929.5   35.88  2989.5   36.68  3543.8   34.38  4053.8   33.98
  4063.5   33.35  4073.8   32.68  4759.9      32  4913.9   31.16  4963.8   31.67
  4972.3      31  4984.2   25.46  4984.3   23.02  4985.8    21.6  5015.5   21.54
  5015.7      23  5016.5   25.44  5029.6   31.52  5074.9   31.25    5126   32.79
  5185.9   33.11    5685   32.73  5955.2   32.78  6045.2   33.68  6433.9   32.98
  6583.9   34.18  7103.9   33.78  7133.9   34.38  7163.9   36.48  7289.3   37.28
#Mann= 5 , 1 , 0
  2669.5      .2       0  4063.5      .1       0  4972.3    .015       0
  5029.6      .1       0    5685      .2       0
#XS Ineff= 2 , 0
       0  4974.3    31.2  5025.6       0    31.5
Permanent Ineff=
       F       F
Bank Sta=4972.3,5029.6
XS Rating Curve= 0 ,0
Exp/Cntr=0.5,0.3

Type RM Length L Ch R = 1 ,12877.2 ,133.5,157.9,69.1
BEGIN DESCRIPTION:
Cross Section 12877.2-Interpolated
END DESCRIPTION:
XS GIS Cut Line= 6
      3153094.96     13806385.38      3155061.74       13806455.
      3155212.59      13806460.8      3155763.75      13806460.8
      3156376.61     13806389.92      3157312.81     13806414.39
#Sta/Elev= 30
  2972.1    37.1  2972.2    37.1  3227.1      37  3277.1    35.8  3522.1      35
  3562.1    34.3  4327.1      34  4567.1    34.3  4822.1    33.1  4837.1    33.4
  4971.7   31.76  4981.7   25.54  4983.2   23.24  4984.9   21.43    5001   21.31
  5015.1   21.38  5016.8    23.2  5029.4   32.22  5091.1    33.5  5241.1      33
  6259.2    34.3  6414.2    34.2  6429.2    33.3  6459.2    33.2  6734.2    34.7
  7004.2    33.5  7029.2    34.1  7094.2    34.2  7134.2    36.7  7195.7    37.6
#Mann= 4 , 1 , 0
  2972.1      .2       0  2972.2      .1       0  4971.7     .04       0
  5029.4      .1       0
Bank Sta=4971.7,5029.4
XS Rating Curve= 0 ,0
Exp/Cntr=0.5,0.3

Type RM Length L Ch R = 1 ,12719.3 ,81,81,81
BEGIN DESCRIPTION:
Upstream Section of Bridge/Culvert/Weir
END DESCRIPTION:
XS GIS Cut Line= 5
      3153145.35     13806517.54      3154422.61     13806607.51
      3155169.51     13806620.96      3156295.03     13806431.23
       3157362.4     13806472.28
#Sta/Elev= 30
    3026   37.53    3386   36.43    3536   35.13  4192.7   33.96  4592.7   33.08
  4880.3   32.42  4971.7   31.34  4981.7   25.12  4983.2   22.82  4984.9   21.01
    5001   20.89  5015.1   20.96  5016.8   22.78  5029.4    31.8  5049.1   32.74
  5074.6   32.14  5085.9   32.86  5137.1    33.2  5809.5   33.33  5849.5   34.53
  6030.6   34.03  6380.9   34.33  6430.9   33.93  6450.9   33.23  6620.9   34.53
  7040.9   34.03  7100.9   34.43  7130.9   36.53  7248.7   37.44    7263   37.53
#Mann= 6 , 1 , 0
    3026     .99       0  4192.7      .2       0  4592.7      .1       0
  4971.7    .015       0  5029.4      .1       0  7248.7      .2       0
#XS Ineff= 2 , 0
       0  4973.8    31.6  5026.5       0    32.3
Permanent Ineff=
       F       F
Bank Sta=4971.7,5029.4
XS Rating Curve= 0 ,0
Exp/Cntr=0.5,0.3