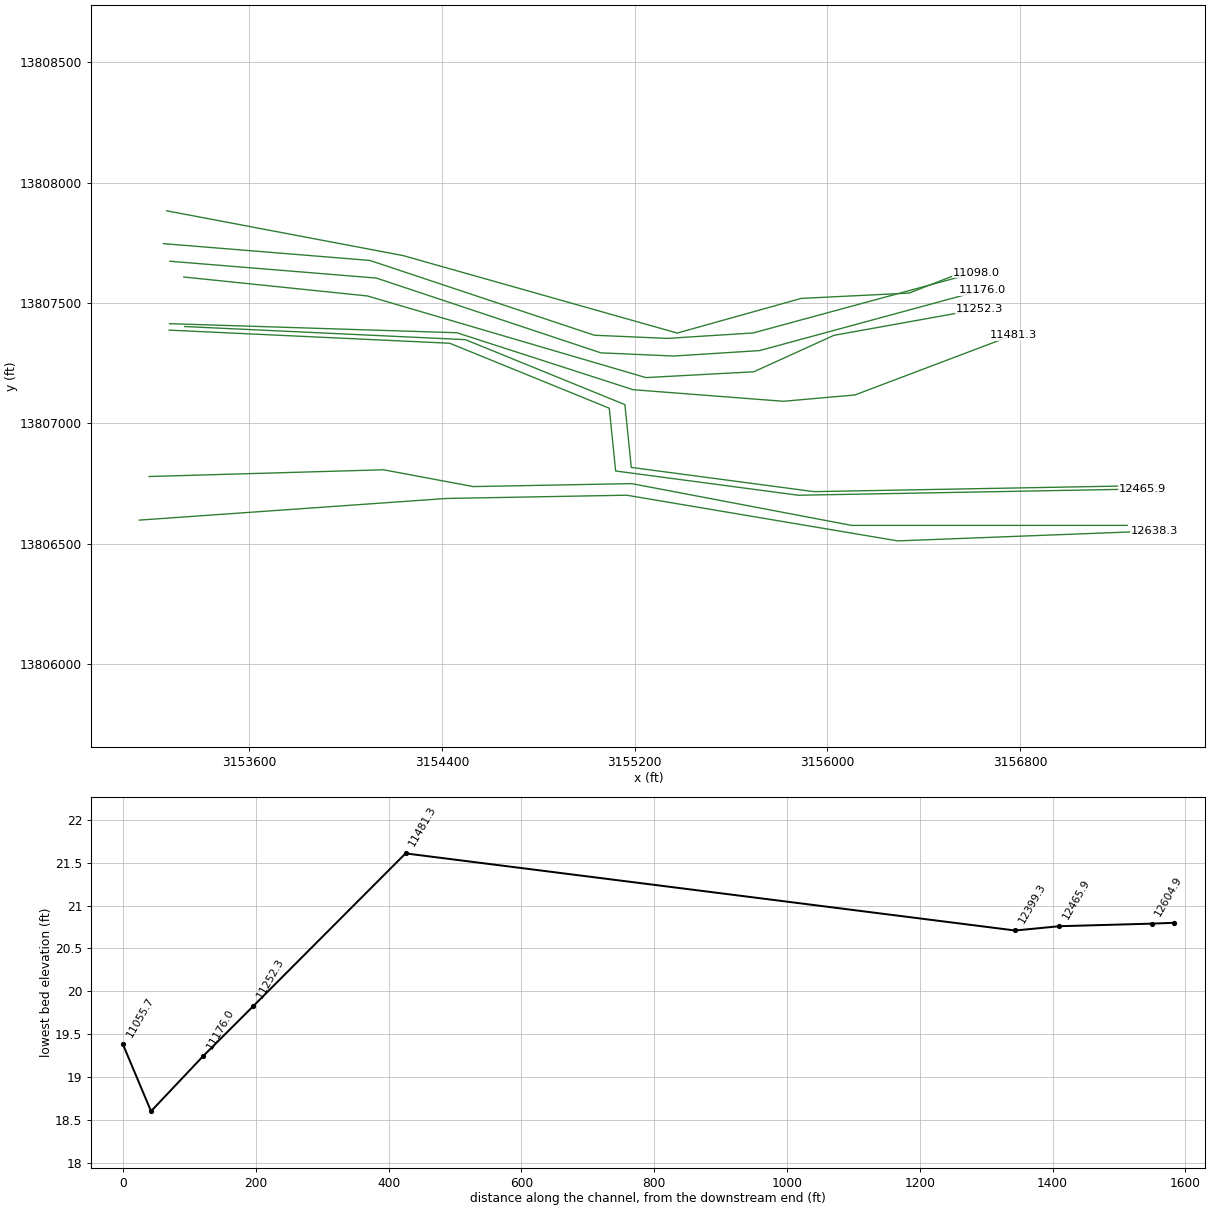
HEC-RAS study C106-01-00.PRJ: C106-01-00

--- C106-01-00.g01 (geometry) --- (continued)

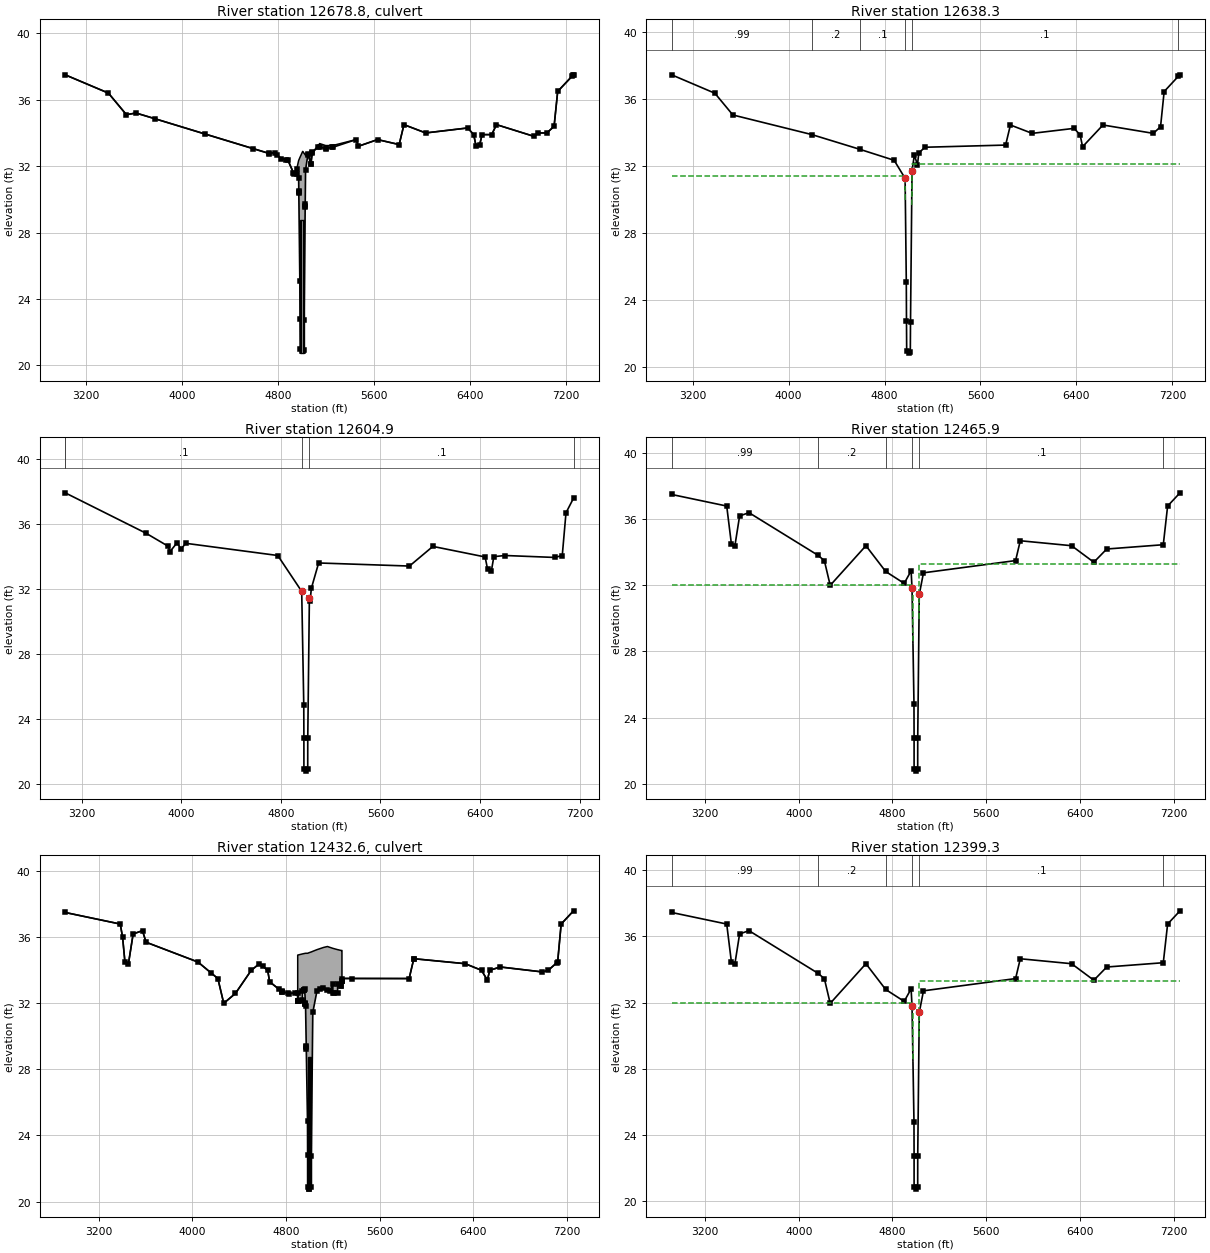
Type RM Length L Ch R = 2 ,12678.8 ,,,
BEGIN DESCRIPTION:
MEADVILLE STREET
Structure ID: C61-8
END DESCRIPTION:
Bridge Culvert--1,0,-1,-1, 0
Deck Dist Width WeirC Skew NumUp NumDn MinLoCord MaxHiCord MaxSubmerge Is_Ogee
10,61,3,0, 46, 46, , , 0.95, 0, 1,1,,
    3026    3386    3536    3616  4725.7  4772.5  4827.9  4880.3  4931.2  4955.7
  4956.5  4971.7  4981.7  4983.2  4984.9    5001  5005.6  5015.1  5016.8  5029.4
  5049.1  5074.6  5085.9  5137.1  5146.6  5197.2    5254  5450.4  5470.4  5629.5
  5809.5  5849.5  6030.6  6380.9  6430.9  6450.9  6480.9  6500.9  6580.9  6620.9
  6930.9  6970.9  7040.9  7100.9  7130.9    7263
    37.5    36.4    35.1    35.2   32.77   32.82   32.44    32.4   31.56   31.83
   31.85   32.34   32.51   32.54   32.56   32.82   32.89   32.79   32.78   32.65
   32.72   32.29   32.84   33.24   33.36   33.24   33.24    33.6    33.2    33.6
    33.3    34.5      34    34.3    33.9    33.2    33.3    33.9    33.9    34.5
    33.8      34      34    34.4    36.5    37.5
    37.5    36.4    35.1    35.2   32.76   32.81   32.43   32.39   31.55    31.5
   31.81   31.31   25.09   22.79   20.98   20.86   20.88   20.93   22.75   31.77
   32.71   32.11   32.83   33.17   33.15   33.06   33.13    33.6    33.2    33.6
    33.3    34.5      34    34.3    33.9    33.2    33.3    33.9    33.9    34.5
    33.8      34      34    34.4    36.5    37.5
    3026    3386    3536    3616  4725.7  4772.5  4827.9  4880.3  4931.2  4955.7
  4956.5  4971.7  4981.7  4983.2  4984.9    5001  5005.6  5015.1  5016.8  5029.4
  5049.1  5074.6  5085.9  5137.1  5146.6  5197.2    5254  5450.4  5470.4  5629.5
  5809.5  5849.5  6030.6  6380.9  6430.9  6450.9  6480.9  6500.9  6580.9  6620.9
  6930.9  6970.9  7040.9  7100.9  7130.9    7263
    37.5    36.4    35.1    35.2   32.77   32.82   32.44    32.4   31.56   31.83
   31.85   32.34   32.51   32.54   32.56   32.82   32.89   32.79   32.78   32.65
   32.72   32.29   32.84   33.24   33.36   33.24   33.24    33.6    33.2    33.6
    33.3    34.5      34    34.3    33.9    33.2    33.3    33.9    33.9    34.5
    33.8      34      34    34.4    36.5    37.5
   37.44   36.34   35.04   35.14    32.7   32.75   32.37   32.33   31.49   31.44
   31.75   31.25   25.03   22.73   20.92    20.8   20.82   20.87   22.69   31.71
   32.65   32.05   32.77   33.11   33.09      33   33.07   33.54   33.14   33.54
   33.24   34.44   33.94   34.24   33.84   33.14   33.24   33.84   33.84   34.44
   33.74   33.94   33.94   34.34   36.44   37.44
BR Coef= 1 , 0 , 0 ,1.25, 0 ,,,0.8,-1,2,0,
WSPro=,,,, 1 ,,,, 0 ,,,, 0 ,,,,-1 ,-1 ,-1 , 0 , 0 , 0 , 0 , 0
Culvert=2,8,10,61,0.015,0.4,1,8,1,20.74,4988.5,21.1,4988.5,Culvert #1  , 0 ,10
Culvert Bottom n=0.015
Culvert=2,8,10,61,0.015,0.4,1,8,1,20.74,4999.7,21.1,4999.7,Culvert #2  , 0 ,10
Culvert Bottom n=0.015
Culvert=2,8,10,61,0.015,0.4,1,8,1,20.74,5010.9,21.1,5010.9,Culvert #3  , 0 ,10
Culvert Bottom n=0.015
BR U #Sta/Elev= 66
    3026    37.5    3386    36.4    3536    35.1    3616    35.2  3772.7   34.86
  4192.7   33.93  4592.7   33.05  4722.8   32.77  4725.7   32.76  4772.5   32.81
  4788.8    32.7  4827.9   32.43  4865.5    32.4  4880.3   32.39  4928.2    31.6
  4931.2   31.55  4955.7    31.5  4956.5   31.81  4971.7   31.31 4972.99   30.51
  4973.1   30.44 4973.21   30.37  4981.7   25.09  4983.2   22.79  4984.9   20.98
    5001   20.86  5005.6   20.88  5015.1   20.93  5016.8   22.75 5026.29   29.54
  5026.4   29.62 5026.51    29.7  5029.4   31.77  5049.1   32.71  5049.9   32.69
  5074.6   32.11  5075.1   32.14  5084.9   32.77  5085.9   32.83  5137.1   33.17
  5146.6   33.15  5197.2   33.06  5201.5   33.07  5252.9   33.13    5254   33.13
  5450.4    33.6  5470.4    33.2  5629.5    33.6  5809.5    33.3  5849.5    34.5
  6030.6      34  6380.9    34.3  6430.9    33.9  6450.9    33.2  6480.9    33.3
  6500.9    33.9  6580.9    33.9  6620.9    34.5  6930.9    33.8  6970.9      34
  7040.9      34  7100.9    34.4  7130.9    36.5  7248.7   37.41  7260.9    37.5
    7263    37.5
BR U #Mann= 6
    3026     .99  4192.7      .2  4592.7      .1  4971.7    .015  5029.4      .1
  7248.7      .2
BR U Banks=4971.7,5029.4
BR D #Sta/Elev= 66
    3026   37.44    3386   36.34    3536   35.04    3616   35.14  3772.7    34.8
  4192.7   33.87  4592.7   32.99  4722.8   32.71  4725.7    32.7  4772.5   32.75
  4788.8   32.64  4827.9   32.37  4865.5   32.34  4880.3   32.33  4928.2   31.54
  4931.2   31.49  4955.7   31.44  4956.5   31.75  4971.7   31.25 4972.99   30.45
  4973.1   30.38 4973.21   30.31  4981.7   25.03  4983.2   22.73  4984.9   20.92
    5001    20.8  5005.6   20.82  5015.1   20.87  5016.8   22.69 5026.29   29.48
  5026.4   29.56 5026.51   29.64  5029.4   31.71  5049.1   32.65  5049.9   32.63
  5074.6   32.05  5075.1   32.08  5084.9   32.71  5085.9   32.77  5137.1   33.11
  5146.6   33.09  5197.2      33  5201.5   33.01  5252.9   33.07    5254   33.07
  5450.4   33.54  5470.4   33.14  5629.5   33.54  5809.5   33.24  5849.5   34.44
  6030.6   33.94  6380.9   34.24  6430.9   33.84  6450.9   33.14  6480.9   33.24
  6500.9   33.84  6580.9   33.84  6620.9   34.44  6930.9   33.74  6970.9   33.94
  7040.9   33.94  7100.9   34.34  7130.9   36.44  7248.7   37.35  7260.9   37.44
    7263   37.44
BR D #Mann= 6
    3026     .99  4192.7      .2  4592.7      .1  4971.7    .015  5029.4      .1
  7248.7      .2
BR D Banks=4971.7,5029.4
BC Design=,, 0 ,, 0 ,,,,,,
BC HTab HWMax=37.53
BC Use User HTab Curves=0
BC User HTab FreeFlow(D)= 0

Type RM Length L Ch R = 1 ,12638.3 ,33,33.4,34
BEGIN DESCRIPTION:
Downstream Section of Bridge/Culvert/Weir
END DESCRIPTION:
XS GIS Cut Line= 5
      3153142.29     13806598.48      3154419.55     13806688.45
      3155166.45      13806701.9      3156291.97     13806512.17
      3157359.34     13806553.22
#Sta/Elev= 30
    3026   37.44    3386   36.34    3536   35.04  4192.7   33.87  4592.7   32.99
  4880.3   32.33  4971.7   31.25  4981.7   25.03  4983.2   22.73  4984.9   20.92
    5001    20.8  5015.1   20.87  5016.8   22.69  5029.4   31.71  5049.1   32.65
  5074.6   32.05  5085.9   32.77  5137.1   33.11  5809.5   33.24  5849.5   34.44
  6030.6   33.94  6380.9   34.24  6430.9   33.84  6450.9   33.14  6620.9   34.44
  7040.9   33.94  7100.9   34.34  7130.9   36.44  7248.7   37.35    7263   37.44
#Mann= 6 , 1 , 0
    3026     .99       0  4192.7      .2       0  4592.7      .1       0
  4971.7    .015       0  5029.4      .1       0  7248.7      .2       0
#XS Ineff= 2 , 0
       0  4973.8    31.4  5026.5       0    32.1
Permanent Ineff=
       F       F
Bank Sta=4971.7,5029.4
XS Rating Curve= 0 ,0
Exp/Cntr=0.5,0.3

Type RM Length L Ch R = 1 ,12604.9 ,14.2,139,62.8
BEGIN DESCRIPTION:
Cross Section 12604.9-Interpolated
END DESCRIPTION:
XS GIS Cut Line= 6
      3153183.33     13806779.52      3154157.08     13806807.48
      3154529.02     13806737.74      3155186.79     13806750.07
      3156100.55     13806576.51      3157244.72     13806576.51
#Sta/Elev= 30
  3065.8   37.93  3715.8   35.44  3895.8   34.63  3905.8   34.29  3965.8   34.86
  3995.8   34.47  4035.8   34.82  4774.4   34.07  4966.8   31.86  4983.4   24.88
  4984.4   22.82  4984.5   20.93  4998.6   20.79  5015.2   20.91  5015.5    22.8
  5028.6   31.48  5034.4   31.27  5044.4   32.05  5102.9   33.61  5832.9   33.42
  6021.2   34.63  6441.2   33.98  6461.2   33.21  6491.2   33.11  6511.2      34
  6601.2   34.07  7001.2   33.95  7061.2   34.07  7091.2    36.7  7151.8    37.6
#Mann= 5 , 1 , 0
  3065.8      .2       0  3065.8      .1       0  4966.8     .04       0
  5028.6      .1       0  7151.8      .2       0
Bank Sta=4966.8,5028.6
XS Rating Curve= 0 ,0
Exp/Cntr=0.5,0.3

Type RM Length L Ch R = 1 ,12465.9 ,66.6,66.6,66.6
BEGIN DESCRIPTION:
Upstream Section of Bridge/Culvert/Weir
END DESCRIPTION:
XS GIS Cut Line= 6
      3153266.39     13807387.39       3154431.6     13807332.99
      3155094.12     13807063.18      3155120.65     13806802.46
      3155879.22     13806701.76      3157306.24     13806727.72
#Sta/Elev= 30
  2914.5    37.5  3384.5    36.8  3424.5    34.5  3454.5    34.4  3494.5    36.2
  3574.5    36.4  4161.8   33.83  4218.1    33.5  4268.1      32  4573.2    34.4
  4741.8   32.84 4899.91   32.12  4958.9   32.88  4966.8   31.83  4983.4   24.85
  4984.4   22.79  4984.5    20.9  4998.6   20.76  5015.2   20.88  5015.5   22.77
  5028.6   31.45  5064.5   32.76  5851.1    33.5  5891.1    34.7  6329.2    34.4
  6519.2    33.4  6629.2    34.2  7112.2   34.46  7149.2    36.8  7254.9    37.6
#Mann= 6 , 1 , 0
  2914.5     .99       0  4161.8      .2       0  4741.8      .1       0
  4966.8    .015       0  5028.6      .1       0  7112.2      .2       0
#XS Ineff= 2 , 0
       0  4974.8      32  5026.4       0    33.3
Permanent Ineff=
       F       F
Bank Sta=4966.8,5028.6
XS Rating Curve= 0 ,0
Exp/Cntr=0.5,0.3

Type RM Length L Ch R = 2 ,12432.6 ,,,
BEGIN DESCRIPTION:
MONROE STREET
Structure ID: C61-7
END DESCRIPTION:
Bridge Culvert--1,0,-1,-1, 0
Deck Dist Width WeirC Skew NumUp NumDn MinLoCord MaxHiCord MaxSubmerge Is_Ogee
10,46.6,3,0, 57, 57, , , 0.95, 0, 1,1,,
  2914.5  3384.5  3404.5  3424.5  3454.5  3494.5  3574.5  3604.5  4048.1  4218.1
  4268.1  4368.1  4503.2  4573.2  4643.2    4660  4762.8  4828.2  4899.5  4899.6
 4899.69  4899.8  4939.5  4939.9  4958.9  4966.8  4983.4  4984.4  4984.5  4998.6
  5015.2  5015.5  5028.6  5064.5    5119  5153.6    5174  5199.4  5199.8    5240
    5241  5270.3  5277.5 5277.61  5281.1  5851.1  5891.1  6329.2  6469.2  6519.2
  6539.2  6629.2  6989.2  7039.2  7119.2  7149.2  7254.9
    37.5    36.8      36    34.5    34.4    36.2    36.4    35.7    34.5    33.5
      32    32.6      34    34.4   34.01   33.31   32.73   32.59   32.66   32.13
   32.13   34.92   34.99   34.99   35.02   35.03   35.03   35.03   35.03   35.07
   35.11   35.11   35.15   35.25   35.38   35.44   35.39   35.33   35.33   35.25
   35.25    35.2    35.2   33.36   33.51    33.5    34.7    34.4      34    33.4
      34    34.2    33.9      34    34.5    36.8    37.6
    37.5    36.8      36    34.5    34.4    36.2    36.4    35.7    34.5    33.5
      32    32.6      34    34.4      34    33.3   32.72   32.58   32.65   32.12
   32.12   32.12   32.18   32.73   32.88   31.83   24.85   22.79    20.9   20.76
   20.88   22.77   31.45   32.76   32.92   32.81   32.74   33.14   32.63   32.61
   33.14   33.04   33.35   33.35    33.5    33.5    34.7    34.4      34    33.4
      34    34.2    33.9      34    34.5    36.8    37.6
  2914.5  3384.5  3404.5  3424.5  3454.5  3494.5  3574.5  3604.5  4048.1  4218.1
  4268.1  4368.1  4503.2  4573.2  4643.2    4660  4762.8  4828.2  4899.5  4899.6
 4899.69  4899.8  4939.5  4939.9  4958.9  4966.8  4983.4  4984.4  4984.5  4998.6
  5015.2  5015.5  5028.6  5064.5    5119  5153.6    5174  5199.4  5199.8    5240
    5241  5270.3  5277.5 5277.61  5281.1  5851.1  5891.1  6329.2  6469.2  6519.2
  6539.2  6629.2  6989.2  7039.2  7119.2  7149.2  7254.9
    37.5    36.8      36    34.5    34.4    36.2    36.4    35.7    34.5    33.5
      32    32.6      34    34.4   34.01   33.31   32.73   32.59   32.66   32.13
   32.13   34.92   34.99   34.99   35.02   35.03   35.03   35.03   35.03   35.07
   35.11   35.11   35.15   35.25   35.38   35.44   35.39   35.33   35.33   35.25
   35.25    35.2    35.2   33.36   33.51    33.5    34.7    34.4      34    33.4
      34    34.2    33.9      34    34.5    36.8    37.6
   37.44   36.74   35.94   34.44   34.34   36.14   36.34   35.64   34.44   33.44
   31.94   32.54   33.94   34.34   33.94   33.24   32.66   32.52   32.59   32.06
   32.06   32.06   32.12   32.67   32.82   31.77   24.79   22.73   20.84    20.7
   20.82   22.71   31.39    32.7   32.86   32.75   32.68   33.08   32.57   32.55
   33.08   32.98   33.29   33.29   33.44   33.44   34.64   34.34   33.94   33.34
   33.94   34.14   33.84   33.94   34.44   36.74   37.54
BR Coef= 1 , 0 , 0 ,1.25, 0 ,,,0.8,-1,2,0,
WSPro=,,,, 1 ,,,, 0 ,,,, 0 ,,,,-1 ,-1 ,-1 , 0 , 0 , 0 , 0 , 0
Culvert=2,8,10,46.6,0.015,0.4,1,8,1,20.75,4989.8,20.7,4989.8,Culvert #1  , 0 ,10
Culvert Bottom n=0.015
Culvert=2,8,10,46.6,0.015,0.4,1,8,1,20.75,5000.6,20.7,5000.6,Culvert #2  , 0 ,10
Culvert Bottom n=0.015
Culvert=2,8,10,46.6,0.015,0.4,1,8,1,20.75,5011.4,20.7,5011.4,Culvert #3  , 0 ,10
Culvert Bottom n=0.015
BR U #Sta/Elev= 83
  2914.5    37.5  3384.5    36.8  3404.5      36  3424.5    34.5  3454.5    34.4
  3494.5    36.2  3574.5    36.4  3604.5    35.7  4048.1    34.5  4161.8   33.83
  4218.1    33.5  4268.1      32  4368.1    32.6  4503.2      34  4573.2    34.4
    4600   34.25  4643.2      34    4660    33.3  4741.8   32.84  4762.8   32.72
  4766.6    32.7  4766.7    32.7    4820    32.6  4828.2   32.58  4876.2   32.63
  4899.5   32.65  4899.6   32.12 4899.69   32.12  4899.8   32.12 4899.91   32.12
  4932.7   32.17  4939.5   32.18  4939.9   32.73 4949.69   32.81  4949.8   32.81
 4949.91   32.81  4958.9   32.88 4965.59   31.99  4965.7   31.98 4965.81   31.96
  4966.8   31.83 4972.59    29.4  4972.7   29.35 4972.91   29.26  4983.4   24.85
  4984.4   22.79  4984.5    20.9  4998.6   20.76  5000.3   20.77  5015.2   20.88
  5015.5   22.77  5028.6   31.45  5064.5   32.76  5092.5   32.84    5119   32.92
  5153.6   32.81    5174   32.74  5199.4   33.14  5199.8   32.63  5205.9   32.63
    5240   32.61    5241   33.14  5270.2   33.04  5270.3   33.04 5277.39   33.34
  5277.5   33.35 5277.61   33.35  5281.1    33.5    5360    33.5  5851.1    33.5
  5891.1    34.7  5893.3    34.7  6329.2    34.4  6469.2      34  6519.2    33.4
  6539.2      34  6629.2    34.2  6989.2    33.9  7039.2      34  7112.2   34.46
  7119.2    34.5  7149.2    36.8  7254.9    37.6
BR U #Mann= 6
  2914.5     .99  4161.8      .2  4741.8      .1  4966.8    .015  5028.6      .1
  7112.2      .2
BR U Banks=4966.8,5028.6
BR D #Sta/Elev= 83
  2914.5   37.44  3384.5   36.74  3404.5   35.94  3424.5   34.44  3454.5   34.34
  3494.5   36.14  3574.5   36.34  3604.5   35.64  4048.1   34.44  4161.8   33.77
  4218.1   33.44  4268.1   31.94  4368.1   32.54  4503.2   33.94  4573.2   34.34
    4600   34.19  4643.2   33.94    4660   33.24  4741.8   32.78  4762.8   32.66
  4766.6   32.64  4766.7   32.64    4820   32.54  4828.2   32.52  4876.2   32.57
  4899.5   32.59  4899.6   32.06 4899.69   32.06  4899.8   32.06 4899.91   32.06
  4932.7   32.11  4939.5   32.12  4939.9   32.67 4949.69   32.75  4949.8   32.75
 4949.91   32.75  4958.9   32.82 4965.59   31.93  4965.7   31.92 4965.81    31.9
  4966.8   31.77 4972.59   29.34  4972.7   29.29 4972.91    29.2  4983.4   24.79
  4984.4   22.73  4984.5   20.84  4998.6    20.7  5000.3   20.71  5015.2   20.82
  5015.5   22.71  5028.6   31.39  5064.5    32.7  5092.5   32.78    5119   32.86
  5153.6   32.75    5174   32.68  5199.4   33.08  5199.8   32.57  5205.9   32.57
    5240   32.55    5241   33.08  5270.2   32.98  5270.3   32.98 5277.39   33.28
  5277.5   33.29 5277.61   33.29  5281.1   33.44    5360   33.44  5851.1   33.44
  5891.1   34.64  5893.3   34.64  6329.2   34.34  6469.2   33.94  6519.2   33.34
  6539.2   33.94  6629.2   34.14  6989.2   33.84  7039.2   33.94  7112.2    34.4
  7119.2   34.44  7149.2   36.74  7254.9   37.54
BR D #Mann= 6
  2914.5     .99  4161.8      .2  4741.8      .1  4966.8    .015  5028.6      .1
  7112.2      .2
BR D Banks=4966.8,5028.6
BC Design=,, 0 ,, 0 ,,,,,,
BC HTab HWMax=37.6
BC Use User HTab Curves=0
BC User HTab FreeFlow(D)= 0

Type RM Length L Ch R = 1 ,12399.3 ,464.8,918,1028.2
BEGIN DESCRIPTION:
Downstream Section of Bridge/Culvert/Weir
END DESCRIPTION:
XS GIS Cut Line= 6
      3153331.29     13807402.33       3154496.5     13807347.93
      3155159.02     13807078.12      3155185.55      13806817.4
      3155944.12      13806716.7      3157371.14     13806742.66
#Sta/Elev= 30
  2914.5   37.45  3384.5   36.75  3424.5   34.45  3454.5   34.35  3494.5   36.15
  3574.5   36.35  4161.8   33.78  4218.1   33.45  4268.1   31.95  4573.2   34.35
  4741.8   32.79 4899.91   32.07  4958.9   32.83  4966.8   31.78  4983.4    24.8
  4984.4   22.74  4984.5   20.85  4998.6   20.71  5015.2   20.83  5015.5   22.72
  5028.6    31.4  5064.5   32.71  5851.1   33.45  5891.1   34.65  6329.2   34.35
  6519.2   33.35  6629.2   34.15  7112.2   34.41  7149.2   36.75  7254.9   37.55
#Mann= 6 , 1 , 0
  2914.5     .99       0  4161.8      .2       0  4741.8      .1       0
  4966.8    .015       0  5028.6      .1       0  7112.2      .2       0
#XS Ineff= 2 , 0
       0  4974.8      32  5026.4       0    33.3
Permanent Ineff=
       F       F
Bank Sta=4966.8,5028.6
XS Rating Curve= 0 ,0
Exp/Cntr=0.5,0.3

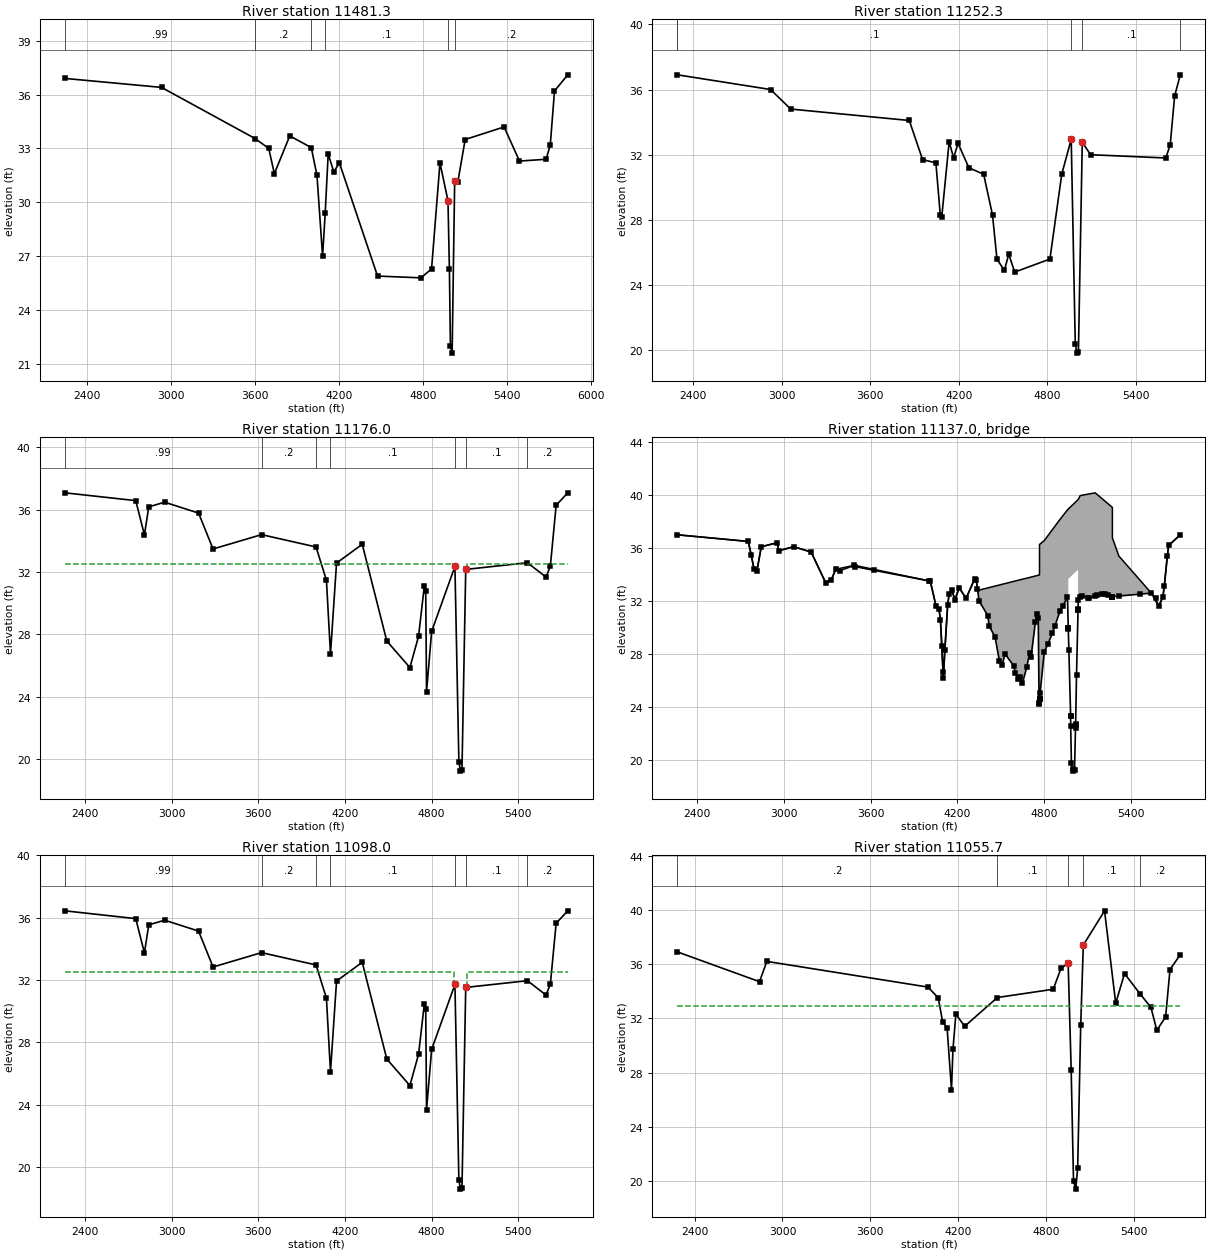
Type RM Length L Ch R = 1 ,11481.3 ,114,229,248.5
BEGIN DESCRIPTION:
Cross Section 11481.3
END DESCRIPTION:
XS GIS Cut Line= 6
      3153268.11     13807414.22       3154461.2     13807376.56
      3155193.12     13807139.98      3155817.34     13807091.96
      3156114.18     13807118.15      3156773.17      13807367.4
#Sta/Elev= 30
  2240.3    36.9  2930.3    36.4  3599.3   33.55  3696.3      33  3736.3    31.6
  3846.3    33.7    4000   33.05  4040.7    31.5  4080.7      27  4099.3   29.39
  4120.7    32.7  4160.7    31.7  4200.7    32.2  4473.2    25.9  4783.2    25.8
  4859.2    26.3  4919.2    32.2  4976.4   30.09  4986.6   26.27  4993.9   21.98
  5006.1   21.61  5024.2   31.17  5047.1   31.15  5099.2    33.5  5377.2    34.2
  5487.2    32.3  5677.2    32.4  5707.2    33.2  5737.2    36.2  5831.8    37.1
#Mann= 6 , 1 , 0
  2240.3     .99       0  3599.3      .2       0    4000     .99       0
  4099.3      .1       0  4976.4     .04       0  5024.2      .2       0
Bank Sta=4976.4,5024.2
XS Rating Curve= 0 ,0
Exp/Cntr=0.3,0.1

Type RM Length L Ch R = 1 ,11252.3 ,82.5,76.3,76.2
BEGIN DESCRIPTION:
Cross Section 11252.3-Interpolated
END DESCRIPTION:
XS GIS Cut Line= 6
      3153327.38     13807607.97      3154090.13     13807529.27
      3155246.36     13807190.27      3155694.32     13807214.48
      3156027.27     13807365.82      3156632.62     13807474.79
#Sta/Elev= 30
  2295.5    36.9  2925.5      36  3062.3    34.8  3864.8    34.1  3954.8    31.7
  4044.8    31.5  4074.8    28.3  4084.8    28.2  4134.8    32.8  4164.8    31.8
  4194.8    32.7  4268.3    31.2  4368.3    30.8  4428.3    28.3  4458.3    25.6
  4508.3    24.9  4538.3    25.9  4578.3    24.8  4816.9    25.6  4896.9    30.8
  4961.1   32.95  4988.4   20.42  4999.2   19.83  5009.8   19.88  5035.9   32.76
  5092.6      32  5601.2    31.8  5631.2    32.6  5661.2    35.6  5699.4    36.9
#Mann= 5 , 1 , 0
  2295.5      .2       0  2295.5      .1       0  4961.1     .04       0
  5035.9      .1       0  5699.4      .2       0
Bank Sta=4961.1,5035.9
XS Rating Curve= 0 ,0
Exp/Cntr=0.5,0.3

Type RM Length L Ch R = 1 ,11176.0 ,78,78,78
BEGIN DESCRIPTION:
Upstream Section of Bridge/Culvert/Weir
END DESCRIPTION:
XS GIS Cut Line= 6
       3153269.8     13807673.44      3154126.81     13807603.65
      3155059.32     13807293.04      3155361.92     13807279.89
      3155718.37     13807302.45      3156643.45      13807553.5
#Sta/Elev= 30
  2262.6   37.08  2752.6   36.58  2812.6   34.38  2842.6   36.18  2952.6   36.48
  3187.4   35.78  3287.4   33.48    3623    34.4    4000   33.61    4072   31.48
    4100   26.76    4142   32.58  4319.7   33.78  4489.7   27.58  4649.4   25.88
  4709.4   27.88    4749   31.08    4759   30.78  4764.6   24.33  4800.1    28.2
  4961.1   32.36  4988.4   19.83  4999.2   19.24  5009.8   19.29  5035.9   32.17
  5462.7    32.6  5591.4   31.68  5621.4   32.38  5661.4   36.28  5741.6   37.08
#Mann= 7 , 1 , 0
  2262.6     .99       0    3623      .2       0    4000     .99       0
    4100      .1       0  4961.1     .04       0  5035.9      .1       0
  5462.7      .2       0
#XS Ineff= 2 , 0
       0    4956    32.5    5045       0    32.5
Permanent Ineff=
       F       F
Bank Sta=4961.1,5035.9
XS Rating Curve= 0 ,0
Exp/Cntr=0.5,0.3

Type RM Length L Ch R = 3 ,11137.0 ,,,
BEGIN DESCRIPTION:
EASTBOUND MONROE STREET
Structure ID: C61-6
END DESCRIPTION:
Bridge Culvert--1,0,-1,-1, 0
Deck Dist Width WeirC Skew NumUp NumDn MinLoCord MaxHiCord MaxSubmerge Is_Ogee
10,58,2.6,0, 60, 60, , , 0.95, 0, 1,1,,
  2262.6  2752.6  2792.6  2812.6  2842.6  2952.6  2962.6  3067.4  3187.4  3287.4
  3327.4  3357.4  3487.4    4012    4052    4072    4082    4102    4132    4142
    4162    4182    4212  4259.7  4319.7  4329.7  4338.4  4349.7  4409.7  4419.7
  4459.7  4489.7  4509.7  4529.7  4649.4  4699.4  4709.4    4749    4759  4764.6
 4767.59  4767.7  4800.1  4909.7  4961.1 4966.71  4966.8 5034.19  5034.3  5035.9
    5049  5152.9  5271.8 5271.91  5316.7  5541.4  5591.4  5621.4  5661.4  5741.6
      37    36.5    34.4    34.3    36.1    36.4    35.8    36.1    35.7    33.4
    33.6    34.4    34.7    33.5    31.6    31.4    30.6    26.2    31.7    32.5
    32.8    32.1      33    32.2    33.7    33.6   32.91   32.83   32.99   33.02
   33.13   33.21   33.27   33.32   33.65   33.78   33.81   33.92   33.95   33.96
   33.97   36.27   36.56   38.17   38.88   38.95   38.95   39.65   39.65   39.68
   39.96   40.17   39.07   36.77    35.4    32.6    31.6    32.3    36.2      37
      37    36.5    34.4    34.3    36.1    36.4    35.8    36.1    35.7    33.4
    33.6    34.4    34.7    33.5    31.6    31.4    30.6    26.2    31.7    32.5
    32.8    32.1      33    32.2    33.7    33.6    32.9      32    30.9    30.1
    29.3    27.5    27.2      28    25.8    28.1    27.8      31    30.7   24.25
   24.59   24.61   28.12   31.26   32.28   29.95   33.67   34.37   31.35   32.09
   32.27    32.4   32.33   32.33   32.38    32.6    31.6    32.3    36.2      37
  2262.6  2752.6  2792.6  2812.6  2842.6  2952.6  2962.6  3067.4  3187.4  3287.4
  3327.4  3357.4  3487.4    4012    4052    4072    4082    4102    4132    4142
    4162    4182    4212  4259.7  4319.7  4329.7  4338.4  4349.7  4409.7  4419.7
  4459.7  4489.7  4509.7  4529.7  4649.4  4699.4  4709.4    4749    4759  4764.6
 4767.59  4767.7  4800.1  4909.7  4961.1 4966.71  4966.8 5034.19  5034.3  5035.9
    5049  5152.9  5271.8 5271.91  5316.7  5541.4  5591.4  5621.4  5661.4  5741.6
      37    36.5    34.4    34.3    36.1    36.4    35.8    36.1    35.7    33.4
    33.6    34.4    34.7    33.5    31.6    31.4    30.6    26.2    31.7    32.5
    32.8    32.1      33    32.2    33.7    33.6   32.91   32.83   32.99   33.02
   33.13   33.21   33.27   33.32   33.65   33.78   33.81   33.92   33.95   33.96
   33.97   36.27   36.56   38.17   38.88   38.95   38.95   39.65   39.65   39.68
   39.96   40.17   39.07   36.77    35.4    32.6    31.6    32.3    36.2      37
   36.26   35.76   33.66   33.56   35.36   35.66   35.06   35.36   34.96   32.66
   32.86   33.66   33.96   32.76   30.86   30.66   29.86   25.46   30.96   31.76
   32.06   31.36   32.26   31.46   32.96   32.86   32.16   31.26   30.16   29.36
   28.56   26.76   26.46   27.26   25.06   27.36   27.06   30.26   29.96   23.51
   23.85   23.87   27.38   30.52   31.54   29.21   32.93   33.63   30.61   31.35
   31.53   31.66   31.59   31.59   31.64   31.86   30.86   31.56   35.46   36.26
Abutment Skew #Up #Dn= , 2 , 2
  4966.6    4983
   33.67   23.31
  4966.6    4983
   32.93   22.57
Abutment Skew #Up #Dn= , 2 , 2
  5017.5 5034.39
   22.74   34.37
  5017.5 5034.39
      22   33.63
BR Coef= 1 , 1 , 0 ,1.25, 0 ,,,0.8,0,2,0,
WSPro=,,,, 1 ,,,, 0 ,,,, 0 ,,,,-1 ,-1 ,-1 , 0 , 0 , 0 , 0 , 0
BR U #Sta/Elev= 108
  2262.6      37  2752.6    36.5  2772.6    35.5  2792.6    34.4  2812.6    34.3
  2842.6    36.1  2952.6    36.4  2962.6    35.8  3067.4    36.1  3187.4    35.7
  3287.4    33.4  3327.4    33.6  3357.4    34.4  3387.4    34.3  3487.4    34.7
    3492    34.6    3623   34.32    4000   33.53    4012    33.5    4052    31.6
    4072    31.4    4082    30.6    4092    28.6    4100   26.68    4102    26.2
    4112    28.3    4132    31.7    4142    32.5    4162    32.8    4182    32.1
    4212      33  4259.7    32.2  4319.7    33.7  4329.7    33.6  4338.4    32.9
  4349.7      32  4409.7    30.9  4419.7    30.1  4459.7    29.3  4489.7    27.5
  4509.7    27.2  4529.7      28  4589.7    27.1  4599.4    26.6  4619.4    26.1
  4629.4    26.3  4649.4    25.8  4679.4      27  4699.4    28.1  4709.4    27.8
    4739    30.4    4749      31    4759    30.7  4764.6   24.25  4764.7   24.28
 4767.59   24.59  4767.7   24.61 4767.81   24.62  4771.6   25.03  4800.1   28.12
  4824.5   28.74  4857.4   29.58  4874.9   30.14  4909.7   31.26  4927.8   31.62
  4961.1   32.28  4966.6   29.99 4966.71   29.95  4966.8   29.91  4970.7   28.29
  4982.9   23.35    4983   23.31  4983.3   22.57  4988.4   19.75    4996   19.33
  4999.2   19.16  5009.8   19.21  5016.7   22.42  5017.4   22.68  5017.5   22.74
  5023.7   26.44 5034.19    31.3  5034.3   31.35  5034.4    31.4  5035.9   32.09
    5049   32.27  5059.5   32.41  5101.3   32.25  5111.9   32.21  5152.9    32.4
  5165.9   32.46  5202.3   32.51  5218.6   32.53    5243   32.43  5268.5   32.33
 5271.69   32.33  5271.8   32.33 5271.91   32.33  5316.7   32.38  5462.7   32.52
  5541.4    32.6  5571.4    32.2  5591.4    31.6  5621.4    32.3  5631.4    33.1
  5651.4    35.4  5661.4    36.2  5741.6      37
BR U #Mann= 7
  2262.6     .99    3623      .2    4000     .99    4100      .1  4961.1     .04
  5035.9      .1  5462.7      .2
BR U Banks=4961.1,5035.9
BR D #Sta/Elev= 108
  2262.6   36.26  2752.6   35.76  2772.6   34.76  2792.6   33.66  2812.6   33.56
  2842.6   35.36  2952.6   35.66  2962.6   35.06  3067.4   35.36  3187.4   34.96
  3287.4   32.66  3327.4   32.86  3357.4   33.66  3387.4   33.56  3487.4   33.96
    3492   33.86    3623   33.58    4000   32.79    4012   32.76    4052   30.86
    4072   30.66    4082   29.86    4092   27.86    4100   25.94    4102   25.46
    4112   27.56    4132   30.96    4142   31.76    4162   32.06    4182   31.36
    4212   32.26  4259.7   31.46  4319.7   32.96  4329.7   32.86  4338.4   32.16
  4349.7   31.26  4409.7   30.16  4419.7   29.36  4459.7   28.56  4489.7   26.76
  4509.7   26.46  4529.7   27.26  4589.7   26.36  4599.4   25.86  4619.4   25.36
  4629.4   25.56  4649.4   25.06  4679.4   26.26  4699.4   27.36  4709.4   27.06
    4739   29.66    4749   30.26    4759   29.96  4764.6   23.51  4764.7   23.54
 4767.59   23.85  4767.7   23.87 4767.81   23.88  4771.6   24.29  4800.1   27.38
  4824.5      28  4857.4   28.84  4874.9    29.4  4909.7   30.52  4927.8   30.88
  4961.1   31.54  4966.6   29.25 4966.71   29.21  4966.8   29.17  4970.7   27.55
  4982.9   22.61    4983   22.57  4983.3   21.83  4988.4   19.01    4996   18.59
  4999.2   18.42  5009.8   18.47  5016.7   21.68  5017.4   21.94  5017.5      22
  5023.7    25.7 5034.19   30.56  5034.3   30.61  5034.4   30.66  5035.9   31.35
    5049   31.53  5059.5   31.67  5101.3   31.51  5111.9   31.47  5152.9   31.66
  5165.9   31.72  5202.3   31.77  5218.6   31.79    5243   31.69  5268.5   31.59
 5271.69   31.59  5271.8   31.59 5271.91   31.59  5316.7   31.64  5462.7   31.78
  5541.4   31.86  5571.4   31.46  5591.4   30.86  5621.4   31.56  5631.4   32.36
  5651.4   34.66  5661.4   35.46  5741.6   36.26
BR D #Mann= 7
  2262.6     .99    3623      .2    4000     .99    4100      .1  4961.1     .04
  5035.9      .1  5462.7      .2
BR D Banks=4961.1,5035.9
BC Design=,, 0 ,, 0 ,,,,,,
BC HTab HWMax=37.08
BC Use User HTab Curves=0
BC User HTab FreeFlow(D)= 0

Type RM Length L Ch R = 1 ,11098.0 ,42,42.3,43
BEGIN DESCRIPTION:
Downstream Section of Bridge/Culvert/Weir
END DESCRIPTION:
XS GIS Cut Line= 6
      3153242.78     13807746.61      3154099.79     13807676.83
       3155032.3     13807366.22       3155334.9     13807353.07
      3155691.35     13807375.63      3156616.43     13807626.67
#Sta/Elev= 30
  2262.6   36.44  2752.6   35.94  2812.6   33.74  2842.6   35.54  2952.6   35.84
  3187.4   35.14  3287.4   32.84    3623   33.76    4000   32.97    4072   30.84
    4100   26.12    4142   31.94  4319.7   33.14  4489.7   26.94  4649.4   25.24
  4709.4   27.24    4749   30.44    4759   30.14  4764.6   23.69  4800.1   27.56
  4961.1   31.72  4988.4   19.19  4999.2    18.6  5009.8   18.65  5035.9   31.53
  5462.7   31.96  5591.4   31.04  5621.4   31.74  5661.4   35.64  5741.6   36.44
#Mann= 7 , 1 , 0
  2262.6     .99       0    3623      .2       0    4000     .99       0
    4100      .1       0  4961.1     .04       0  5035.9      .1       0
  5462.7      .2       0
#XS Ineff= 2 , 0
       0    4956    32.5    5045       0    32.5
Permanent Ineff=
       F       F
Bank Sta=4961.1,5035.9
XS Rating Curve= 0 ,0
Exp/Cntr=0.5,0.3

Type RM Length L Ch R = 1 ,11055.7 ,43,43,43
BEGIN DESCRIPTION:
Upstream Section of Bridge/Culvert/Weir
END DESCRIPTION:
XS GIS Cut Line= 6
      3153256.62     13807882.89      3154238.21     13807696.94
      3155376.35     13807375.23      3155891.11     13807519.12
      3156339.14     13807541.25      3156582.12     13807636.07
#Sta/Elev= 30
  2283.4   36.92  2843.4   34.72  2893.4   36.22  3993.9   34.32  4063.9   33.52
  4093.9   31.72  4123.9   31.32  4153.9   26.72  4163.9   29.72  4183.9   32.32
  4243.9   31.42  4467.1   33.55  4848.7   34.16  4901.2    35.7  4950.3   36.09
  4970.9   28.21  4986.9   19.98    5002   19.38  5015.3   20.93  5036.1   31.55
  5053.8   37.43  5198.8   39.96    5275   33.12    5335   35.32  5442.6    33.8
  5515.6   32.82  5555.6   31.12  5615.6   32.12  5645.6   35.62  5715.7   36.72
#Mann= 5 , 1 , 0
  2283.4      .2       0  4467.1      .1       0  4950.3     .04       0
  5053.8      .1       0  5442.6      .2       0
#XS Ineff= 2 , 0
       0    4959    32.9  5039.6       0    32.9
Permanent Ineff=
       F       F
Bank Sta=4950.3,5053.8
XS Rating Curve= 0 ,0
Exp/Cntr=0.5,0.3