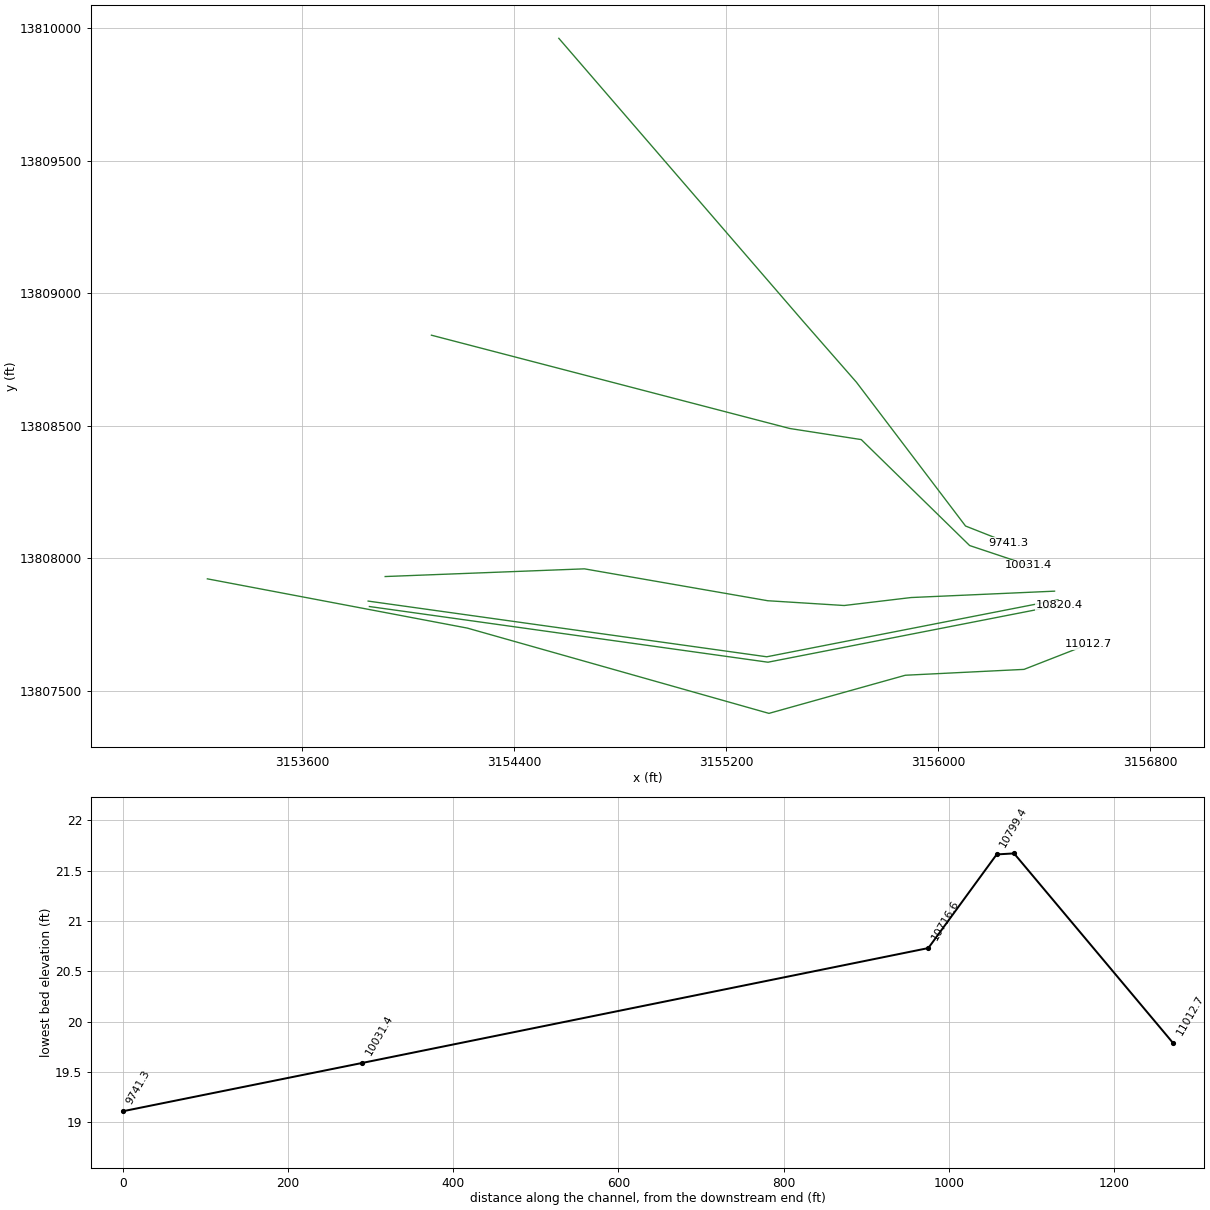
HEC-RAS study C106-01-00.PRJ: C106-01-00

--- C106-01-00.g01 (geometry) --- (continued)

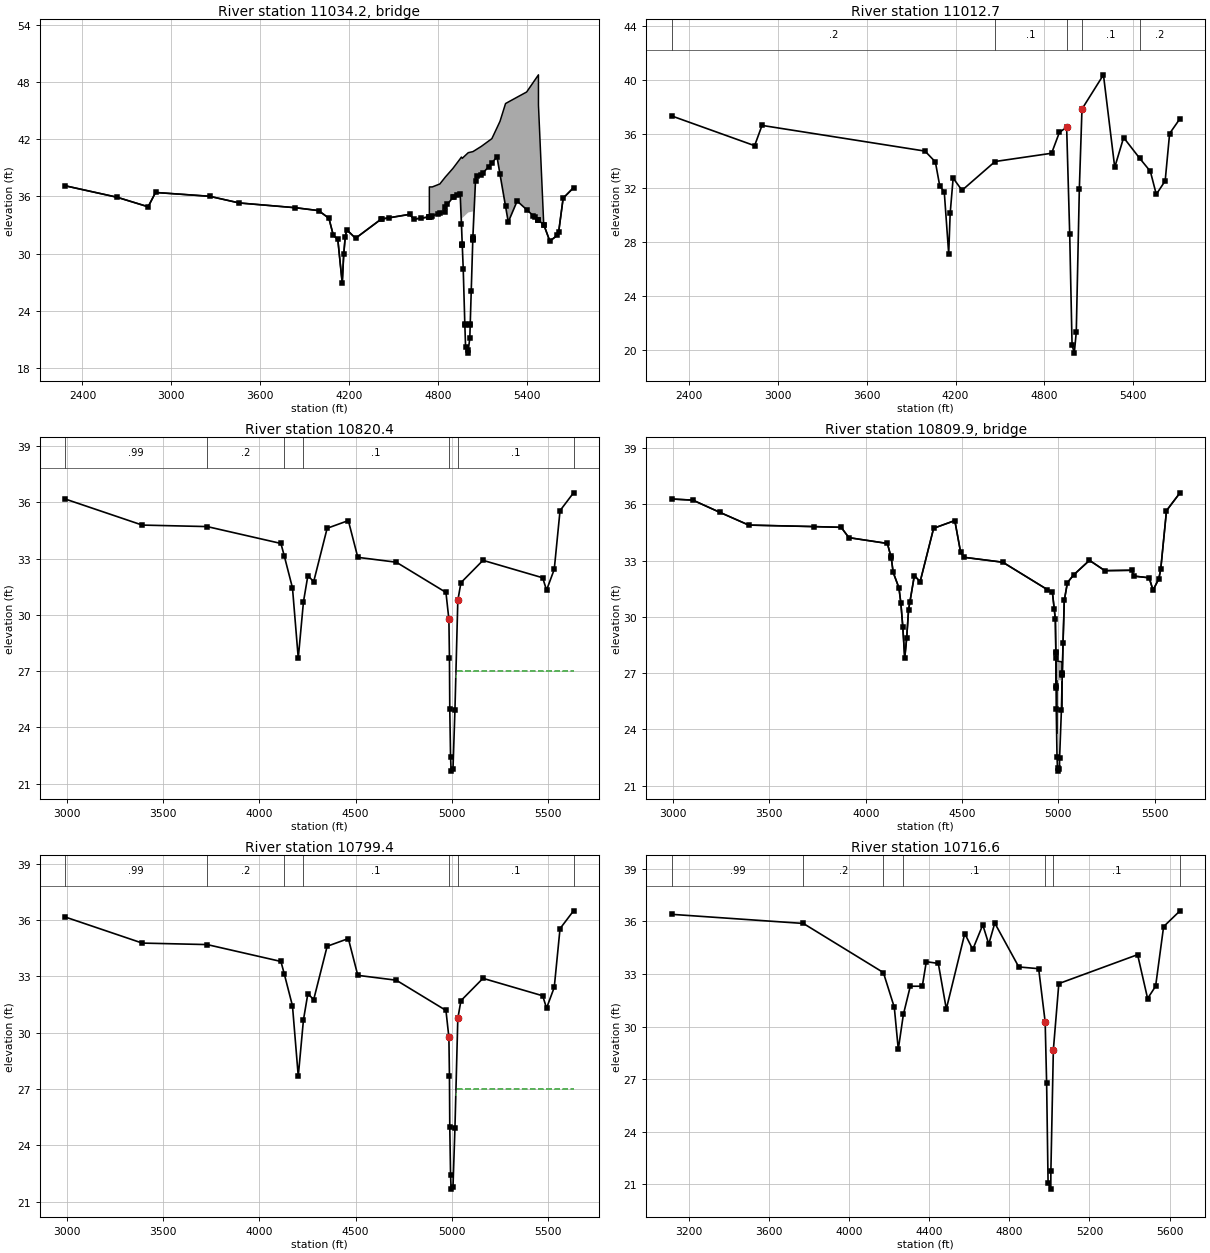
Type RM Length L Ch R = 3 ,11034.2 ,,,
BEGIN DESCRIPTION:
WESTBOUND MONROE STREET
Structure ID: C61-5
END DESCRIPTION:
Bridge Culvert--1,0,-1,-1, 0
Deck Dist Width WeirC Skew NumUp NumDn MinLoCord MaxHiCord MaxSubmerge Is_Ogee
10,23,2.6,0, 52, 52, , , 0.95, 0, 1,1,,
  2283.4  2633.4  2843.4  2893.4  3258.3  3458.3  3838.3  3993.9  4063.9  4093.9
  4123.9  4153.9  4163.9  4173.9  4183.9  4243.9  4419.2  4608.5  4638.5 4742.09
  4742.2  4761.7  4812.8  4848.7  4849.1  4901.2  4950.3  4958.5 4964.31  4964.4
  5004.7 5035.49  5035.6  5036.1  5053.8    5063  5092.9  5164.2  5198.8  5219.2
  5256.6    5275    5335    5399  5478.9 5479.01  5514.6  5555.6  5605.6  5615.6
  5645.6  5715.7
    37.1    35.9    34.9    36.4      36    35.3    34.8    34.5    33.7    31.9
    31.5    26.9    29.9    31.7    32.5    31.6   33.62   34.11   33.61   33.84
   36.98   36.98   37.29   37.99      38   38.92   39.93   40.11   39.98   39.98
   40.57   40.68   40.68   40.68   40.85   40.94   41.23   42.04   43.18   43.86
   45.72   45.88   46.39   46.93   48.73   45.53   33.02    31.3    31.9    32.3
    35.8    36.9
    37.1    35.9    34.9    36.4      36    35.3    34.8    34.5    33.7    31.9
    31.5    26.9    29.9    31.7    32.5    31.6   33.61    34.1    33.6   33.83
   33.83   33.92   34.22   34.34   34.86   35.88   36.27   33.13   30.91   33.71
    34.3   34.41   31.48   31.73   37.61   38.11   38.26   39.49   40.14   38.31
   34.95    33.3    35.5    34.6   33.49   33.49   33.01    31.3    31.9    32.3
    35.8    36.9
  2283.4  2633.4  2843.4  2893.4  3258.3  3458.3  3838.3  3993.9  4063.9  4093.9
  4123.9  4153.9  4163.9  4173.9  4183.9  4243.9  4415.6  4608.5  4638.5 4742.09
  4742.2  4761.7  4812.8  4848.7  4849.1  4901.2  4950.3  4958.5 4964.31  4964.4
  5004.7 5035.49  5035.6  5036.1  5053.8    5063  5092.9  5164.2  5198.8  5219.2
  5256.6    5275    5335    5399  5478.9 5479.01  5514.6  5555.6  5605.6  5615.6
  5645.6  5715.7
   37.23   36.03   35.03   36.53   36.13   35.43   34.93   34.63   33.83   32.03
   31.63   27.03   30.03   31.83   32.63   31.73   33.73   34.23   33.73   33.96
   36.98   36.98   37.29   37.99      38   38.92   39.93   40.11   39.98   39.98
   40.57   40.68   40.68   40.68   40.85   40.94   41.23   42.04   43.18   43.86
   45.72   45.88   46.39   46.93   48.73   45.53   33.14   31.43   32.03   32.43
   35.93   37.03
   37.23   36.03   35.03   36.53   36.13   35.43   34.93   34.63   33.83   32.03
   31.63   27.03   30.03   31.83   32.63   31.73   33.73   34.23   33.73   33.96
   33.96   34.05   34.35   34.47   34.99   36.01    36.4   33.26   31.04   33.84
   34.43   34.54   31.61   31.86   37.74   38.24   38.39   39.62   40.27   38.44
   35.08   33.43   35.63   34.73   33.62   33.62   33.14   31.43   32.03   32.43
   35.93   37.03
Abutment Skew #Up #Dn= , 2 , 2
  4964.2  4981.8
   33.71   22.54
  4964.2  4981.8
   33.84   22.67
Abutment Skew #Up #Dn= , 2 , 2
  5018.2 5035.69
   22.62   34.41
  5018.2 5035.69
   22.75   34.54
BR Coef= 1 , 1 , 0 ,1.25, 0 ,,,0.8,0,2,0,
WSPro=,,,, 1 ,,,, 0 ,,,, 0 ,,,,-1 ,-1 ,-1 , 0 , 0 , 0 , 0 , 0
BR U #Sta/Elev= 78
  2283.4    37.1  2633.4    35.9  2843.4    34.9  2893.4    36.4  3258.3      36
  3458.3    35.3  3838.3    34.8  3993.9    34.5  4063.9    33.7  4093.9    31.9
  4123.9    31.5  4153.9    26.9  4163.9    29.9  4173.9    31.7  4183.9    32.5
  4243.9    31.6  4415.6    33.6  4419.2   33.61  4467.1   33.73  4608.5    34.1
  4638.5    33.6  4688.4   33.71 4742.09   33.83  4742.2   33.83 4742.31   33.83
  4751.5   33.85  4761.7   33.92  4803.1   34.19  4812.8   34.22  4848.7   34.34
  4849.1   34.86  4863.6   35.14  4901.2   35.88  4910.7   35.95  4930.6   36.11
  4950.3   36.27  4958.5   33.13  4964.2   30.95 4964.31   30.91  4964.4   30.88
  4970.9   28.39  4981.7   22.59  4981.8   22.54  4986.9   20.16    5002   19.56
  5004.7   19.87  5015.3   21.11    5018   22.52  5018.1   22.57  5024.9   26.06
 5035.49   31.42  5035.6   31.48  5035.7   31.53  5036.1   31.73  5053.8   37.61
    5063   38.11  5092.9   38.26  5101.7   38.41  5144.1   39.12  5164.2   39.49
  5198.8   40.14  5219.2   38.31  5256.6   34.95    5275    33.3    5335    35.5
    5399    34.6  5442.6   33.98  5455.6    33.8 5478.79   33.49  5478.9   33.49
 5479.01   33.49  5514.6   33.01  5515.6      33  5555.6    31.3  5605.6    31.9
  5615.6    32.3  5645.6    35.8  5715.7    36.9
BR U #Mann= 5
  2283.4      .2  4467.1      .1  4950.3     .04  5053.8      .1  5442.6      .2
BR U Banks=4950.3,5053.8
BR D #Sta/Elev= 78
  2283.4   37.23  2633.4   36.03  2843.4   35.03  2893.4   36.53  3258.3   36.13
  3458.3   35.43  3838.3   34.93  3993.9   34.63  4063.9   33.83  4093.9   32.03
  4123.9   31.63  4153.9   27.03  4163.9   30.03  4173.9   31.83  4183.9   32.63
  4243.9   31.73  4415.6   33.73  4419.2   33.74  4467.1   33.86  4608.5   34.23
  4638.5   33.73  4688.4   33.84 4742.09   33.96  4742.2   33.96 4742.31   33.96
  4751.5   33.98  4761.7   34.05  4803.1   34.32  4812.8   34.35  4848.7   34.47
  4849.1   34.99  4863.6   35.27  4901.2   36.01  4910.7   36.08  4930.6   36.24
  4950.3    36.4  4958.5   33.26  4964.2   31.08 4964.31   31.04  4964.4   31.01
  4970.9   28.52  4981.7   22.72  4981.8   22.67  4986.9   20.29    5002   19.69
  5004.7      20  5015.3   21.24    5018   22.65  5018.1    22.7  5024.9   26.19
 5035.49   31.55  5035.6   31.61  5035.7   31.66  5036.1   31.86  5053.8   37.74
    5063   38.24  5092.9   38.39  5101.7   38.54  5144.1   39.25  5164.2   39.62
  5198.8   40.27  5219.2   38.44  5256.6   35.08    5275   33.43    5335   35.63
    5399   34.73  5442.6   34.11  5455.6   33.93 5478.79   33.62  5478.9   33.62
 5479.01   33.62  5514.6   33.14  5515.6   33.13  5555.6   31.43  5605.6   32.03
  5615.6   32.43  5645.6   35.93  5715.7   37.03
BR D #Mann= 5
  2283.4      .2  4467.1      .1  4950.3     .04  5053.8      .1  5442.6      .2
BR D Banks=4950.3,5053.8
BC Design=,, 0 ,, 0 ,,,,,,
BC HTab HWMax=39.96
BC Use User HTab Curves=0
BC User HTab FreeFlow(D)= 0

Type RM Length L Ch R = 1 ,11012.7 ,193,192.3,189.9
BEGIN DESCRIPTION:
Downstream Section of Bridge/Culvert/Weir
END DESCRIPTION:
XS GIS Cut Line= 6
      3153241.73     13807923.23      3154223.31     13807737.28
      3155361.45     13807415.57      3155876.21     13807559.46
      3156324.24     13807581.59      3156567.23     13807676.41
#Sta/Elev= 30
  2283.4   37.33  2843.4   35.13  2893.4   36.63  3993.9   34.73  4063.9   33.93
  4093.9   32.13  4123.9   31.73  4153.9   27.13  4163.9   30.13  4183.9   32.73
  4243.9   31.83  4467.1   33.96  4848.7   34.57  4901.2   36.11  4950.3    36.5
  4970.9   28.62  4986.9   20.39    5002   19.79  5015.3   21.34  5036.1   31.96
  5053.8   37.84  5198.8   40.37    5275   33.53    5335   35.73  5442.6   34.21
  5515.6   33.23  5555.6   31.53  5615.6   32.53  5645.6   36.03  5715.7   37.13
#Mann= 5 , 1 , 0
  2283.4      .2       0  4467.1      .1       0  4950.3     .04       0
  5053.8      .1       0  5442.6      .2       0
#XS Ineff= 2 , 0
       0  4960.2    32.5  5038.3       0    32.5
Permanent Ineff=
       F       F
Bank Sta=4950.3,5053.8
XS Rating Curve= 0 ,0
Exp/Cntr=0.5,0.3

Type RM Length L Ch R = 1 ,10820.4 ,21,21,21
BEGIN DESCRIPTION:
Upstream Section of Bridge/Culvert/Weir
END DESCRIPTION:
XS GIS Cut Line= 3
      3153853.27     13807818.77      3155357.76     13807608.64
      3156457.05     13807823.54
#Sta/Elev= 30
  2992.6   36.18  3392.6   34.79  3729.6   34.71  4112.6   33.81  4129.6   33.16
  4172.6   31.44  4202.6   27.69  4229.6    30.7  4252.6    32.1  4282.6   31.77
  4352.6   34.62  4462.6   35.03  4511.7   33.07  4711.7   32.81 4969.38    31.2
 4984.68   29.76 4987.58   27.69 4989.28   24.98 4993.28   22.45 4996.28   21.67
 5005.98    21.8 5016.08   24.93 5030.98   30.77 5047.28   31.72  5161.7   32.91
  5471.7   31.98  5491.7   31.32  5531.7   32.43  5561.7   35.56  5631.8   36.51
#Mann= 7 , 1 , 0
  2992.6     .99       0  3729.6      .2       0  4129.6     .99       0
  4229.6      .1       0 4984.68     .04       0 5030.98      .1       0
  5631.8      .2       0
#XS Ineff= 2 , 0
       0    4988      27  5020.5       0      27
Permanent Ineff=
       F       F
Bank Sta=4984.68,5030.98
XS Rating Curve= 0 ,0
Exp/Cntr=0.5,0.3

Type RM Length L Ch R = 3 ,10809.9 ,,,
BEGIN DESCRIPTION:
12" PIPELINE
END DESCRIPTION:
Bridge Culvert--1,0,-1,-1, 0
Deck Dist Width WeirC Skew NumUp NumDn MinLoCord MaxHiCord MaxSubmerge Is_Ogee
10,1,2.6,0, 58, 58, , , 0.95, 0, 1,1,,
  2992.6  3102.6  3242.6  3392.6  3729.6  3872.6  3912.6  4112.6  4129.6  4132.6
  4142.6  4172.6  4182.6  4192.6  4202.6  4212.6  4222.6  4229.6  4252.6  4282.6
  4352.6  4462.6  4492.6  4511.7  4711.7 4943.08 4969.38  4978.5 4984.68 4987.09
 4987.18 4987.58  4988.5 4988.58 4989.28 4993.28 4996.28 4998.98 5005.98 5006.68
 5016.08 5020.47 5020.58 5020.68 5024.48 5030.98 5047.28 5079.28  5161.7  5241.7
  5381.7  5391.7  5471.7  5491.7  5521.7  5531.7  5561.7  5631.8
   36.28   36.22   35.57   34.89   34.81   34.77   34.22   33.91   33.26   33.15
   32.37   31.54   30.72   29.46   27.79   28.85   30.38    30.8    32.2   31.87
   34.72   35.13   33.45   33.17   32.91   31.45    31.3   30.45   29.87   28.15
   28.09    27.8   26.33   27.65   27.65   27.64   27.64   27.63   27.62   27.62
    27.6   27.59   27.59   26.98   28.59   30.87   31.82   32.23   33.01   32.46
   32.48   32.17   32.08   31.42   32.02   32.53   35.66   36.61
   36.28   36.22   35.57   34.89   34.81   34.77   34.22   33.91   33.26   33.15
   32.37   31.54   30.72   29.46   27.79   28.85   30.38    30.8    32.2   31.87
   34.72   35.13   33.45   33.17   32.91   31.45    31.3   30.44   29.86   28.14
   28.08   27.79   26.32   26.65   26.65   26.64   26.64   26.63   26.62   26.62
    26.6   26.89   26.94   26.98   28.59   30.87   31.82   32.23   33.01   32.46
   32.48   32.17   32.08   31.42   32.02   32.53   35.66   36.61
  2992.6  3102.6  3242.6  3392.6  3729.6  3872.6  3912.6  4112.6  4129.6  4132.6
  4142.6  4172.6  4182.6  4192.6  4202.6  4212.6  4222.6  4229.6  4252.6  4282.6
  4352.6  4462.6  4492.6  4511.7  4711.7 4943.08 4969.38  4978.5 4984.68 4987.09
 4987.18 4987.58  4988.5 4988.58 4989.28 4993.28 4996.28 4998.98 5005.98 5006.68
 5016.08 5020.47 5020.58 5020.68 5024.48 5030.98 5047.28 5079.28  5161.7  5241.7
  5381.7  5391.7  5471.7  5491.7  5521.7  5531.7  5561.7  5631.8
   36.28   36.22   35.57   34.89   34.81   34.77   34.22   33.91   33.26   33.15
   32.37   31.54   30.72   29.46   27.79   28.85   30.38    30.8    32.2   31.87
   34.72   35.13   33.45   33.17   32.91   31.45    31.3   30.45   29.87   28.15
   28.09    27.8   26.33   27.65   27.65   27.64   27.64   27.63   27.62   27.62
    27.6   27.59   27.59   26.98   28.59   30.87   31.82   32.23   33.01   32.46
   32.48   32.17   32.08   31.42   32.02   32.53   35.66   36.61
   36.28   36.22   35.57   34.89   34.81   34.77   34.22   33.91   33.26   33.15
   32.37   31.54   30.72   29.46   27.79   28.85   30.38    30.8    32.2   31.87
   34.72   35.13   33.45   33.17   32.91   31.45    31.3   30.44   29.86   28.14
   28.08   27.79   26.32   26.65   26.65   26.64   26.64   26.63   26.62   26.62
    26.6   26.89   26.94   26.98   28.59   30.87   31.82   32.23   33.01   32.46
   32.48   32.17   32.08   31.42   32.02   32.53   35.66   36.61
Pier Skew, UpSta & Num, DnSta & Num=  ,4991.3, 2 ,4991.3, 2 , 0 , 0 , 0 ,,
       2       2
   22.18   27.65
       2       2
   22.18   27.65
Pier Skew, UpSta & Num, DnSta & Num=  ,5016.1, 2 ,5016.1, 2 , 0 , 0 , 0 ,,
       2       2
   23.76   27.67
       2       2
   23.76   27.67
BR Coef= 1 , 1 , 0 ,1.25, 0 ,,,0.8,0,2,0,
WSPro=,,,, 1 ,,,, 0 ,,,, 0 ,,,,-1 ,-1 ,-1 , 0 , 0 , 0 , 0 , 0
BR U #Sta/Elev= 58
  2992.6   36.28  3102.6   36.22  3242.6   35.57  3392.6   34.89  3729.6   34.81
  3872.6   34.77  3912.6   34.22  4112.6   33.91  4129.6   33.26  4132.6   33.15
  4142.6   32.37  4172.6   31.54  4182.6   30.72  4192.6   29.46  4202.6   27.79
  4212.6   28.85  4222.6   30.38  4229.6    30.8  4252.6    32.2  4282.6   31.87
  4352.6   34.72  4462.6   35.13  4492.6   33.45  4511.7   33.17  4711.7   32.91
 4943.08   31.45 4969.38    31.3  4978.5   30.44 4984.68   29.86 4987.09   28.14
 4987.18   28.08 4987.58   27.79  4988.5   26.32 4988.58    26.2 4989.28   25.08
 4993.28   22.55 4996.28   21.77 4998.98   21.93 5005.98    21.9 5006.68   22.48
 5016.08   25.03 5020.47   26.89 5020.58   26.94 5020.68   26.98 5024.48   28.59
 5030.98   30.87 5047.28   31.82 5079.28   32.23  5161.7   33.01  5241.7   32.46
  5381.7   32.48  5391.7   32.17  5471.7   32.08  5491.7   31.42  5521.7   32.02
  5531.7   32.53  5561.7   35.66  5631.8   36.61
BR U #Mann= 7
  2992.6     .99  3729.6      .2  4129.6     .99  4229.6      .1 4984.68     .04
 5030.98      .1  5631.8      .2
BR U Banks=4984.68,5030.98
BR D #Sta/Elev= 58
  2992.6   36.28  3102.6   36.22  3242.6   35.57  3392.6   34.89  3729.6   34.81
  3872.6   34.77  3912.6   34.22  4112.6   33.91  4129.6   33.26  4132.6   33.15
  4142.6   32.37  4172.6   31.54  4182.6   30.72  4192.6   29.46  4202.6   27.79
  4212.6   28.85  4222.6   30.38  4229.6    30.8  4252.6    32.2  4282.6   31.87
  4352.6   34.72  4462.6   35.13  4492.6   33.45  4511.7   33.17  4711.7   32.91
 4943.08   31.45 4969.38    31.3  4978.5   30.44 4984.68   29.86 4987.09   28.14
 4987.18   28.08 4987.58   27.79  4988.5   26.32 4988.58    26.2 4989.28   25.08
 4993.28   22.55 4996.28   21.77 4998.98   21.93 5005.98    21.9 5006.68   22.48
 5016.08   25.03 5020.47   26.89 5020.58   26.94 5020.68   26.98 5024.48   28.59
 5030.98   30.87 5047.28   31.82 5079.28   32.23  5161.7   33.01  5241.7   32.46
  5381.7   32.48  5391.7   32.17  5471.7   32.08  5491.7   31.42  5521.7   32.02
  5531.7   32.53  5561.7   35.66  5631.8   36.61
BR D #Mann= 7
  2992.6     .99  3729.6      .2  4129.6     .99  4229.6      .1 4984.68     .04
 5030.98      .1  5631.8      .2
BR D Banks=4984.68,5030.98
BC Design=,, 0 ,, 0 ,,,,,,
BC HTab HWMax=36.51
BC Use User HTab Curves=0
BC User HTab FreeFlow(D)= 0

Type RM Length L Ch R = 1 ,10799.4 ,94.2,82.8,68.1
BEGIN DESCRIPTION:
Downstream Section of Bridge/Culvert/Weir
END DESCRIPTION:
XS GIS Cut Line= 3
      3153848.64     13807839.26      3155353.14     13807629.12
      3156452.43     13807844.02
#Sta/Elev= 30
  2992.6   36.17  3392.6   34.78  3729.6    34.7  4112.6    33.8  4129.6   33.15
  4172.6   31.43  4202.6   27.68  4229.6   30.69  4252.6   32.09  4282.6   31.76
  4352.6   34.61  4462.6   35.02  4511.7   33.06  4711.7    32.8 4969.38   31.19
 4984.68   29.75 4987.58   27.68 4989.28   24.97 4993.28   22.44 4996.28   21.66
 5005.98   21.79 5016.08   24.92 5030.98   30.76 5047.28   31.71  5161.7    32.9
  5471.7   31.97  5491.7   31.31  5531.7   32.42  5561.7   35.55  5631.8    36.5
#Mann= 7 , 1 , 0
  2992.6     .99       0  3729.6      .2       0  4129.6     .99       0
  4229.6      .1       0 4984.68     .04       0 5030.98      .1       0
  5631.8      .2       0
#XS Ineff= 2 , 0
       0    4988      27  5020.5       0      27
Permanent Ineff=
       F       F
Bank Sta=4984.68,5030.98
XS Rating Curve= 0 ,0
Exp/Cntr=0.5,0.3

Type RM Length L Ch R = 1 ,10716.6 ,685.1,685.2,716.1
BEGIN DESCRIPTION:
Cross Section 10716.6
END DESCRIPTION:
XS GIS Cut Line= 6
      3153912.91     13807931.91      3154664.96     13807960.96
      3155356.74     13807840.65      3155645.48      13807822.6
      3155898.13     13807852.68      3156439.52     13807876.74
#Sta/Elev= 30
  3111.9    36.4  3769.9   35.88  4169.9   33.08  4224.5    31.1  4244.5    28.7
  4269.9   30.69  4304.5    32.3  4364.5    32.3  4384.5    33.7  4444.5    33.6
  4484.5      31  4576.7    35.3  4616.7    34.4  4666.7    35.8  4696.7    34.7
  4726.7    35.9  4846.7    33.4    4946    33.3  4978.5   30.27  4985.8   26.79
  4993.1   21.07  5006.7   20.73  5007.1   21.75  5019.4   28.66  5046.8   32.45
  5440.5    34.1  5490.5    31.6  5530.5    32.3  5570.5    35.7  5652.4    36.6
#Mann= 7 , 1 , 0
  3111.9     .99       0  3769.9      .2       0  4169.9     .99       0
  4269.9      .1       0  4978.5     .04       0  5019.4      .1       0
  5652.4      .2       0
Bank Sta=4978.5,5019.4
XS Rating Curve= 0 ,0
Exp/Cntr=0.3,0.1

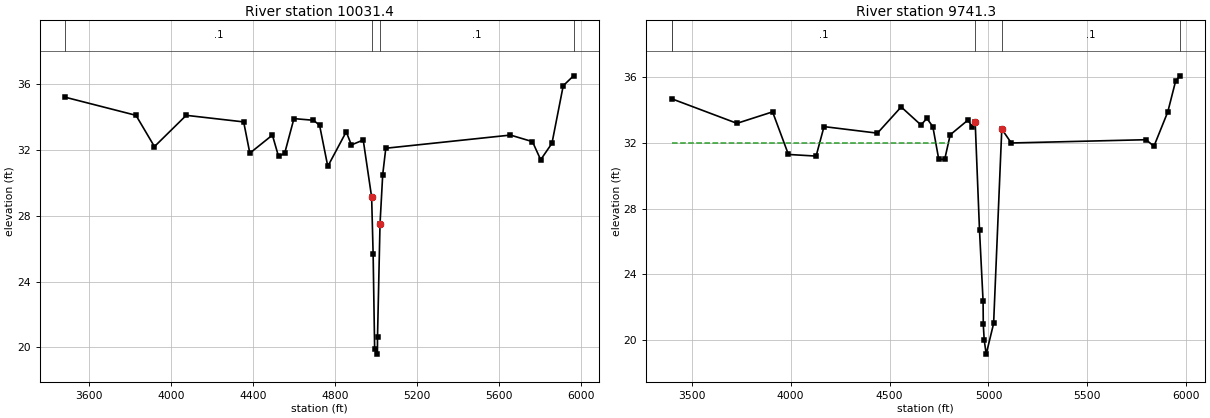
Type RM Length L Ch R = 1 ,10031.4 ,416.1,290.1,255.2
BEGIN DESCRIPTION:
Cross Section 10031.4-Interpolated
END DESCRIPTION:
XS GIS Cut Line= 5
       3154087.5      13808842.6      3155440.28     13808490.51
      3155709.93     13808448.67      3156119.07     13808048.83
      3156342.23     13807974.44
#Sta/Elev= 30
  3484.7    35.2  3829.7    34.1  3919.7    32.2  4074.7    34.1  4354.7    33.7
  4384.7    31.8  4494.7    32.9  4524.7    31.6  4554.7    31.8  4599.7    33.9
  4694.7    33.8  4724.7    33.5  4764.7      31  4854.7    33.1  4879.7    32.3
  4937.5    32.6  4978.5   29.13  4985.8   25.65  4993.1   19.93  5006.7   19.59
  5007.1   20.61  5019.4   27.52  5032.5    30.5  5047.5    32.1  5655.4    32.9
  5762.5    32.5  5802.5    31.4  5857.5    32.4  5912.5    35.9  5962.7    36.5
#Mann= 4 , 1 , 0
  3484.7      .1       0  4978.5     .04       0  5019.4      .1       0
  5962.7      .2       0
Bank Sta=4978.5,5019.4
XS Rating Curve= 0 ,0
Exp/Cntr=0.3,0.1

Type RM Length L Ch R = 1 ,9741.3  ,91.6,125.4,122
BEGIN DESCRIPTION:
Cross Section 9741.3-Interpolated
END DESCRIPTION:
XS GIS Cut Line= 5
      3154568.36      13809962.8       3155488.5     13808897.37
       3155691.9     13808664.92      3156103.54     13808122.52
      3156263.35     13808059.56
#Sta/Elev= 30
  3398.9    34.7  3728.9    33.2  3908.9    33.9  3988.9    31.3  4128.9    31.2
  4168.9      33  4438.9    32.6  4558.9    34.2  4658.9    33.1  4688.9    33.5
  4718.9      33  4748.9      31  4778.9      31  4806.7    32.5  4896.7    33.4
  4916.7      33  4932.9   33.29  4954.8   26.68  4972.9   22.34  4973.9   20.93
  4978.5   19.98  4988.6   19.11  5026.1   20.98  5067.4   32.85  5115.5      32
  5796.5    32.2  5836.5    31.8  5906.5    33.9  5946.5    35.8  5968.2    36.1
#Mann= 5 , 1 , 0
  3398.9      .2       0  3398.9      .1       0  4932.9     .04       0
  5067.4      .1       0  5968.2      .2       0
#XS Ineff= 2 , 0
       0  4796.5      32               0
Permanent Ineff=
       F       F
Bank Sta=4932.9,5067.4
XS Rating Curve= 0 ,0
Exp/Cntr=0.5,0.3