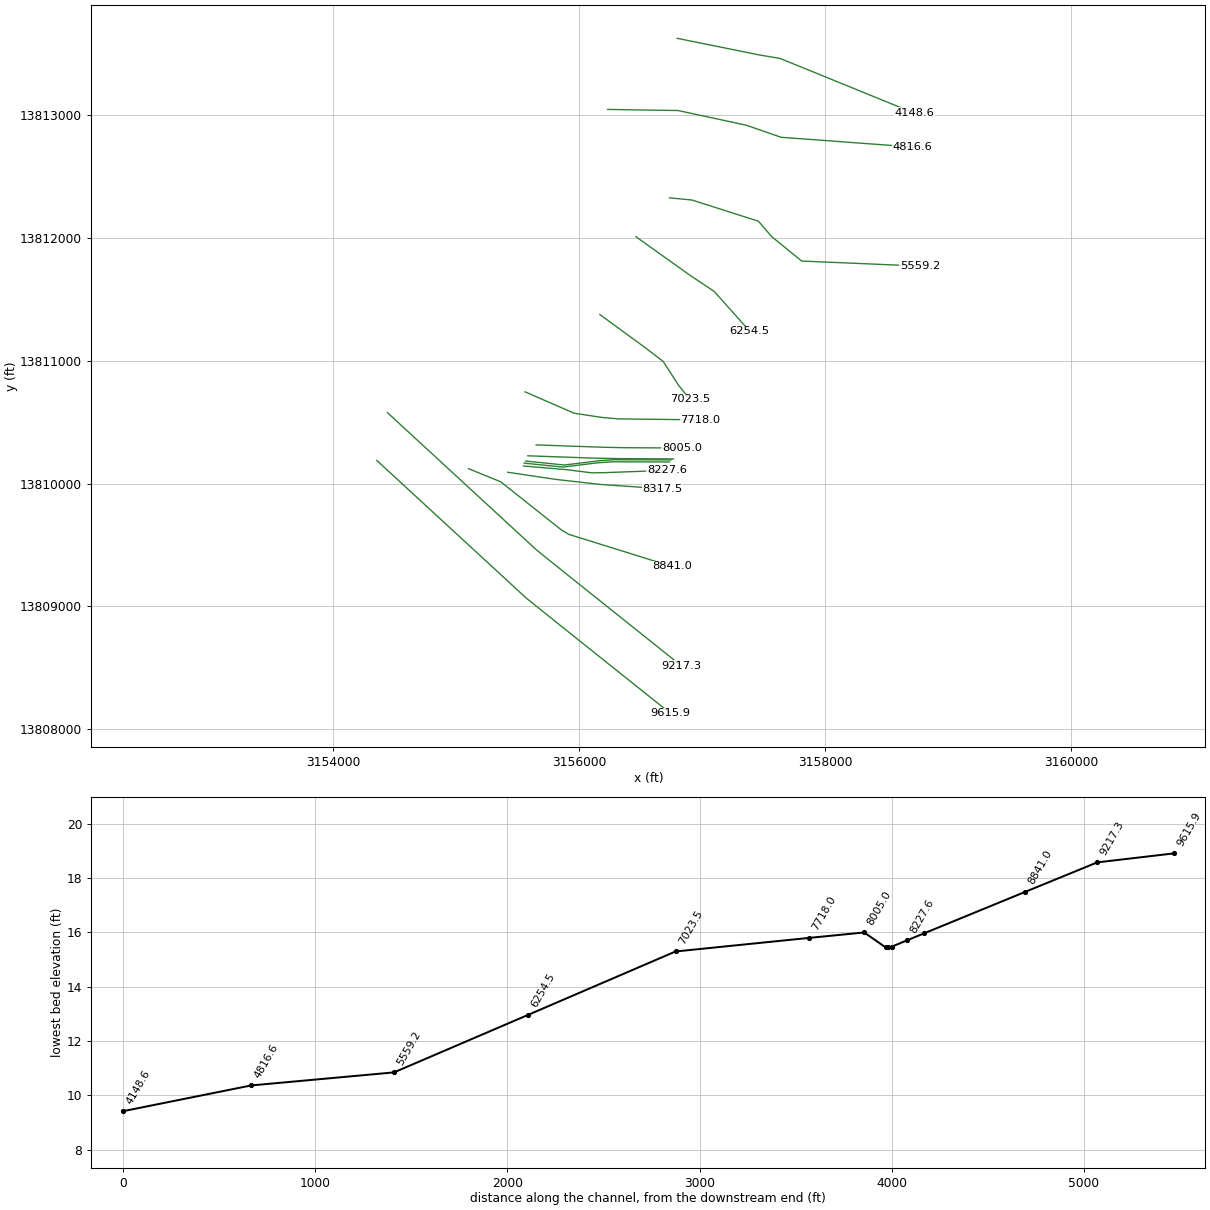
HEC-RAS study C106-01-00.PRJ: C106-01-00

--- C106-01-00.g01 (geometry) --- (continued)

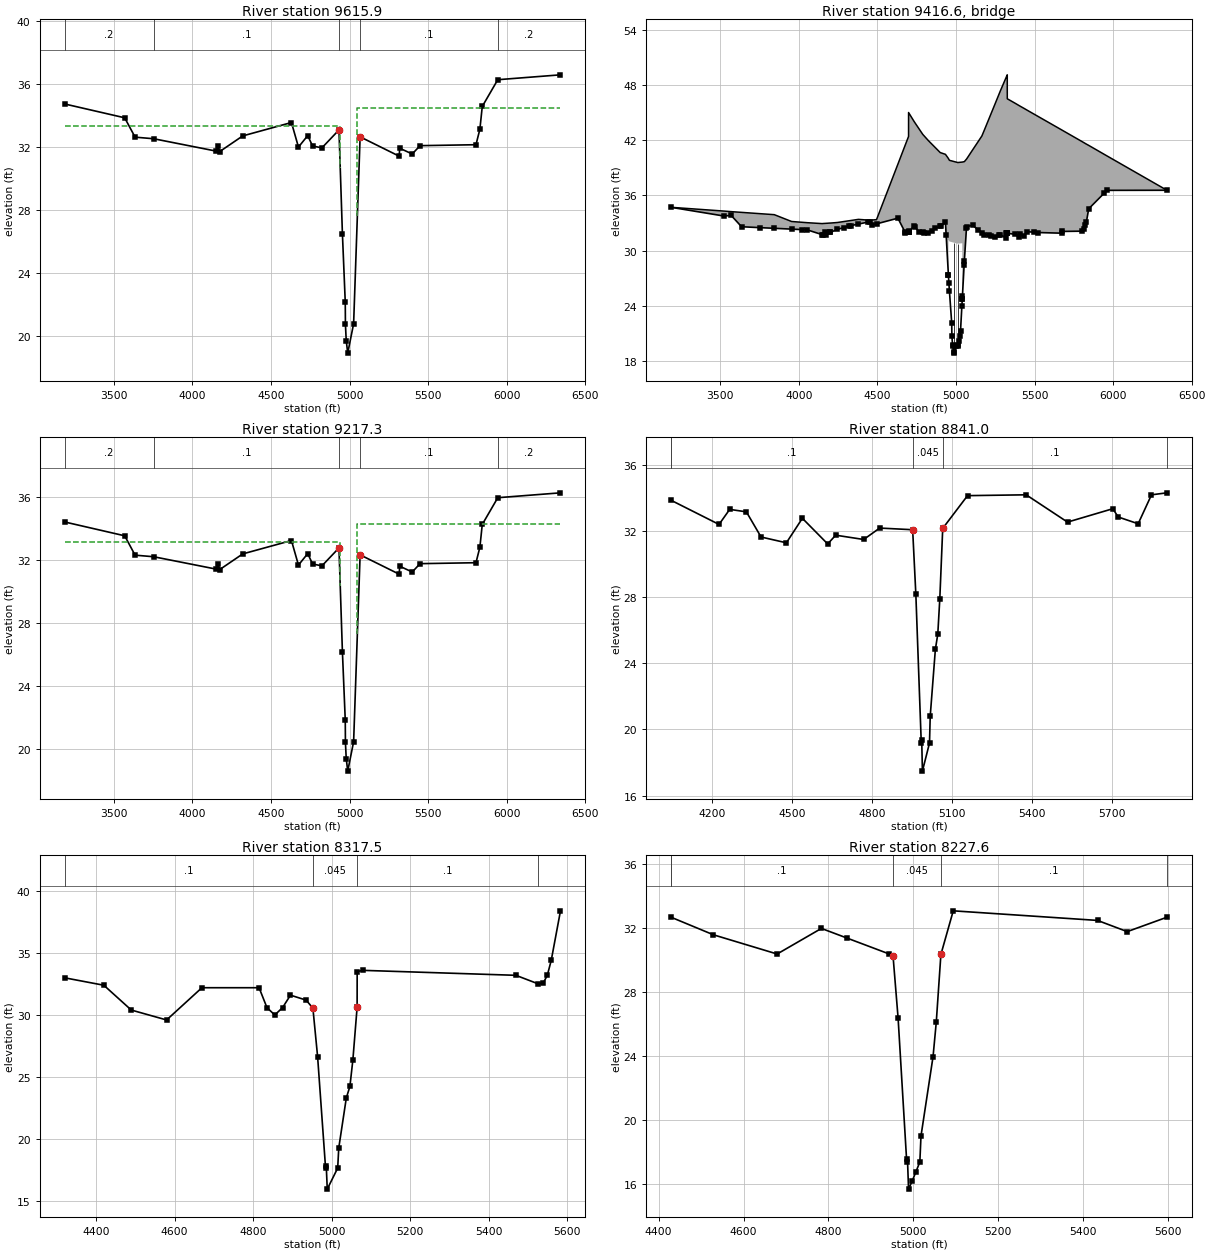
Type RM Length L Ch R = 1 ,9615.9  ,398.6,398.6,398.6
BEGIN DESCRIPTION:
Upstream Section of Bridge/Culvert/Weir
END DESCRIPTION:
XS GIS Cut Line= 4
      3154355.04     13810189.06      3155568.82     13809068.65
      3155837.49      13808852.4      3156742.88     13808128.09
#Sta/Elev= 30
  3186.5   34.73  3569.1   33.85  3635.2   32.62  3753.3   32.52  4153.2   31.73
  4163.2   32.09  4173.2    31.7  4320.4    32.7  4630.4   33.55    4675   31.99
    4734   32.72  4764.7   32.06  4824.3   31.94  4932.9   33.08  4954.8   26.47
  4972.9   22.13  4973.9   20.72 4979.13   19.69  4988.6    18.9  5026.1   20.77
  5067.4   32.64  5316.4   31.41    5319   31.92    5399   31.55    5449   32.08
  5804.8   32.14  5829.8   33.13  5844.8   34.57  5943.6   36.27  6342.7   36.58
#Mann= 5 , 1 , 0
  3186.5      .2       0  3753.3      .1       0  4932.9     .04       0
  5067.4      .1       0  5943.6      .2       0
#XS Ineff= 2 , 0
       0    4941    33.3    5050       0    34.5
Permanent Ineff=
       F       F
Bank Sta=4932.9,5067.4
XS Rating Curve= 0 ,0
Exp/Cntr=0.5,0.3

Type RM Length L Ch R = 3 ,9416.6  ,,,
BEGIN DESCRIPTION:
Highway 45, SKEW ANGLE OF 40 DEGREES
Structure ID: C61-4
END DESCRIPTION:
Bridge Culvert--1,0,-1,-1, 0
Deck Dist Width WeirC Skew NumUp NumDn MinLoCord MaxHiCord MaxSubmerge Is_Ogee
10,378.6,2.6,0, 60, 60, , , 0.95, 0, 1,1,,
  3186.5  3524.1  3569.1  3635.2  3843.6  3953.6  4053.2  4148.6  4153.2  4163.2
  4173.2  4198.2  4200.4  4245.4  4379.2  4450.4  4465.4  4494.2  4630.4    4675
 4698.09  4698.2    4734  4764.7  4788.9  4824.3  4899.7  4932.9 4951.71  4951.8
  4958.3  5011.4 5039.93 5040.04  5053.3  5067.4  5106.9  5164.7  5180.1  5247.1
  5282.9  5316.4    5319  5326.2  5326.4 5326.51    5374    5399    5409    5434
    5449  5671.8  5676.8  5804.8  5814.8  5819.8  5829.8  5844.8  5960.8  6342.7
   34.71    34.3   34.24   34.16   33.91   33.17   33.04   32.94   32.95   32.96
   32.97      33      33   33.06    33.4   33.31   33.33   33.37    39.4   41.38
    42.4      45   44.01   43.23   42.62   41.95   40.65   40.46   40.01      40
   39.81   39.57   39.62   39.62   39.67   39.95   40.97   42.45   43.08   45.87
   47.37    48.7    48.8   49.09   49.09   46.49   46.03   45.78   45.68   45.44
   45.29   43.12   43.07   41.82   41.72   41.67   41.57   41.43   40.29   36.56
   34.71   33.76   33.83    32.6   32.43   32.34   32.26   31.74   31.71   32.07
   31.68   32.06   31.99   32.31   32.89   33.14   32.78   32.91   33.53   31.97
   32.08   32.08    32.7   32.04   31.98   31.92   32.64   33.06   27.38   31.19
      31   30.76   30.81   24.77    28.9   32.62   32.75   31.95   31.75    31.5
   31.73   31.39    31.9   31.89   31.89   31.88   31.79   31.53   31.86   31.64
   32.06    31.9   32.09   32.12    32.4   32.77   33.11   34.55   36.55   36.56
  3186.5  3524.1  3569.1  3635.2  3843.6  3953.6  4053.2  4148.6  4153.2  4163.2
  4173.2  4198.2  4200.4  4245.4  4379.2  4450.4  4465.4  4494.2  4630.4    4675
 4698.09  4698.2    4734  4764.7  4788.9  4824.3  4899.7  4932.9 4951.71  4951.8
  4958.3  5011.4 5039.93 5040.04  5053.3  5067.4  5106.9  5164.7  5180.1  5247.1
  5282.9  5316.4    5319  5326.2  5326.4 5326.51    5374    5399    5409    5434
    5449  5671.8  5676.8  5804.8  5814.8  5819.8  5829.8  5844.8  5960.8  6342.7
   34.71    34.3   34.24   34.16   33.91   33.17   33.04   32.94   32.95   32.96
   32.97      33      33   33.06    33.4   33.31   33.33   33.37    39.4   41.38
    42.4      45   44.01   43.23   42.62   41.95   40.65   40.46   40.01      40
   39.81   39.57   39.62   39.62   39.67   39.95   40.97   42.45   43.08   45.87
   47.37    48.7    48.8   49.09   49.09   46.49   46.03   45.78   45.68   45.44
   45.29   43.12   43.07   41.82   41.72   41.67   41.57   41.43   40.29   36.56
   34.43   33.48   33.55   32.32   32.15   32.06   31.98   31.46   31.43   31.79
    31.4   31.78   31.71   32.03   32.61   32.86    32.5   32.63   33.25   31.69
    31.8    31.8   32.42   31.76    31.7   31.64   32.36   32.78    27.1   30.91
   30.72   30.48   30.53   24.49   28.62   32.34   32.47   31.67   31.47   31.22
   31.45   31.11   31.62   31.61   31.61    31.6   31.51   31.25   31.58   31.36
   31.78   31.62   31.81   31.84   32.12   32.49   32.83   34.27   36.27   36.28
Pier Skew, UpSta & Num, DnSta & Num=  ,4988.5, 2 ,4988.5, 2 , 0 , 0 , 0 ,,
     1.5     1.5
    17.9   31.86
     1.5     1.5
   17.62   31.58
Pier Skew, UpSta & Num, DnSta & Num=  ,5015, 2 ,5015, 2 , 0 , 0 , 0 ,,
     1.5     1.5
   18.88   31.77
     1.5     1.5
    18.6   31.49
Abutment Skew #Up #Dn= , 2 , 2
  4951.6 4979.13
   31.19   19.67
  4951.6 4979.13
   30.91   19.39
Abutment Skew #Up #Dn= , 2 , 2
 5037.58 5040.13
   24.01   30.81
 5037.58 5040.13
   23.73   30.53
BR Coef= 1 , 1 , 0 ,1.25, 0 ,,,0.8,0,2,0,
WSPro=,,,, 1 ,,,, 0 ,,,, 0 ,,,,-1 ,-1 ,-1 , 0 , 0 , 0 , 0 , 0
BR U #Sta/Elev= 100
  3186.5   34.71  3524.1   33.76  3569.1   33.83  3635.2    32.6  3753.3    32.5
  3843.6   32.43  3953.6   32.34  4018.6   32.29  4053.2   32.26  4148.6   31.74
  4153.2   31.71  4163.2   32.07  4173.2   31.68  4198.2   32.06  4200.4   31.99
  4245.4   32.31  4284.2    32.5  4320.4   32.68  4334.2   32.73  4379.2   32.89
  4439.2    33.1  4450.4   33.14  4465.4   32.78  4494.2   32.91  4630.4   33.53
  4674.9   32.04    4675   31.97 4698.09   32.08  4698.2   32.08 4698.31   32.08
  4698.6   32.08  4703.9   32.11    4734    32.7  4739.4   32.58  4764.7   32.04
  4788.9   31.98  4795.6   31.96  4824.3   31.92  4846.7   32.17  4869.3   32.42
  4899.7   32.64  4903.8   32.67  4932.9   33.06  4937.4    31.7 4951.71   27.38
  4951.8   27.36  4954.8   26.45  4958.3   25.61  4972.9   22.11  4973.9    20.7
  4978.5   19.75 4979.13   19.67  4985.1   18.96  4988.6   18.88  5002.4   19.66
  5011.4    19.7    5012   19.74  5019.5    20.2  5026.1   20.75  5028.8   21.28
 5037.58   24.01 5039.93   24.74 5040.04   24.77  5041.1    25.1    5052    28.5
  5053.3    28.9  5066.6   32.41  5067.4   32.62  5106.9   32.75    5141   32.26
  5164.7   31.95  5180.1   31.75  5212.5   31.66  5220.3   31.62  5247.1    31.5
  5273.2   31.67  5282.9   31.73  5316.4   31.39    5319    31.9  5326.2   31.89
 5326.29   31.89  5326.4   31.89 5326.51   31.88    5374   31.79    5399   31.53
    5409   31.86    5434   31.64    5449   32.06  5496.8   32.01  5521.8   31.97
  5671.8    31.9  5676.8   32.09  5804.8   32.12  5814.8    32.4  5819.8   32.77
  5829.8   33.11  5844.8   34.55  5943.6   36.25  5960.8   36.55  6342.7   36.56
BR U #Mann= 5
  3186.5      .2  3753.3      .1  4932.9     .04  5067.4      .1  5943.6      .2
BR U Banks=4932.9,5067.4
BR D #Sta/Elev= 100
  3186.5   34.43  3524.1   33.48  3569.1   33.55  3635.2   32.32  3753.3   32.22
  3843.6   32.15  3953.6   32.06  4018.6   32.01  4053.2   31.98  4148.6   31.46
  4153.2   31.43  4163.2   31.79  4173.2    31.4  4198.2   31.78  4200.4   31.71
  4245.4   32.03  4284.2   32.22  4320.4    32.4  4334.2   32.45  4379.2   32.61
  4439.2   32.82  4450.4   32.86  4465.4    32.5  4494.2   32.63  4630.4   33.25
  4674.9   31.76    4675   31.69 4698.09    31.8  4698.2    31.8 4698.31    31.8
  4698.6    31.8  4703.9   31.83    4734   32.42  4739.4    32.3  4764.7   31.76
  4788.9    31.7  4795.6   31.68  4824.3   31.64  4846.7   31.89  4869.3   32.14
  4899.7   32.36  4903.8   32.39  4932.9   32.78  4937.4   31.42 4951.71    27.1
  4951.8   27.08  4954.8   26.17  4958.3   25.33  4972.9   21.83  4973.9   20.42
  4978.5   19.47 4979.13   19.39  4985.1   18.68  4988.6    18.6  5002.4   19.38
  5011.4   19.42    5012   19.46  5019.5   19.92  5026.1   20.47  5028.8      21
 5037.58   23.73 5039.93   24.46 5040.04   24.49  5041.1   24.82    5052   28.22
  5053.3   28.62  5066.6   32.13  5067.4   32.34  5106.9   32.47    5141   31.98
  5164.7   31.67  5180.1   31.47  5212.5   31.38  5220.3   31.34  5247.1   31.22
  5273.2   31.39  5282.9   31.45  5316.4   31.11    5319   31.62  5326.2   31.61
 5326.29   31.61  5326.4   31.61 5326.51    31.6    5374   31.51    5399   31.25
    5409   31.58    5434   31.36    5449   31.78  5496.8   31.73  5521.8   31.69
  5671.8   31.62  5676.8   31.81  5804.8   31.84  5814.8   32.12  5819.8   32.49
  5829.8   32.83  5844.8   34.27  5943.6   35.97  5960.8   36.27  6342.7   36.28
BR D #Mann= 5
  3186.5      .2  3753.3      .1  4932.9     .04  5067.4      .1  5943.6      .2
BR D Banks=4932.9,5067.4
BC Design=,, 0 ,, 0 ,,,,,,
BC HTab HWMax=36.58
BC Use User HTab Curves=0
BC User HTab FreeFlow(D)= 0

Type RM Length L Ch R = 1 ,9217.3  ,336.2,376.3,409.8
BEGIN DESCRIPTION:
Downstream Section of Bridge/Culvert/Weir
END DESCRIPTION:
XS GIS Cut Line= 4
      3154441.95     13810578.07      3155655.74     13809457.65
      3155924.41      13809241.4       3156829.8      13808517.1
#Sta/Elev= 30
  3186.5    34.4  3569.1   33.52  3635.2   32.29  3753.3   32.19  4153.2    31.4
  4163.2   31.76  4173.2   31.37  4320.4   32.37  4630.4   33.22    4675   31.66
    4734   32.39  4764.7   31.73  4824.3   31.61  4932.9   32.75  4954.8   26.14
  4972.9    21.8  4973.9   20.39 4979.13   19.36  4988.6   18.57  5026.1   20.44
  5067.4   32.31  5316.4   31.08    5319   31.59    5399   31.22    5449   31.75
  5804.8   31.81  5829.8    32.8  5844.8   34.24  5943.6   35.94  6342.7   36.25
#Mann= 5 , 1 , 0
  3186.5      .2       0  3753.3      .1       0  4932.9     .04       0
  5067.4      .1       0  5943.6      .2       0
#XS Ineff= 2 , 0
       0    4941    33.1    5050       0    34.3
Permanent Ineff=
       F       F
Bank Sta=4932.9,5067.4
XS Rating Curve= 0 ,0
Exp/Cntr=0.5,0.3

Type RM Length L Ch R = 1 ,8841.0  ,459.5,523.5,515.3
BEGIN DESCRIPTION:
Cross Section 8841.0-Interpolated
END DESCRIPTION:
XS GIS Cut Line= 5
      3155101.19     13810121.77      3155362.73     13810014.78
      3155856.08     13809622.47      3155915.52     13809586.81
      3156753.63     13809325.27
#Sta/Elev= 30
    4046   33.85    4226   32.39    4266    33.3  4328.6   33.15  4383.6   31.63
  4478.6   31.28  4538.6   32.76  4633.6   31.21  4663.6   31.74  4768.6   31.48
  4828.6   32.17 4952.28   32.07 4964.28   28.16 4984.58   19.18 4986.28   19.37
 4988.88   17.48 5015.48   19.18 5018.18    20.8 5037.48   24.84 5046.58   25.76
 5054.18   27.91 5065.08   32.15  5158.2   34.13  5378.2   34.18  5533.2   32.53
  5703.2   33.34  5723.2   32.84  5798.2   32.43  5848.2   34.18  5906.2    34.3
#Mann= 5 , 1 , 0
    4046      .2       0    4046      .1       0 4952.28    .045       0
 5065.08      .1       0  5906.2      .2       0
Bank Sta=4952.28,5065.08
XS Rating Curve= 0 ,0
Exp/Cntr=0.3,0.1

Type RM Length L Ch R = 1 ,8317.5  ,86.8,89.9,103.5
BEGIN DESCRIPTION:
Cross Section 8317.5-Interpolated
END DESCRIPTION:
XS GIS Cut Line= 4
        3155420.     13810092.68      3155811.42     13810034.26
      3156173.62     13809993.37      3156676.03     13809958.31
#Sta/Elev= 30
  4319.4      33  4419.4    32.4  4489.4    30.4  4579.4    29.6  4669.4    32.2
  4815.1    32.2  4835.1    30.6  4855.1      30  4875.1    30.6  4895.1    31.6
  4935.1    31.2 4952.28   30.55 4964.28   26.64 4984.58   17.66 4986.28   17.85
 4988.88   15.96 5015.48   17.66 5018.18   19.28 5037.48   23.32 5046.58   24.24
 5054.18   26.39 5064.98   30.63  5065.1    33.5  5079.7    33.6  5469.7    33.2
  5524.9   32.53  5539.7    32.6  5549.7    33.2  5559.7    34.4  5583.3    38.4
#Mann= 4 , 1 , 0
  4319.4      .1       0 4952.28    .045       0 5064.98      .1       0
  5524.9      .2       0
#XS Ineff= 2 , 0
       0  4879.1    30.8               0
Permanent Ineff=
       F       F
Bank Sta=4952.28,5064.98
XS Rating Curve= 0 ,0
Exp/Cntr=0.3,0.1

Type RM Length L Ch R = 1 ,8227.6  ,71.3,78.5,83.5
BEGIN DESCRIPTION:
Cross Section 8227.6-Interpolated
END DESCRIPTION:
XS GIS Cut Line= 5
      3155548.66     13810143.63      3155901.65     13810113.23
      3156102.64     13810087.89      3156210.73     13810089.58
      3156714.04     13810108.16
#Sta/Elev= 22
  4429.2    32.7  4529.2    31.6  4679.2    30.4  4783.5      32  4843.5    31.4
  4943.5    30.4 4952.28   30.29 4964.28   26.38 4984.58    17.4 4986.28   17.59
 4988.88    15.7 4997.48   16.21 5006.38   16.79 5015.48    17.4 5018.18   19.02
 5046.58   23.98 5054.18   26.13 5065.08   30.37  5094.2    33.1  5434.2    32.5
  5504.2    31.8  5597.8    32.7
#Mann= 5 , 1 , 0
  4429.2      .2       0  4429.2      .1       0 4952.28    .045       0
 5065.08      .1       0  5597.8      .2       0
#XS Ineff= 2 , 0
       0                  5434.2       0    32.5
Permanent Ineff=
       F       F
Bank Sta=4952.28,5065.08
XS Rating Curve= 0 ,0
Exp/Cntr=0.5,0.3

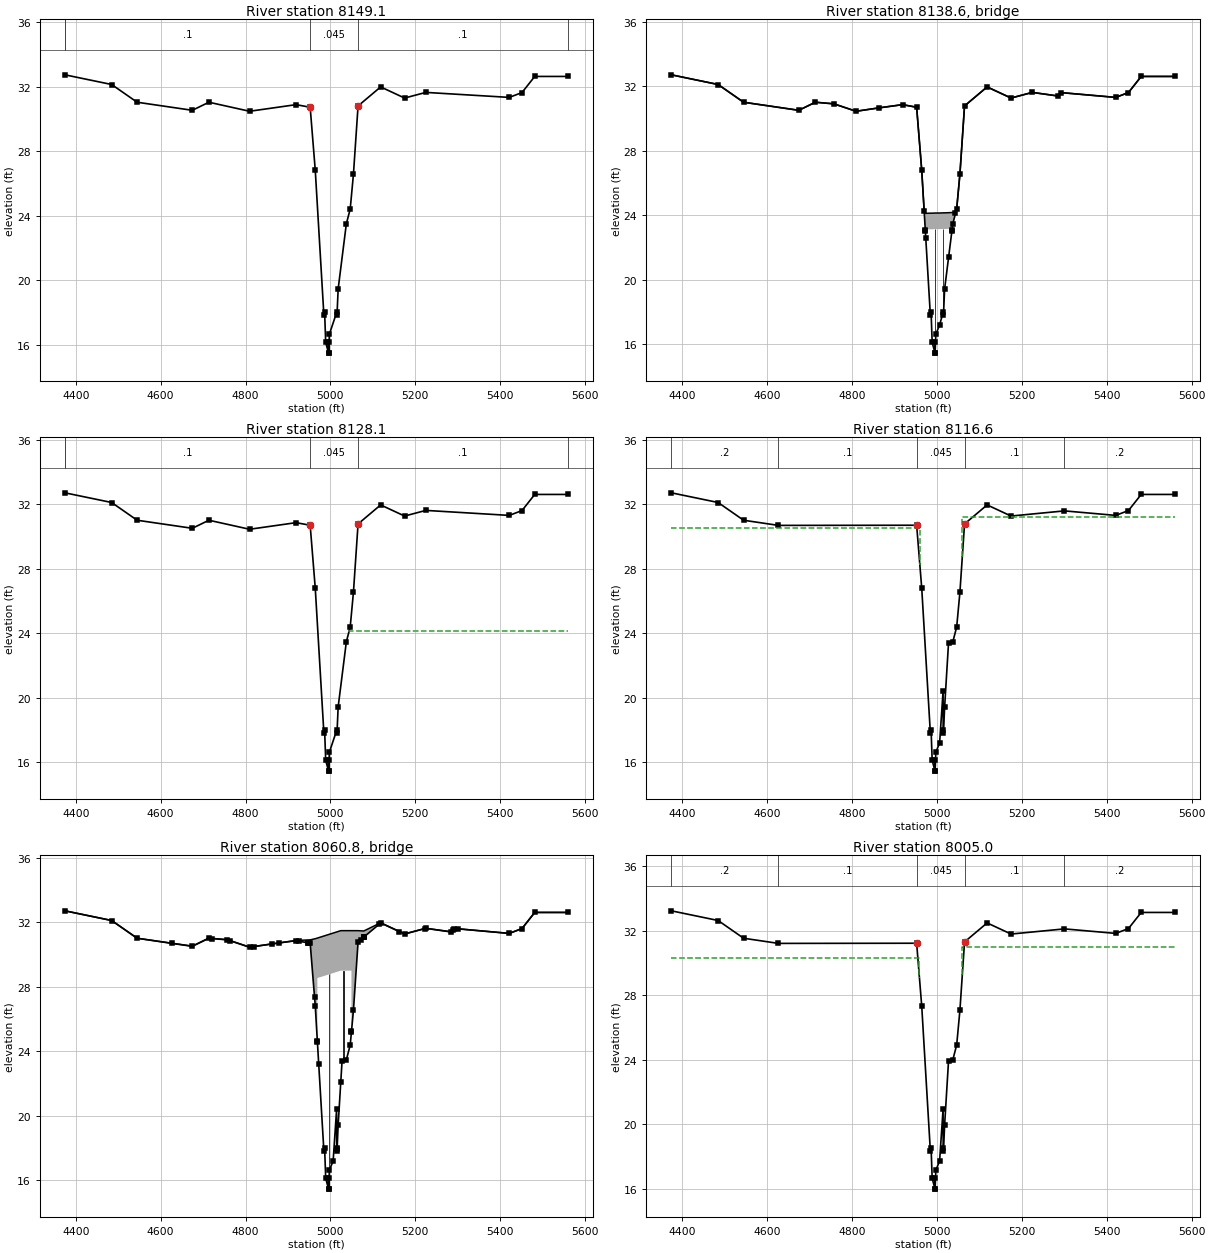
Type RM Length L Ch R = 1 ,8149.1  ,21,21,21
BEGIN DESCRIPTION:
Upstream Section of Bridge/Culvert/Weir
END DESCRIPTION:
XS GIS Cut Line= 5
      3155553.02     13810166.74      3155867.75     13810134.79
      3156152.12     13810169.94      3156271.94     13810177.93
      3156734.74     13810176.25
#Sta/Elev= 30
  4374.7   32.73  4484.7   32.13  4544.7   31.03  4674.7   30.53  4713.8   31.03
 4809.58   30.47 4919.08   30.88 4952.28   30.72 4964.28   26.81 4984.58   17.83
 4986.28   18.02 4988.88   16.13 4995.48   15.49 4995.68   16.15 4995.78   15.47
 4997.48   16.64 5014.88   18.01 5015.48   17.83 5018.18   19.45 5037.48   23.49
 5046.58   24.41 5054.18   26.56 5065.08    30.8 5118.28   31.98 5174.68   31.29
 5224.68   31.64  5421.2   31.33  5451.2   31.63  5481.2   32.63  5559.7   32.63
#Mann= 5 , 1 , 0
  4374.7      .2       0  4374.7      .1       0 4952.28    .045       0
 5065.08      .1       0  5559.7      .2       0
#XS Ineff= 2 , 0
       0  4969.9    24.2  5043.6       0    24.1
Permanent Ineff=
       F       F
Bank Sta=4952.28,5065.08
XS Rating Curve= 0 ,0
Exp/Cntr=0.5,0.3

Type RM Length L Ch R = 3 ,8138.6  ,,,
BEGIN DESCRIPTION:
12" PIPELINE
END DESCRIPTION:
Bridge Culvert--1,0,-1,-1, 0
Deck Dist Width WeirC Skew NumUp NumDn MinLoCord MaxHiCord MaxSubmerge Is_Ogee
10,1,2.6,0, 43, 43, , , 0.95, 0, 1,1,,
  4374.7  4484.7  4544.7  4674.7  4713.8 4757.48 4809.58 4863.48 4919.08 4952.28
 4964.28    4970 4972.69 4972.78 4973.78 4984.58 4986.28 4988.88 4995.48 4995.68
 4995.78 4997.48 5006.38 5014.88 5015.48 5018.18 5027.58 5035.47 5035.58 5037.48
 5043.78 5046.58 5054.18 5065.08 5118.28 5174.68 5224.68 5284.48  5291.2  5421.2
  5451.2  5481.2  5559.7
    32.7    32.1      31    30.5      31    30.9   30.44   30.65   30.85   30.69
   26.78   24.26   24.11   24.11   24.11   24.12   24.12   24.12   24.13   24.13
   24.13   24.13   24.13   24.14   24.14   24.14   24.15   24.16   24.16   24.16
   24.17   24.38   26.53   30.77   31.95   31.26   31.61   31.39    31.6    31.3
    31.6    32.6    32.6
    32.7    32.1      31    30.5      31    30.9   30.44   30.65   30.85   30.69
   26.78   24.25   23.06   23.11   23.11   23.12   23.12   23.12   23.13   23.13
   23.13   23.13   23.13   23.14   23.14   23.14   23.15   23.16   23.06   23.46
    24.1   24.38   26.53   30.77   31.95   31.26   31.61   31.39    31.6    31.3
    31.6    32.6    32.6
  4374.7  4484.7  4544.7  4674.7  4713.8 4757.48 4809.58 4863.48 4919.08 4952.28
 4964.28    4970 4972.69 4972.78 4973.78 4984.58 4986.28 4988.88 4995.48 4995.68
 4995.78 4997.48 5006.38 5014.88 5015.48 5018.18 5027.58 5035.47 5035.58 5037.48
 5043.78 5046.58 5054.18 5065.08 5118.28 5174.68 5224.68 5284.48  5291.2  5421.2
  5451.2  5481.2  5559.7
    32.7    32.1      31    30.5      31    30.9   30.44   30.65   30.85   30.69
   26.78   24.26   24.11   24.11   24.11   24.12   24.12   24.12   24.13   24.13
   24.13   24.13   24.13   24.14   24.14   24.14   24.15   24.16   24.16   24.16
   24.17   24.38   26.53   30.77   31.95   31.26   31.61   31.39    31.6    31.3
    31.6    32.6    32.6
    32.7    32.1      31    30.5      31    30.9   30.44   30.65   30.85   30.69
   26.78   24.25   23.06   23.11   23.11   23.12   23.12   23.12   23.13   23.13
   23.13   23.13   23.13   23.14   23.14   23.14   23.15   23.16   23.06   23.46
    24.1   24.38   26.53   30.77   31.95   31.26   31.61   31.39    31.6    31.3
    31.6    32.6    32.6
Pier Skew, UpSta & Num, DnSta & Num=  ,4995.7, 2 ,4995.7, 2 , 0 , 0 , 0 ,,
       1       1
   14.49   24.13
       1       1
   14.49   24.13
Pier Skew, UpSta & Num, DnSta & Num=  ,5014.9, 2 ,5014.9, 2 , 0 , 0 , 0 ,,
       1       1
   16.83   24.14
       1       1
   16.83   24.14
BR Coef= 1 , 1 , 0 ,1.25, 0 ,,,0.8,0,2,0,
WSPro=,,,, 1 ,,,, 0 ,,,, 0 ,,,,-1 ,-1 ,-1 , 0 , 0 , 0 , 0 , 0
BR U #Sta/Elev= 43
  4374.7    32.7  4484.7    32.1  4544.7      31  4674.7    30.5  4713.8      31
 4757.48    30.9 4809.58   30.44 4863.48   30.65 4919.08   30.85 4952.28   30.69
 4964.28   26.78    4970   24.25 4972.69   23.06 4972.78   23.02 4973.78   22.58
 4984.58    17.8 4986.28   17.99 4988.88    16.1 4995.48   15.46 4995.68   16.12
 4995.78   15.44 4997.48   16.61 5006.38   17.19 5014.88   17.98 5015.48    17.8
 5018.18   19.42 5027.58   21.39 5035.47   23.04 5035.58   23.06 5037.48   23.46
 5043.78    24.1 5046.58   24.38 5054.18   26.53 5065.08   30.77 5118.28   31.95
 5174.68   31.26 5224.68   31.61 5284.48   31.39  5291.2    31.6  5421.2    31.3
  5451.2    31.6  5481.2    32.6  5559.7    32.6
BR U #Mann= 5
  4374.7      .2  4374.7      .1 4952.28    .045 5065.08      .1  5559.7      .2
BR U Banks=4952.28,5065.08
BR D #Sta/Elev= 43
  4374.7    32.7  4484.7    32.1  4544.7      31  4674.7    30.5  4713.8      31
 4757.48    30.9 4809.58   30.44 4863.48   30.65 4919.08   30.85 4952.28   30.69
 4964.28   26.78    4970   24.25 4972.69   23.06 4972.78   23.02 4973.78   22.58
 4984.58    17.8 4986.28   17.99 4988.88    16.1 4995.48   15.46 4995.68   16.12
 4995.78   15.44 4997.48   16.61 5006.38   17.19 5014.88   17.98 5015.48    17.8
 5018.18   19.42 5027.58   21.39 5035.47   23.04 5035.58   23.06 5037.48   23.46
 5043.78    24.1 5046.58   24.38 5054.18   26.53 5065.08   30.77 5118.28   31.95
 5174.68   31.26 5224.68   31.61 5284.48   31.39  5291.2    31.6  5421.2    31.3
  5451.2    31.6  5481.2    32.6  5559.7    32.6
BR D #Mann= 5
  4374.7      .2  4374.7      .1 4952.28    .045 5065.08      .1  5559.7      .2
BR D Banks=4952.28,5065.08
BC Design=,, 0 ,, 0 ,,,,,,
BC HTab HWMax=32.73
BC Use User HTab Curves=0
BC User HTab FreeFlow(D)= 0

Type RM Length L Ch R = 1 ,8128.1  ,11.5,11.5,11.5
BEGIN DESCRIPTION:
Downstream Section of Bridge/Culvert/Weir
END DESCRIPTION:
XS GIS Cut Line= 5
       3155565.5     13810183.62      3155880.23     13810151.67
       3156164.6     13810186.82      3156284.42     13810194.81
      3156747.22     13810193.13
#Sta/Elev= 30
  4374.7    32.7  4484.7    32.1  4544.7      31  4674.7    30.5  4713.8      31
 4809.58   30.44 4919.08   30.85 4952.28   30.69 4964.28   26.78 4984.58    17.8
 4986.28   17.99 4988.88    16.1 4995.48   15.46 4995.68   16.12 4995.78   15.44
 4997.48   16.61 5014.88   17.98 5015.48    17.8 5018.18   19.42 5037.48   23.46
 5046.58   24.38 5054.18   26.53 5065.08   30.77 5118.28   31.95 5174.68   31.26
 5224.68   31.61  5421.2    31.3  5451.2    31.6  5481.2    32.6  5559.7    32.6
#Mann= 5 , 1 , 0
  4374.7      .2       0  4374.7      .1       0 4952.28    .045       0
 5065.08      .1       0  5559.7      .2       0
#XS Ineff= 2 , 0
       0  4969.9    24.2  5043.6       0    24.1
Permanent Ineff=
       F       F
Bank Sta=4952.28,5065.08
XS Rating Curve= 0 ,0
Exp/Cntr=0.5,0.3

Type RM Length L Ch R = 1 ,8116.6  ,111.6,111.6,111.6
BEGIN DESCRIPTION:
Upstream Section of Bridge/Culvert/Weir
END DESCRIPTION:
XS GIS Cut Line= 4
      3155582.83     13810226.72      3156118.78     13810207.71
      3156311.93     13810203.81      3156767.45     13810201.43
#Sta/Elev= 30
  4374.7    32.7  4484.7    32.1  4544.7      31  4626.9   30.68  4952.3   30.69
  4964.3   26.78  4984.6    17.8  4986.3   17.99  4988.9    16.1  4995.5   15.46
  4995.7   16.12  4995.8   15.44  4997.5   16.61  5006.4   17.19  5014.6   20.41
  5014.8   17.98  5015.5    17.8  5018.2   19.42  5027.4   23.39  5037.5   23.46
  5046.6   24.38  5054.2   26.53  5065.1   30.77  5118.3   31.95  5174.7   31.26
  5300.5   31.58  5421.2    31.3  5451.2    31.6  5481.2    32.6  5559.7    32.6
#Mann= 5 , 1 , 0
  4374.7      .2       0  4626.9      .1       0  4952.3    .045       0
  5065.1      .1       0  5300.5      .2       0
#XS Ineff= 2 , 0
       0  4959.8    30.5  5059.8       0    31.2
Permanent Ineff=
       F       F
Bank Sta=4952.3,5065.1
XS Rating Curve= 0 ,0
Exp/Cntr=0.5,0.3

Type RM Length L Ch R = 3 ,8060.8  ,,,
BEGIN DESCRIPTION:
WINKLER HIGHWAY, SKEW ANGLE OF 35 DEGREES
Structure ID: C61-3
END DESCRIPTION:
Bridge Culvert--1,0,-1,-1, 0
Deck Dist Width WeirC Skew NumUp NumDn MinLoCord MaxHiCord MaxSubmerge Is_Ogee
10,91.6,2.6,0, 27, 28, , , 0.95, 0, 1,1,,
  4374.7  4484.7  4544.7  4674.7  4713.8  4757.5  4809.6  4919.1  4952.3  4964.3
 4969.16 4969.25  5024.4  5049.5 5049.61  5054.2  5065.1 5078.61  5118.3  5174.7
  5224.7  5284.5  5291.2  5421.2  5451.2  5481.2  5559.7
    32.7    32.1      31   30.51   31.01   30.91   30.45   30.86    30.9   30.97
   31.01   31.01   31.47   31.47   31.47   31.47   31.47   31.45   31.96   31.27
   31.62    31.4   31.61    31.3    31.6    32.6    32.6
    32.7    32.1      31    30.5      31    30.9   30.44   30.85   30.69   26.78
   24.63   28.53   28.99   28.99   25.23   26.53   30.77   31.07   31.95   31.26
   31.61   31.39    31.6    31.3    31.6    32.6    32.6
  4374.7  4484.7  4544.7  4674.7  4713.8  4757.5  4809.6  4919.1  4952.3  4962.5
  4964.3 4969.16 4969.25  5024.4  5049.5 5049.61  5054.2  5065.1  5071.5  5118.3
  5174.7  5224.7  5284.5  5291.2  5421.2  5451.2  5481.2  5559.7
   33.26   32.66   31.56   31.06   31.56   31.46      31   31.41   31.25   30.95
   30.97   31.01   31.01   31.47   31.47   31.47   31.47   31.47   31.47   32.51
   31.82   32.17   31.95   32.16   31.86   32.16   33.16   33.16
   33.26   32.66   31.56   31.06   31.56   31.46      31   31.41   31.25   27.93
   27.34   25.19   29.09   29.55   29.55   25.79   27.09   31.33   31.47   32.51
   31.82   32.17   31.95   32.16   31.86   32.16   33.16   33.16
Pier Skew, UpSta & Num, DnSta & Num=  ,4996.3, 2 ,4996.3, 2 , 0 , 0 , 0 ,,
     1.4     1.4
   14.82   29.76
     1.4     1.4
   15.38   30.32
Pier Skew, UpSta & Num, DnSta & Num=  ,5030.8, 2 ,5030.8, 2 , 0 , 0 , 0 ,,
     1.4     1.4
   22.41   29.99
     1.4     1.4
   22.97   30.55
Abutment Skew #Up #Dn= , 2 , 2
 4969.05 4972.37
   28.53   23.21
 4969.05 4972.37
   29.09   23.77
Abutment Skew #Up #Dn= , 2 , 2
 5014.92  5049.7
   17.95   28.99
 5014.92  5049.7
   18.51   29.55
BR Coef= 1 , 1 , 0 ,1.25, 0 ,,,0.8,0,2,0,
WSPro=,,,, 1 ,,,, 0 ,,,, 0 ,,,,-1 ,-1 ,-1 , 0 , 0 , 0 , 0 , 0
BR U #Sta/Elev= 63
  4374.7    32.7  4484.7    32.1  4544.7      31  4626.9   30.68  4674.7    30.5
  4713.8      31  4720.6   30.98  4757.5    30.9  4764.3   30.84  4809.6   30.44
  4819.2   30.48  4863.5   30.65  4878.9   30.71  4919.1   30.85  4926.9   30.81
 4948.19   30.71  4948.3   30.71 4948.41   30.71  4952.3   30.69  4962.5   27.37
  4964.3   26.78 4969.16   24.63 4969.25   24.59 4972.37   23.21  4984.6    17.8
  4986.3   17.99  4988.9    16.1  4995.5   15.46  4995.7   16.12  4995.8   15.44
  4997.5   16.61  5006.4   17.19  5014.6   20.41  5014.8   17.98 5014.92   17.95
  5015.5    17.8  5018.2   19.42  5024.4    22.1  5027.4   23.39  5037.5   23.46
  5046.6   24.38  5049.5    25.2 5049.61   25.23  5054.2   26.53  5065.1   30.77
  5071.5   30.91 5078.39   31.06  5078.5   31.07 5078.61   31.07  5115.3   31.88
  5118.3   31.95  5162.5   31.41  5174.7   31.26  5222.6    31.6  5224.7   31.61
  5284.5   31.39  5287.9    31.5  5291.2    31.6  5300.5   31.58  5421.2    31.3
  5451.2    31.6  5481.2    32.6  5559.7    32.6
BR U #Mann= 5
  4374.7      .2  4626.9      .1  4952.3    .045  5065.1      .1  5300.5      .2
BR U Banks=4952.3,5065.1
BR D #Sta/Elev= 63
  4374.7   33.26  4484.7   32.66  4544.7   31.56  4626.9   31.24  4674.7   31.06
  4713.8   31.56  4720.6   31.54  4757.5   31.46  4764.3    31.4  4809.6      31
  4819.2   31.04  4863.5   31.21  4878.9   31.27  4919.1   31.41  4926.9   31.37
 4948.19   31.27  4948.3   31.27 4948.41   31.27  4952.3   31.25  4962.5   27.93
  4964.3   27.34 4969.16   25.19 4969.25   25.15 4972.37   23.77  4984.6   18.36
  4986.3   18.55  4988.9   16.66  4995.5   16.02  4995.7   16.68  4995.8      16
  4997.5   17.17  5006.4   17.75  5014.6   20.97  5014.8   18.54 5014.92   18.51
  5015.5   18.36  5018.2   19.98  5024.4   22.66  5027.4   23.95  5037.5   24.02
  5046.6   24.94  5049.5   25.76 5049.61   25.79  5054.2   27.09  5065.1   31.33
  5071.5   31.47 5078.39   31.62  5078.5   31.63 5078.61   31.63  5115.3   32.44
  5118.3   32.51  5162.5   31.97  5174.7   31.82  5222.6   32.16  5224.7   32.17
  5284.5   31.95  5287.9   32.06  5291.2   32.16  5300.5   32.14  5421.2   31.86
  5451.2   32.16  5481.2   33.16  5559.7   33.16
BR D #Mann= 5
  4374.7      .2  4626.9      .1  4952.3    .045  5065.1      .1  5300.5      .2
BR D Banks=4952.3,5065.1
BC Design=,, 0 ,, 0 ,,,,,,
BC HTab HWMax=32.7
BC Use User HTab Curves=0
BC User HTab FreeFlow(D)= 0

Type RM Length L Ch R = 1 ,8005.0  ,289,287,285
BEGIN DESCRIPTION:
Downstream Section of Bridge/Culvert/Weir
END DESCRIPTION:
XS GIS Cut Line= 4
      3155650.46     13810315.49      3156186.42     13810296.49
      3156379.57     13810292.59      3156835.08      13810290.2
#Sta/Elev= 30
  4374.7   33.25  4484.7   32.65  4544.7   31.55  4626.9   31.23  4952.3   31.24
  4964.3   27.33  4984.6   18.35  4986.3   18.54  4988.9   16.65  4995.5   16.01
  4995.7   16.67  4995.8   15.99  4997.5   17.16  5006.4   17.74  5014.6   20.96
  5014.8   18.53  5015.5   18.35  5018.2   19.97  5027.4   23.94  5037.5   24.01
  5046.6   24.93  5054.2   27.08  5065.1   31.32  5118.3    32.5  5174.7   31.81
  5300.5   32.13  5421.2   31.85  5451.2   32.15  5481.2   33.15  5559.7   33.15
#Mann= 5 , 1 , 0
  4374.7      .2       0  4626.9      .1       0  4952.3    .045       0
  5065.1      .1       0  5300.5      .2       0
#XS Ineff= 2 , 0
       0    4959    30.3  5059.8       0      31
Permanent Ineff=
       F       F
Bank Sta=4952.3,5065.1
XS Rating Curve= 0 ,0
Exp/Cntr=0.5,0.3

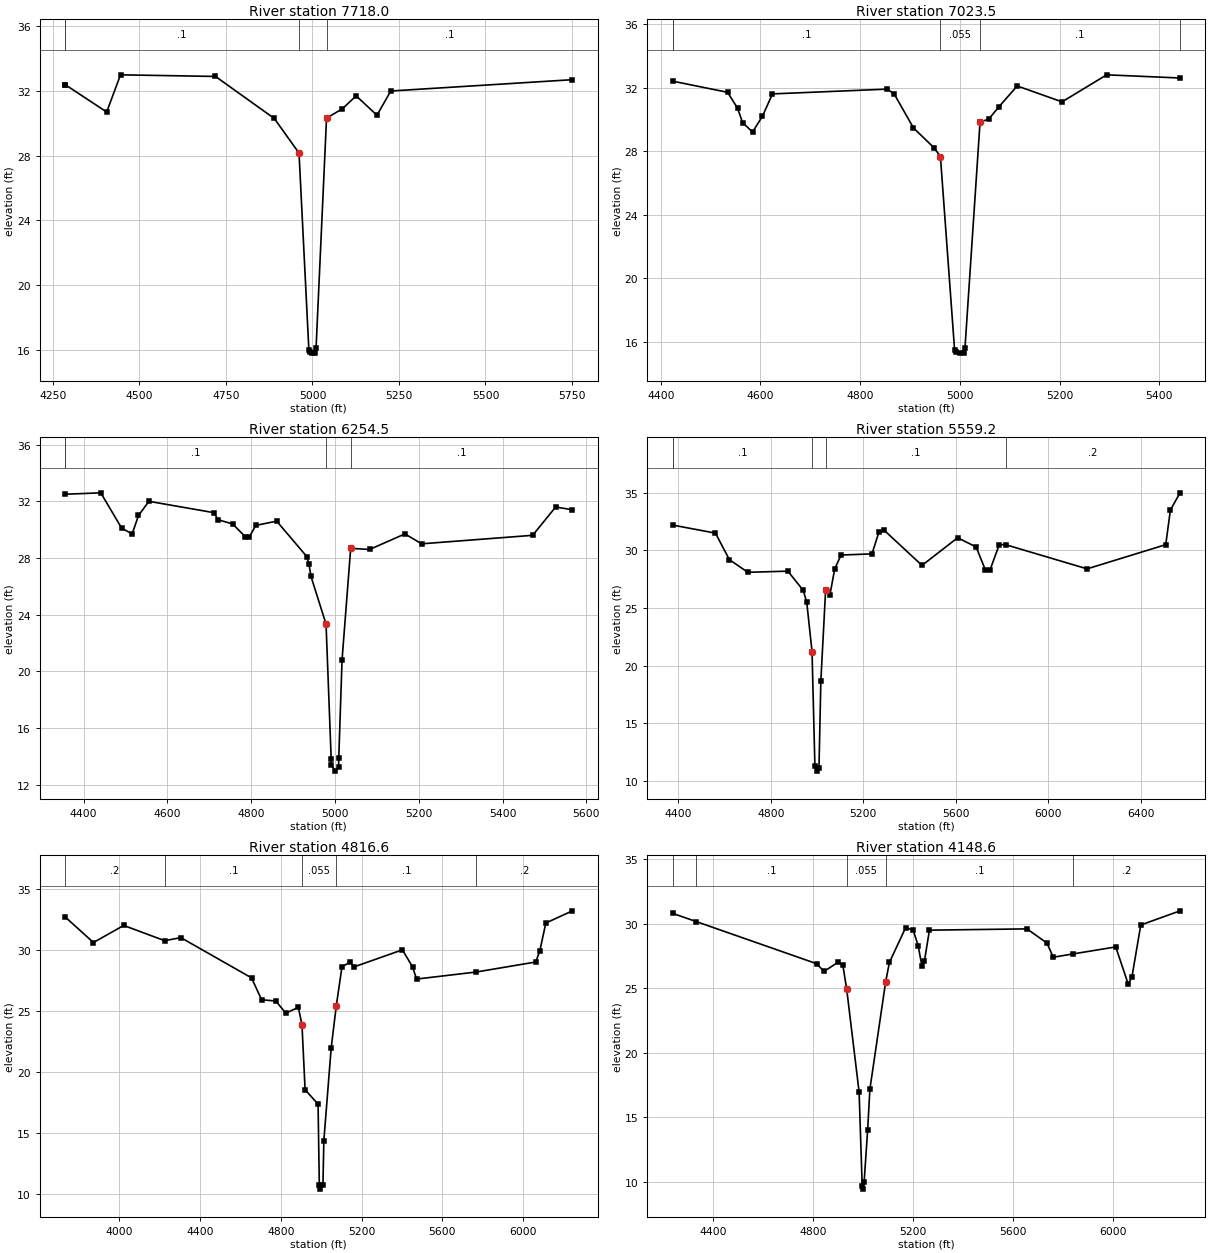
Type RM Length L Ch R = 1 ,7718.0  ,725.9,694.5,580
BEGIN DESCRIPTION:
Cross Section 7718.0-Interpolated
END DESCRIPTION:
XS GIS Cut Line= 5
       3155560.6     13810747.77      3155958.79      13810573.8
      3156186.88     13810539.01      3156322.19     13810527.41
      3156987.13     13810519.68
#Sta/Elev= 18
  4285.2    32.4  4285.6   32.39  4405.2    30.7  4445.2      33  4719.7    32.9
  4889.7    30.3  4961.1   28.16  4989.6   15.96  4992.9   15.83  4999.9   15.79
  5007.7   15.82  5010.4   16.13  5040.6   30.32  5086.3    30.9  5126.3    31.7
  5186.3    30.5  5226.3      32  5751.3    32.7
#Mann= 4 , 1 , 0
  4285.2      .2       0  4285.6      .1       0  4961.1    .055       0
  5040.6      .1       0
#XS Ineff= 2 , 0
       0  4426.1    31.9               0
Permanent Ineff=
       F       F
Bank Sta=4961.1,5040.6
XS Rating Curve= 0 ,0
Exp/Cntr=0.3,0.1

Type RM Length L Ch R = 1 ,7023.5  ,725.5,769,732.7
BEGIN DESCRIPTION:
Cross Section 7023.5
END DESCRIPTION:
XS GIS Cut Line= 5
      3156168.65      13811377.2      3156527.24     13811115.16
      3156683.54     13810995.63      3156807.67     13810802.54
      3156899.62     13810687.61
#Sta/Elev= 24
  4424.2    32.4  4534.2    31.7  4554.2    30.7  4564.2    29.8  4584.2    29.2
  4604.2    30.2  4624.2    31.6  4854.2    31.9  4868.3    31.6    4907   29.46
  4948.3   28.21  4961.1   27.66  4989.6   15.46  4992.9   15.33  4999.9   15.29
  5007.7   15.32  5010.4   15.63  5040.6   29.82  5058.1   30.02  5078.5   30.79
  5115.1    32.1  5205.1    31.1  5294.6    32.8  5441.8    32.6
#Mann= 5 , 1 , 0
  4424.2      .2       0  4424.2      .1       0  4961.1    .055       0
  5040.6      .1       0  5441.8      .2       0
#XS Ineff= 2 , 0
       0  4624.2    31.6               0
Permanent Ineff=
       F       F
Bank Sta=4961.1,5040.6
XS Rating Curve= 0 ,0
Exp/Cntr=0.3,0.1

Type RM Length L Ch R = 1 ,6254.5  ,665,695.3,713.3
BEGIN DESCRIPTION:
Cross Section 6254.5-Interpolated
END DESCRIPTION:
XS GIS Cut Line= 4
      3156461.73     13812011.67      3156906.68     13811693.85
      3157097.38     13811566.73       3157386.9      13811242.1
#Sta/Elev= 30
  4355.9    32.5  4440.9    32.6  4490.9    30.1  4515.9    29.7  4530.9      31
  4555.9      32  4710.9    31.2  4720.9    30.7  4755.9    30.4  4785.9    29.5
  4795.9    29.5  4810.9    30.3  4860.9    30.6  4932.7    28.1  4937.7    27.6
  4942.7    26.7  4978.7   23.33    4991   13.79  4991.1   13.41  5000.7   12.95
  5008.7   13.21  5009.1   13.91  5016.9    20.8  5037.5   28.68  5082.7    28.6
  5166.9    29.7  5206.9      29  5471.9    29.6  5526.9    31.6  5566.9    31.4
#Mann= 4 , 1 , 0
  4355.9      .2       0  4355.9      .1       0  4978.7    .055       0
  5037.5      .1       0
Bank Sta=4978.7,5037.5
XS Rating Curve= 0 ,0
Exp/Cntr=0.3,0.1

Type RM Length L Ch R = 1 ,5559.2  ,742.7,742.6,718.8
BEGIN DESCRIPTION:
Cross Section 5559.2
END DESCRIPTION:
XS GIS Cut Line= 6
      3156734.11     13812328.84        3156918.     13812310.45
      3157457.97     13812138.06      3157566.19     13812011.81
      3157809.67     13811813.42      3158770.71     13811772.57
#Sta/Elev= 30
  4376.4    32.2  4561.2    31.5  4621.2    29.2  4701.2    28.1  4874.3    28.2
  4940.5   26.54  4955.9   25.49  4978.7   21.22  4991.1    11.3  5000.7   10.84
  5008.7    11.1  5016.9   18.69  5037.5   26.57  5055.7   26.09  5076.7    28.4
  5104.3    29.6    5238    29.7    5268    31.6    5288    31.8  5454.3    28.7
  5608.4    31.1  5688.4    30.3  5728.4    28.3  5748.4    28.3  5788.4    30.5
  5815.5    30.5  6168.4    28.4  6508.4    30.5  6528.4    33.5  6570.3      35
#Mann= 5 , 1 , 0
  4376.4      .2       0  4376.4      .1       0  4978.7    .055       0
  5037.5      .1       0  5815.5      .2       0
Bank Sta=4978.7,5037.5
XS Rating Curve= 0 ,0
Exp/Cntr=0.3,0.1

Type RM Length L Ch R = 1 ,4816.6  ,667.9,668,677.1
BEGIN DESCRIPTION:
Cross Section 4816.6
END DESCRIPTION:
XS GIS Cut Line= 5
      3156231.56     13813048.85      3156804.19     13813039.83
      3157359.32     13812920.08      3157642.12     13812821.96
      3158710.94     13812742.59
#Sta/Elev= 30
  3732.6    32.7  3872.6    30.6  4022.6      32  4225.3   30.75  4305.3      31
  4655.3    27.7  4705.3    25.9  4775.3    25.8  4825.3    24.8  4887.1   25.28
  4905.1   23.86  4920.6   18.52  4984.8   17.33    4991   10.72  4993.5   10.36
    5009   10.71  5013.4   14.34  5049.9   21.97  5075.2   25.43  5103.2    28.6
  5143.2      29  5163.2    28.6  5402.5      30  5452.5    28.6  5472.5    27.6
  5768.6   28.18  6062.5      29  6082.5    29.9  6112.5    32.2  6244.3    33.2
#Mann= 5 , 1 , 0
  3732.6      .2       0  4225.3      .1       0  4905.1    .055       0
  5075.2      .1       0  5768.6      .2       0
Bank Sta=4905.1,5075.2
XS Rating Curve= 0 ,0
Exp/Cntr=0.3,0.1

Type RM Length L Ch R = 1 ,4148.6  ,766.4,753.1,732.5
BEGIN DESCRIPTION:
Cross Section 4148.6-Interpolated
END DESCRIPTION:
XS GIS Cut Line= 4
      3156797.72     13813628.02      3157469.68     13813491.81
      3157633.13     13813464.57       3158722.8     13813019.62
#Sta/Elev= 30
  4238.6    30.8  4333.4   30.16  4813.6    26.9  4843.6    26.3  4898.6      27
  4918.6    26.8  4934.2    24.9  4983.7   16.94    4996    9.69  4999.8    9.41
  5003.9      10  5017.9   14.02  5026.8   17.16  5089.9    25.5  5104.9      27
  5169.9    29.7  5199.9    29.5  5219.9    28.3  5234.9    26.7  5244.9    27.1
  5264.9    29.5  5654.9    29.6  5734.9    28.5  5759.9    27.4    5840   27.66
  6009.9    28.2  6059.9    25.3  6074.9    25.9  6109.9    29.9    6267      31
#Mann= 5 , 1 , 0
  4238.6      .2       0  4333.4      .1       0  4934.2    .055       0
  5089.9      .1       0    5840      .2       0
Bank Sta=4934.2,5089.9
XS Rating Curve= 0 ,0
Exp/Cntr=0.3,0.1