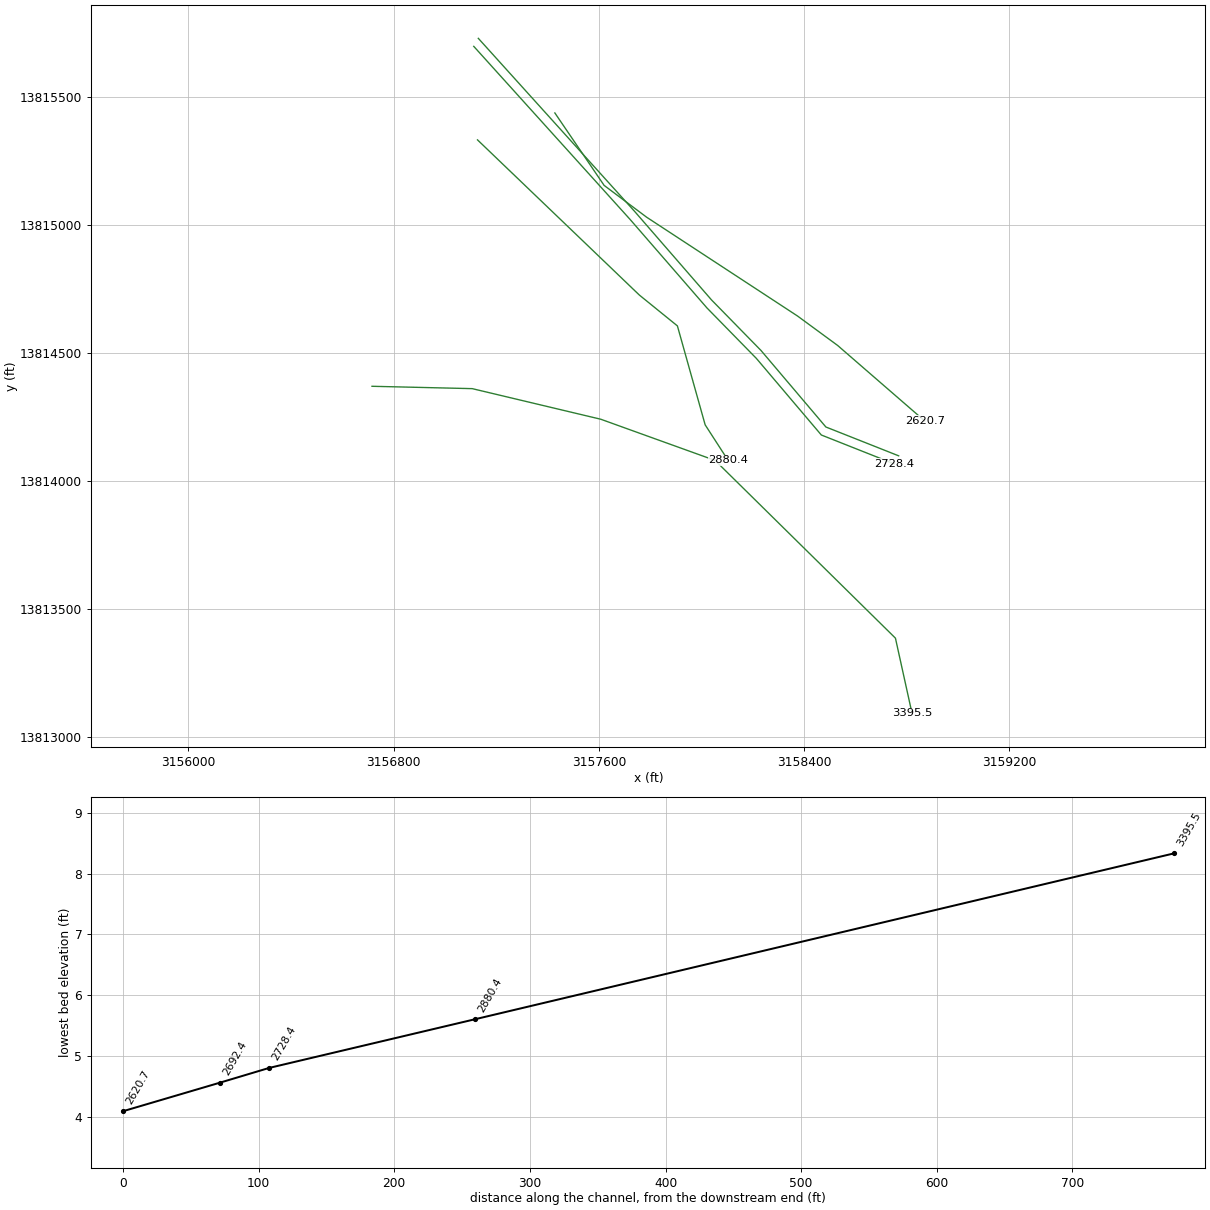
HEC-RAS study C106-01-00.PRJ: C106-01-00

--- C106-01-00.g01 (geometry) --- (continued)

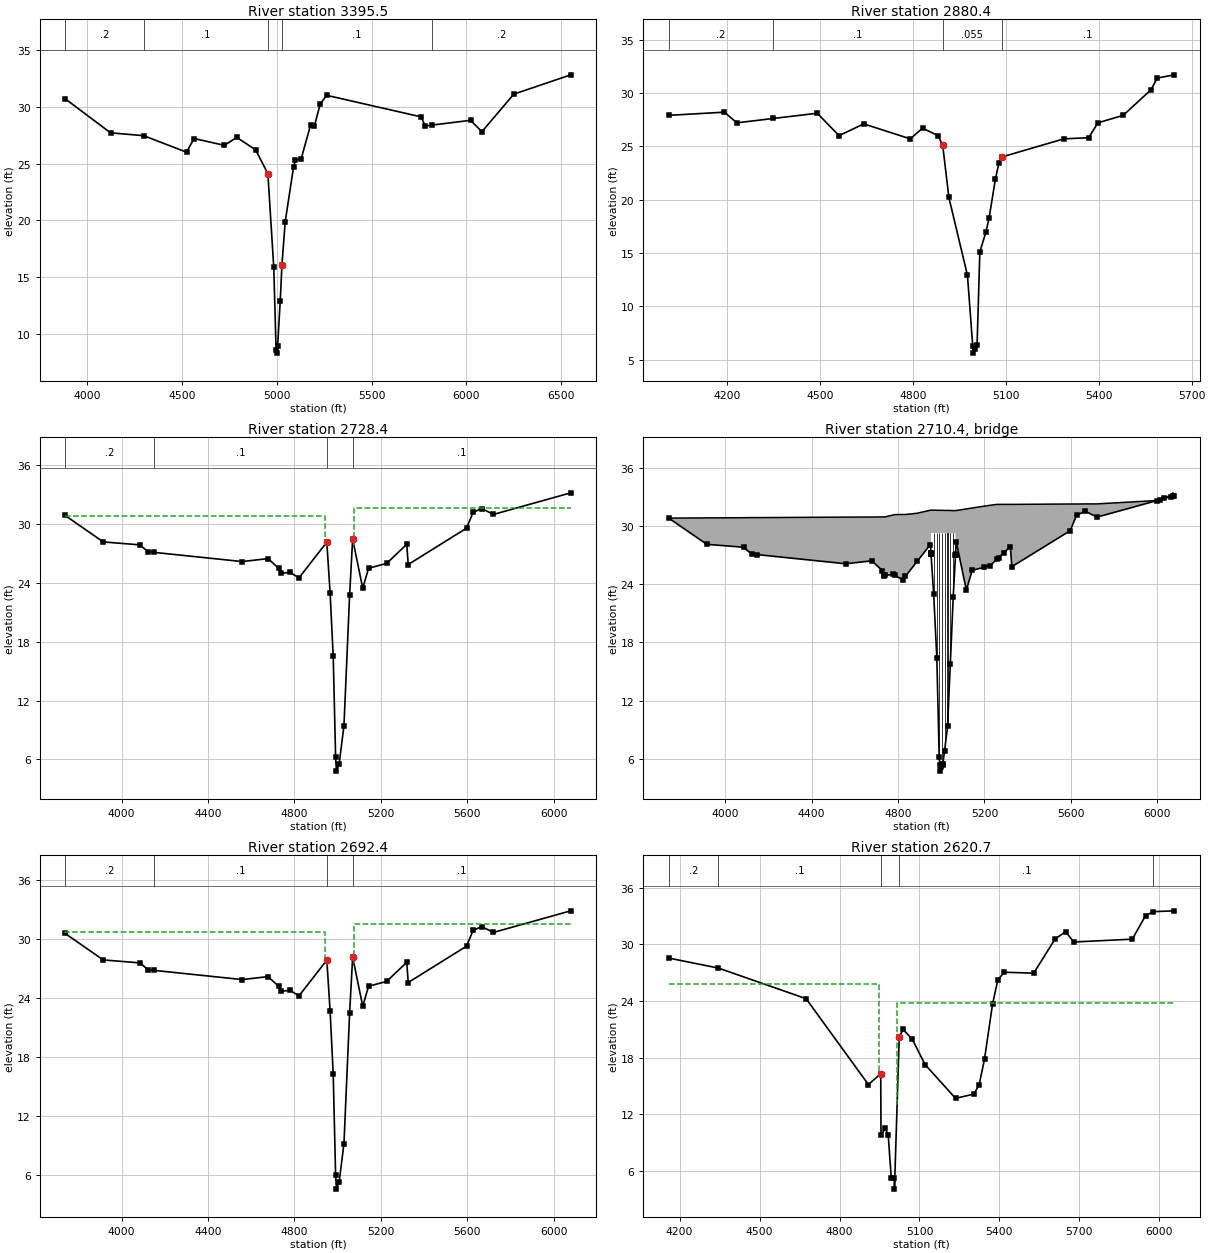
Type RM Length L Ch R = 1 ,3395.5  ,514.5,515.1,414.8
BEGIN DESCRIPTION:
Cross Section 3395.5
END DESCRIPTION:
XS GIS Cut Line= 6
      3156715.72     13814370.03      3157106.49     13814360.83
       3157607.6      13814241.3      3158053.49     13814080.29
      3158756.57     13813385.92      3158821.28     13813091.99
#Sta/Elev= 30
  3882.2    30.7  4122.2    27.7  4296.8   27.45  4523.1      26  4563.1    27.2
  4723.1    26.6  4788.2    27.3  4888.2    26.2  4952.6    24.1  4983.7   15.86
    4996    8.61  4999.8    8.33  5003.9    8.92  5017.9   12.94  5026.8   16.08
  5044.1   19.89  5088.2    24.7  5098.2    25.3  5128.2    25.4  5178.2    28.4
  5198.2    28.3  5228.2    30.2  5262.3      31  5762.3    29.1  5782.3    28.3
  5818.9   28.38  6022.3    28.8  6082.3    27.8  6250.5    31.1  6551.5    32.8
#Mann= 5 , 1 , 0
  3882.2      .2       0  4296.8      .1       0  4952.6    .055       0
  5026.8      .1       0  5818.9      .2       0
Bank Sta=4952.6,5026.8
XS Rating Curve= 0 ,0
Exp/Cntr=0.3,0.1

Type RM Length L Ch R = 1 ,2880.4  ,124.8,152,123.2
BEGIN DESCRIPTION:
Cross Section 2880.4-Interpolated
END DESCRIPTION:
XS GIS Cut Line= 5
      3157127.07     13815332.77        3157758.     13814726.59
      3157906.45     13814605.98      3158014.69     13814219.38
      3158104.38     13814080.21
#Sta/Elev= 30
  4011.1    27.9  4191.1    28.2  4231.1    27.2    4349   27.61  4491.1    28.1
  4561.1      26  4641.1    27.1  4791.1    25.7  4831.1    26.7  4881.1      26
    4896    25.1    4916    20.2    4976    12.9  4993.1    6.25  4994.2    5.61
  4999.2    5.99    5007    6.35    5016    15.1    5036      17    5046    18.3
    5066    21.9  5077.3    23.4  5087.3      24  5287.3    25.7  5367.3    25.8
  5397.3    27.2  5478.8    27.9  5568.8    30.3  5588.8    31.4  5644.3    31.7
#Mann= 4 , 1 , 0
  4011.1      .2       0    4349      .1       0    4896    .055       0
  5087.3      .1       0
Bank Sta=4896,5087.3
XS Rating Curve= 0 ,0
Exp/Cntr=0.5,0.3

Type RM Length L Ch R = 1 ,2728.4  ,36,36,36
BEGIN DESCRIPTION:
Upstream Section of Bridge/Culvert/Weir
END DESCRIPTION:
XS GIS Cut Line= 6
      3157112.46     13815698.24      3157722.84     13815020.98
      3158021.67     13814676.19      3158214.75      13814478.5
       3158467.6     13814179.68      3158751.38       13814067.
#Sta/Elev= 30
  3738.2   30.85  3914.8   28.15  4084.8   27.85  4122.1   27.15  4148.6   27.09
  4557.8   26.15  4677.8   26.45  4727.8   25.45  4735.7   24.94  4778.4   25.06
  4821.1   24.49  4949.8   28.13    4965   22.99  4979.5   16.49  4990.5    6.29
  4994.2    4.81    5007    5.55  5029.2    9.44  5055.3    22.7  5069.4   28.44
  5116.1   23.44  5143.2   25.47  5226.8   25.96  5319.9   27.91  5326.7   25.85
  5596.7   29.55  5626.7   31.15  5666.7   31.55  5721.1   30.95  6079.3   33.15
#Mann= 4 , 1 , 0
  3738.2      .2       0  4148.6      .1       0  4949.8    .055       0
  5069.4      .1       0
#XS Ineff= 2 , 0
       0  4942.6    30.8  5076.1       0    31.6
Permanent Ineff=
       F       F
Bank Sta=4949.8,5069.4
XS Rating Curve= 0 ,0
Exp/Cntr=0.5,0.3

Type RM Length L Ch R = 3 ,2710.4  ,,,
BEGIN DESCRIPTION:
UNION PACIFIC RAILROAD
Structure ID: C61-2
END DESCRIPTION:
Bridge Culvert--1,0,-1,-1, 0
Deck Dist Width WeirC Skew NumUp NumDn MinLoCord MaxHiCord MaxSubmerge Is_Ogee
10,16,2.6,0, 58, 58, , , 0.95, 0, 1,1,,
  3738.2  3914.8  4084.8  4122.1  4148.6  4557.8  4677.8  4727.8  4735.3  4735.7
    4738  4778.4  4786.5  4821.1  4833.8  4888.6  4949.8  4952.4 4952.51 4952.63
  4952.7    4965  4979.5  4990.5  4993.1  4994.2  4999.2  5002.5  5005.8    5007
  5015.6  5029.2  5041.8  5055.3  5065.9 5065.99  5066.1  5066.2  5069.4  5116.1
  5143.2  5196.2  5226.8  5256.8    5266  5289.2  5319.9  5326.7  5596.7  5626.7
  5666.7  5721.1  5998.2  6012.9  6032.9  6062.9  6072.9  6079.3
    30.8   30.82   30.84   30.85   30.85    30.9   30.91   30.92   30.92   30.92
   30.92   31.12   31.16   31.17   31.17    31.3   31.61   31.62   31.62   31.62
   31.62   31.61   31.61    31.6    31.6    31.6    31.6    31.6    31.6    31.6
   31.59   31.59   31.58   31.57   31.57   31.57   31.57   31.57   31.58   31.74
   31.84   32.02   32.12   32.21   32.21   32.21   32.21   32.21   32.25   32.25
   32.26   32.26   32.61    32.7   32.83    33.2    33.4    33.1
    30.8    28.1    27.8    27.1   27.04    26.1    26.4    25.4   24.92   24.89
    24.9   25.01    24.9   24.44    24.8   26.35   28.08    27.2   27.16   27.12
   29.27   29.26   29.26   29.25   29.25   29.25   29.25   29.25   29.25   29.25
   29.24   29.24   29.23   29.22   29.22   29.22   27.05   27.09   28.39   23.39
   25.42   25.73   25.91   26.55   26.74   27.22   27.86    25.8    29.5    31.1
    31.5    30.9    32.6   32.69   32.82      33   33.06    33.1
  3738.2  3914.8  4084.8  4122.1  4148.6  4557.8  4677.8  4727.8  4735.3  4735.7
    4738  4778.4  4786.5  4821.1  4833.8  4888.6  4949.8  4952.4 4952.51 4952.63
  4952.7    4965  4979.5  4990.5  4993.1  4994.2  4999.2  5002.5  5005.8    5007
  5015.6  5029.2  5041.8  5055.3  5065.9 5065.99  5066.1  5066.2  5069.4  5116.1
  5143.2  5196.2  5226.8  5256.8    5266  5289.2  5319.9  5326.7  5596.7  5626.7
  5666.7  5721.1  5998.2  6012.9  6032.9  6062.9  6072.9  6079.3
    30.8   30.82   30.84   30.85   30.85    30.9   30.91   30.92   30.92   30.92
   30.92   31.12   31.16   31.17   31.17    31.3   31.61   31.62   31.62   31.62
   31.62   31.61   31.61    31.6    31.6    31.6    31.6    31.6    31.6    31.6
   31.59   31.59   31.58   31.57   31.57   31.57   31.57   31.57   31.58   31.74
   31.84   32.02   32.12   32.21   32.21   32.21   32.21   32.21   32.25   32.25
   32.26   32.26   32.61    32.7   32.83    33.2    33.4    33.1
   30.67   27.97   27.67   26.97   26.91   25.97   26.27   25.27   24.79   24.76
   24.77   24.88   24.77   24.31   24.67   26.22   27.95   27.07   27.03   26.99
   29.14   29.13   29.13   29.12   29.12   29.12   29.12   29.12   29.12   29.12
   29.11   29.11    29.1   29.09   29.09   29.09   26.92   26.96   28.26   23.26
   25.29    25.6   25.78   26.42   26.61   27.09   27.73   25.67   29.37   30.97
   31.37   30.77   32.47   32.56   32.69   32.87   32.93   32.97
Pier Skew, UpSta & Num, DnSta & Num=  ,4965, 2 ,4965, 2 , 0 , 0 , 0 ,,
       1       1
   21.72   30.26
       1       1
   21.59   30.13
Pier Skew, UpSta & Num, DnSta & Num=  ,4979.5, 2 ,4979.5, 2 , 0 , 0 , 0 ,,
       1       1
   14.98   30.26
       1       1
   14.85   30.13
Pier Skew, UpSta & Num, DnSta & Num=  ,4990.5, 2 ,4990.5, 2 , 0 , 0 , 0 ,,
       1       1
    5.08   30.25
       1       1
    4.95   30.12
Pier Skew, UpSta & Num, DnSta & Num=  ,5002.5, 2 ,5002.5, 2 , 0 , 0 , 0 ,,
       1       1
     4.4   30.25
       1       1
    4.27   30.12
Pier Skew, UpSta & Num, DnSta & Num=  ,5015.6, 2 ,5015.6, 2 , 0 , 0 , 0 ,,
       1       1
     5.8   30.24
       1       1
    5.67   30.11
Pier Skew, UpSta & Num, DnSta & Num=  ,5029.2, 2 ,5029.2, 2 , 0 , 0 , 0 ,,
       1       1
     8.3   30.24
       1       1
    8.17   30.11
Pier Skew, UpSta & Num, DnSta & Num=  ,5041.8, 2 ,5041.8, 2 , 0 , 0 , 0 ,,
       1       1
   14.52   30.23
       1       1
   14.39    30.1
Pier Skew, UpSta & Num, DnSta & Num=  ,5055.3, 2 ,5055.3, 2 , 0 , 0 , 0 ,,
       1       1
    21.4   30.22
       1       1
   21.27   30.09
BR Coef= 1 , 1 , 0 ,1.25, 0 ,,,0.8,0,2,0,
WSPro=,,,, 1 ,,,, 0 ,,,, 0 ,,,,-1 ,-1 ,-1 , 0 , 0 , 0 , 0 , 0
BR U #Sta/Elev= 58
  3738.2    30.8  3914.8    28.1  4084.8    27.8  4122.1    27.1  4148.6   27.04
  4557.8    26.1  4677.8    26.4  4727.8    25.4  4735.3   24.92  4735.7   24.89
    4738    24.9  4778.4   25.01  4786.5    24.9  4821.1   24.44  4833.8    24.8
  4888.6   26.35  4949.8   28.08  4952.4    27.2 4952.51   27.16 4952.63   27.12
  4952.7    27.1    4965   22.94  4979.5   16.44  4990.5    6.24  4993.1     5.4
  4994.2    4.76  4999.2    5.14  5002.5    5.45  5005.8    5.44    5007     5.5
  5015.6    6.88  5029.2    9.39  5041.8   15.77  5055.3   22.65  5065.9   26.97
 5065.99      27  5066.1   27.05  5066.2   27.09  5069.4   28.39  5116.1   23.39
  5143.2   25.42  5196.2   25.73  5226.8   25.91  5256.8   26.55    5266   26.74
  5289.2   27.22  5319.9   27.86  5326.7    25.8  5596.7    29.5  5626.7    31.1
  5666.7    31.5  5721.1    30.9  5998.2    32.6  6012.9   32.69  6032.9   32.82
  6062.9      33  6072.9   33.06  6079.3    33.1
BR U #Mann= 4
  3738.2      .2  4148.6      .1  4949.8    .055  5069.4      .1
BR U Banks=4949.8,5069.4
BR D #Sta/Elev= 58
  3738.2   30.67  3914.8   27.97  4084.8   27.67  4122.1   26.97  4148.6   26.91
  4557.8   25.97  4677.8   26.27  4727.8   25.27  4735.3   24.79  4735.7   24.76
    4738   24.77  4778.4   24.88  4786.5   24.77  4821.1   24.31  4833.8   24.67
  4888.6   26.22  4949.8   27.95  4952.4   27.07 4952.51   27.03 4952.63   26.99
  4952.7   26.97    4965   22.81  4979.5   16.31  4990.5    6.11  4993.1    5.27
  4994.2    4.63  4999.2    5.01  5002.5    5.32  5005.8    5.31    5007    5.37
  5015.6    6.75  5029.2    9.26  5041.8   15.64  5055.3   22.52  5065.9   26.84
 5065.99   26.87  5066.1   26.92  5066.2   26.96  5069.4   28.26  5116.1   23.26
  5143.2   25.29  5196.2    25.6  5226.8   25.78  5256.8   26.42    5266   26.61
  5289.2   27.09  5319.9   27.73  5326.7   25.67  5596.7   29.37  5626.7   30.97
  5666.7   31.37  5721.1   30.77  5998.2   32.47  6012.9   32.56  6032.9   32.69
  6062.9   32.87  6072.9   32.93  6079.3   32.97
BR D #Mann= 4
  3738.2      .2  4148.6      .1  4949.8    .055  5069.4      .1
BR D Banks=4949.8,5069.4
BC Design=,, 0 ,, 0 ,,,,,,
BC HTab HWMax=33.15
BC Use User HTab Curves=0
BC User HTab FreeFlow(D)= 0

Type RM Length L Ch R = 1 ,2692.4  ,70,71.7,72
BEGIN DESCRIPTION:
Downstream Section of Bridge/Culvert/Weir
END DESCRIPTION:
XS GIS Cut Line= 6
      3157130.23     13815729.55       3157740.6     13815052.28
      3158039.43     13814707.49      3158232.51      13814509.8
      3158485.36     13814210.98      3158769.15     13814098.31
#Sta/Elev= 30
  3738.2   30.61  3914.8   27.91  4084.8   27.61  4122.1   26.91  4148.6   26.85
  4557.8   25.91  4677.8   26.21  4727.8   25.21  4735.7    24.7  4778.4   24.82
  4821.1   24.25  4949.8   27.89    4965   22.75  4979.5   16.25  4990.5    6.05
  4994.2    4.57    5007    5.31  5029.2     9.2  5055.3   22.46  5069.4    28.2
  5116.1    23.2  5143.2   25.23  5226.8   25.72  5319.9   27.67  5326.7   25.61
  5596.7   29.31  5626.7   30.91  5666.7   31.31  5721.1   30.71  6079.3   32.91
#Mann= 4 , 1 , 0
  3738.2      .2       0  4148.6      .1       0  4949.8    .055       0
  5069.4      .1       0
#XS Ineff= 2 , 0
       0  4942.6    30.8  5076.1       0    31.6
Permanent Ineff=
       F       F
Bank Sta=4949.8,5069.4
XS Rating Curve= 0 ,0
Exp/Cntr=0.5,0.3

Type RM Length L Ch R = 1 ,2620.7  ,172.2,172.2,172.2
BEGIN DESCRIPTION:
Upstream Section of Bridge/Culvert/Weir
END DESCRIPTION:
XS GIS Cut Line= 6
      3157428.66     13815438.06      3157620.77     13815154.94
      3157786.27     13815030.82      3158374.72     13814644.65
      3158531.03     13814529.71      3158871.18     13814234.18
#Sta/Elev= 30
    4159   28.56  4345.6    27.5  4674.5   24.26  4908.4   15.17  4954.6   16.32
  4955.6    9.79  4971.8   10.56  4982.8    9.78    4994    5.32    5006    5.31
  5006.1     4.1  5024.1   20.24  5038.6      21  5073.3   19.95  5121.1   17.28
  5235.4   13.71    5304   14.16    5324   15.16    5344   17.86    5374   23.66
    5394   26.26  5418.5   27.06  5528.5   26.96  5608.5   30.56  5648.5   31.36
  5678.5   30.26  5898.5   30.56  5948.5   33.06  5977.4   33.47  6056.5   33.56
#Mann= 5 , 1 , 0
    4159      .2       0  4345.6      .1       0  4954.6    .055       0
  5024.1      .1       0  5977.4      .2       0
#XS Ineff= 2 , 0
       0    4947   25.83    5016       0   23.75
Permanent Ineff=
       F       F
Bank Sta=4954.6,5024.1
XS Rating Curve= 0 ,0
Exp/Cntr=0.5,0.3