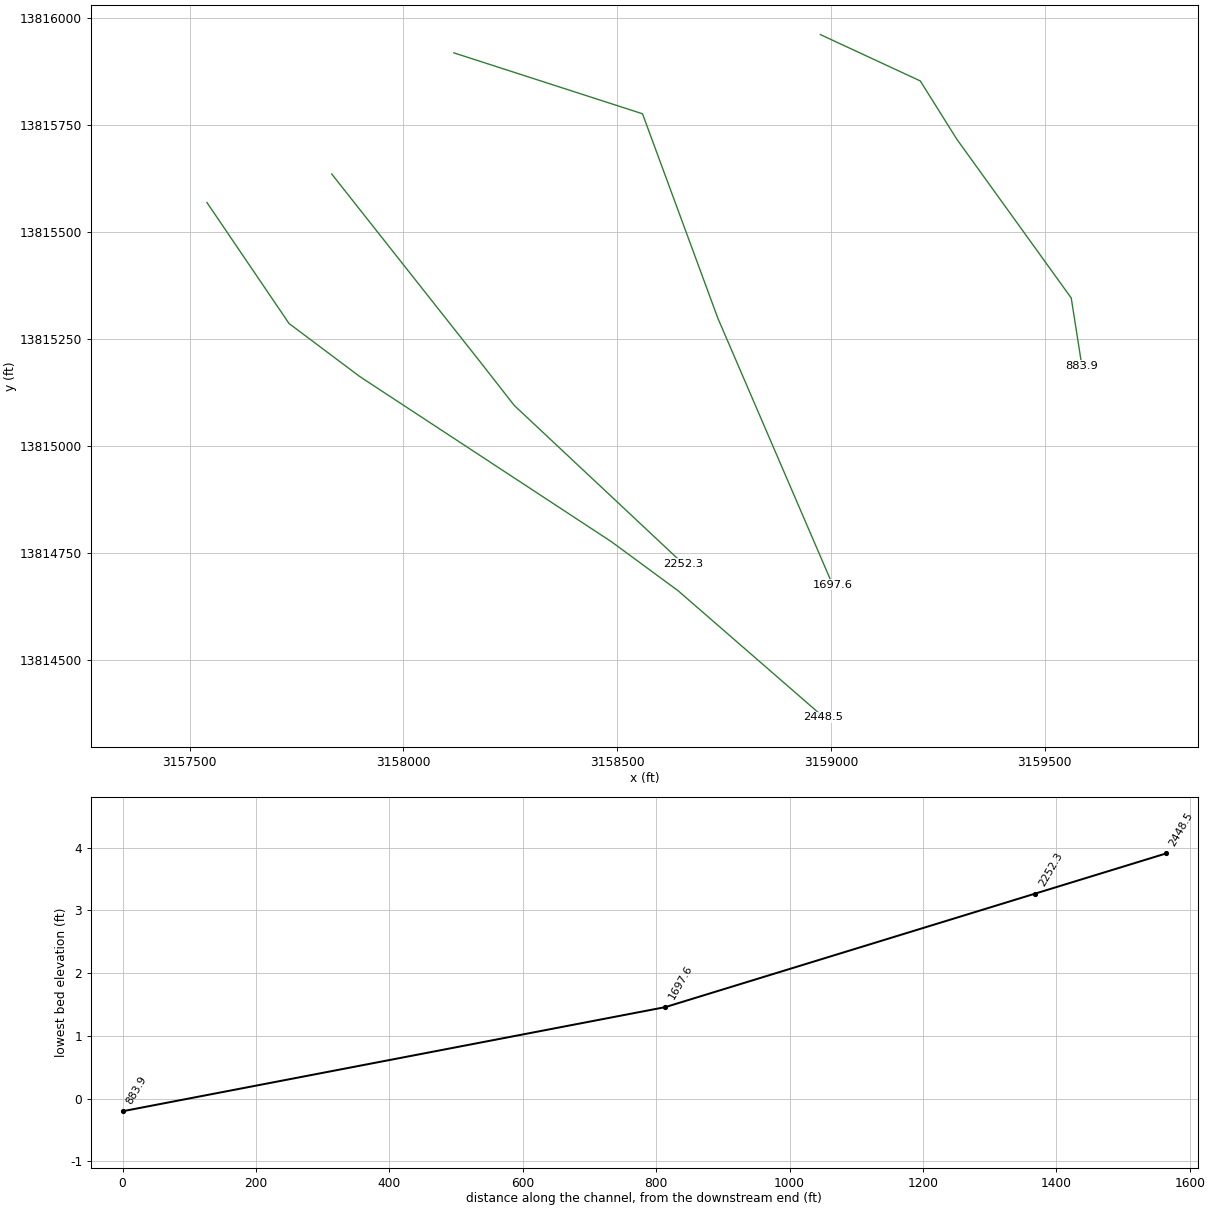
HEC-RAS study C106-01-00.PRJ: C106-01-00

--- C106-01-00.g01 (geometry) --- (continued)

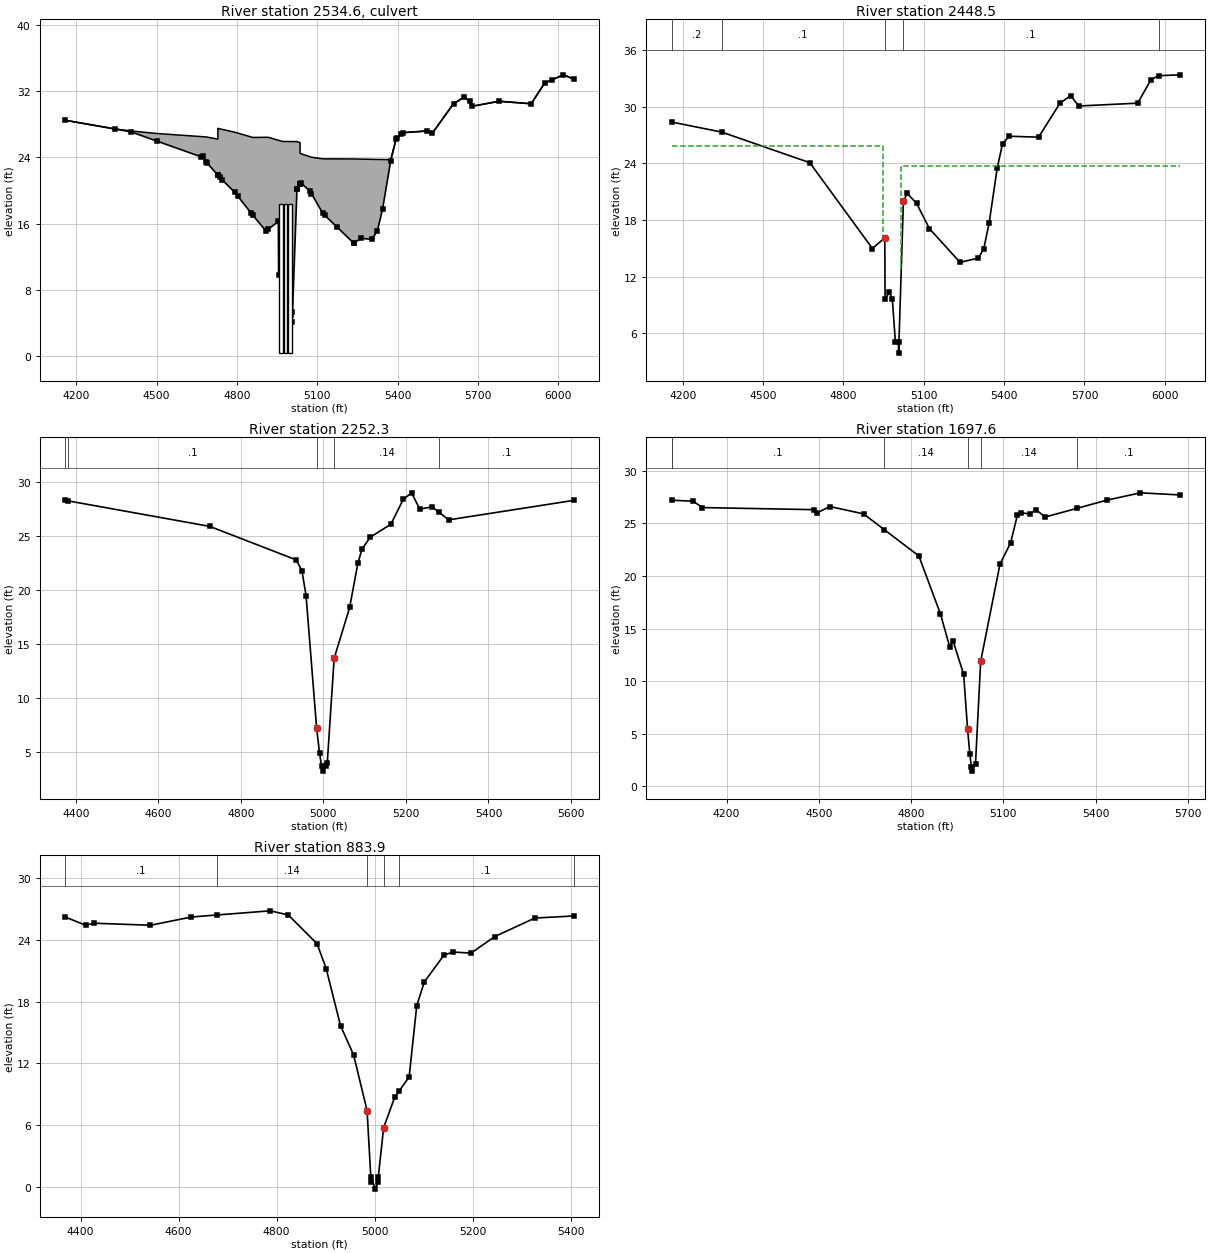
Type RM Length L Ch R = 2 ,2534.6  ,,,
BEGIN DESCRIPTION:
GALVESTON ROAD
Structure ID: C61-1
END DESCRIPTION:
Bridge Culvert--1,0,-1,-1, 0
Deck Dist Width WeirC Skew NumUp NumDn MinLoCord MaxHiCord MaxSubmerge Is_Ogee
10,152.2,3,0, 51, 51, , , 0.95, 0, 1,1,,
    4159  4345.6  4404.5  4501.2  4664.5  4674.5  4684.5 4728.79  4728.9 4729.01
  4792.5  4859.4  4908.4  4916.9  4954.6  4955.6  4971.8  4982.8    4994  4996.7
    5000    5006  5006.1  5024.1  5024.2  5035.7 5035.81  5038.6  5073.3  5078.3
  5121.1  5235.4    5264    5304    5324    5344    5374    5394  5398.5  5418.5
  5508.5  5528.5  5608.5  5648.5  5668.5  5678.5  5778.5  5898.5  5948.5  6018.5
  6056.5
    28.5   27.45   27.21    26.9   26.53   26.51   26.49   26.22   27.52   27.52
   27.05   26.42   26.44   26.44   26.08   26.07   25.93   25.93   25.93   25.93
   25.92   25.92   25.92   25.92   25.92   25.79   24.49   24.46   24.08   24.03
   23.83   23.82    23.8   23.77   23.76   23.75   23.73   26.21   26.41      27
    27.2    26.9    30.5    31.3    30.8    30.2    30.8    30.5      33      34
    33.5
    28.5   27.44    27.1   25.98    24.1    24.2    23.5   21.84   21.84   21.83
   19.76   17.01   15.11   15.32   16.26    9.73    10.5    9.72    5.26    5.17
    4.88    5.25    4.04   20.18   20.19   20.79   20.79   20.94   19.89   19.61
   17.22   13.65    14.2    14.1    15.1    17.8    23.6    26.2    26.4      27
    27.2    26.9    30.5    31.3    30.8    30.2    30.8    30.5      33      34
    33.5
    4159  4345.6  4404.5  4501.2  4664.5  4674.5  4684.5 4728.79  4728.9 4729.01
  4792.5  4859.4  4908.4  4916.9  4954.6  4955.6  4971.8  4982.8    4994  4996.7
    5000    5006  5006.1  5024.1  5024.2  5035.7 5035.81  5038.6  5073.3  5078.3
  5121.1  5235.4    5264    5304    5324    5344    5374    5394  5398.5  5418.5
  5508.5  5528.5  5608.5  5648.5  5668.5  5678.5  5778.5  5898.5  5948.5  6018.5
  6056.5
    28.5   27.45   27.21    26.9   26.53   26.51   26.49   26.22   27.52   27.52
   27.05   26.42   26.44   26.44   26.08   26.07   25.93   25.93   25.93   25.93
   25.92   25.92   25.92   25.92   25.92   25.79   24.49   24.46   24.08   24.03
   23.83   23.82    23.8   23.77   23.76   23.75   23.73   26.21   26.41      27
    27.2    26.9    30.5    31.3    30.8    30.2    30.8    30.5      33      34
    33.5
    28.4   27.34      27   25.88      24    24.1    23.4   21.74   21.74   21.73
   19.66   16.91   15.01   15.22   16.16    9.63    10.4    9.62    5.16    5.07
    4.78    5.15    3.94   20.08   20.09   20.69   20.69   20.84   19.79   19.51
   17.12   13.55    14.1      14      15    17.7    23.5    26.1    26.3    26.9
    27.1    26.8    30.4    31.2    30.7    30.1    30.7    30.4    32.9    33.9
    33.4
BR Coef= 1 , 0 , 0 ,1.25, 0 ,,,0.8,-1,2,0,
WSPro=,,,, 1 ,,,, 0 ,,,, 0 ,,,,-1 ,-1 ,-1 , 0 , 0 , 0 , 0 , 0
Culvert=2,18,14,152.2,0.015,0.4,1,8,1,0.32,4963.6,0.47,4963.6,Culvert #1  , 0 ,10
Culvert Bottom n=0.015
Culvert=2,18,14,152.2,0.015,0.4,1,8,1,0.32,4981,0.47,4981,Culvert #2  , 0 ,10
Culvert Bottom n=0.015
Culvert=2,18,14,152.2,0.015,0.4,1,8,1,0.32,4998.9,0.47,4998.9,Culvert #3  , 0 ,10
Culvert Bottom n=0.015
BR U #Sta/Elev= 63
    4159    28.5  4345.6   27.44  4404.5    27.1  4501.2   25.98  4664.5    24.1
  4674.5    24.2  4684.5    23.5  4689.1   23.33 4728.79   21.84  4728.9   21.84
 4729.01   21.83    4735   21.61  4745.5   21.27  4792.5   19.76  4804.1   19.28
  4853.6   17.24  4859.4   17.01  4908.4   15.11  4916.9   15.32  4954.6   16.26
  4955.6    9.73  4970.2   10.42  4971.8    10.5  4982.8    9.72    4994    5.26
  4996.7    5.17    5000    4.88    5006    5.25  5006.1    4.04  5024.1   20.18
  5024.2   20.19 5035.59   20.78  5035.7   20.79 5035.81   20.79  5038.6   20.94
  5073.3   19.89  5078.3   19.61  5121.1   17.22    5128      17  5172.5   15.61
  5235.4   13.65  5235.5   13.65    5264    14.2    5304    14.1    5324    15.1
    5344    17.8    5374    23.6    5394    26.2  5398.5    26.4  5411.9    26.8
  5418.5      27  5508.5    27.2  5528.5    26.9  5608.5    30.5  5648.5    31.3
  5668.5    30.8  5678.5    30.2  5778.5    30.8  5898.5    30.5  5948.5      33
  5977.4   33.41  6018.5      34  6056.5    33.5
BR U #Mann= 5
    4159      .2  4345.6      .1  4954.6    .055  5024.1      .1  5977.4      .2
BR U Banks=4954.6,5024.1
BR D #Sta/Elev= 63
    4159    28.4  4345.6   27.34  4404.5      27  4501.2   25.88  4664.5      24
  4674.5    24.1  4684.5    23.4  4689.1   23.23 4728.79   21.74  4728.9   21.74
 4729.01   21.73    4735   21.51  4745.5   21.17  4792.5   19.66  4804.1   19.18
  4853.6   17.14  4859.4   16.91  4908.4   15.01  4916.9   15.22  4954.6   16.16
  4955.6    9.63  4970.2   10.32  4971.8    10.4  4982.8    9.62    4994    5.16
  4996.7    5.07    5000    4.78    5006    5.15  5006.1    3.94  5024.1   20.08
  5024.2   20.09 5035.59   20.68  5035.7   20.69 5035.81   20.69  5038.6   20.84
  5073.3   19.79  5078.3   19.51  5121.1   17.12    5128    16.9  5172.5   15.51
  5235.4   13.55  5235.5   13.55    5264    14.1    5304      14    5324      15
    5344    17.7    5374    23.5    5394    26.1  5398.5    26.3  5411.9    26.7
  5418.5    26.9  5508.5    27.1  5528.5    26.8  5608.5    30.4  5648.5    31.2
  5668.5    30.7  5678.5    30.1  5778.5    30.7  5898.5    30.4  5948.5    32.9
  5977.4   33.31  6018.5    33.9  6056.5    33.4
BR D #Mann= 5
    4159      .2  4345.6      .1  4954.6    .055  5024.1      .1  5977.4      .2
BR D Banks=4954.6,5024.1
BC Design=,, 0 ,, 0 ,,,,,,
BC HTab HWMax=34.06
BC Use User HTab Curves=0
BC User HTab FreeFlow(D)= 0

Type RM Length L Ch R = 1 ,2448.5  ,195.2,196.2,198.7
BEGIN DESCRIPTION:
Downstream Section of Bridge/Culvert/Weir
END DESCRIPTION:
XS GIS Cut Line= 6
      3157540.24     13815569.21      3157732.35      13815286.1
      3157897.85     13815161.98       3158486.3     13814775.81
      3158642.61     13814660.87      3158982.76     13814365.33
#Sta/Elev= 30
    4159   28.37  4345.6   27.31  4674.5   24.07  4908.4   14.98  4954.6   16.13
  4955.6     9.6  4971.8   10.37  4982.8    9.59    4994    5.13    5006    5.12
  5006.1    3.91  5024.1   20.05  5038.6   20.81  5073.3   19.76  5121.1   17.09
  5235.4   13.52    5304   13.97    5324   14.97    5344   17.67    5374   23.47
    5394   26.07  5418.5   26.87  5528.5   26.77  5608.5   30.37  5648.5   31.17
  5678.5   30.07  5898.5   30.37  5948.5   32.87  5977.4   33.28  6056.5   33.37
#Mann= 5 , 1 , 0
    4159      .2       0  4345.6      .1       0  4954.6    .055       0
  5024.1      .1       0  5977.4      .2       0
#XS Ineff= 2 , 0
       0    4947   25.81    5016       0   23.73
Permanent Ineff=
       F       F
Bank Sta=4954.6,5024.1
XS Rating Curve= 0 ,0
Exp/Cntr=0.5,0.3

Type RM Length L Ch R = 1 ,2252.3  ,562.8,554.7,501.4
BEGIN DESCRIPTION:
Cross Section 2252.3-Interpolated
END DESCRIPTION:
XS GIS Cut Line= 5
      3157832.22     13815635.86       3158181.7      13815193.6
      3158259.02     13815094.63      3158654.89      13814723.5
      3158654.89      13814723.5
#Sta/Elev= 25
  4374.3    28.3  4380.8   28.26  4724.3    25.9  4934.3    22.8    4948    21.8
    4958    19.5  4983.6    7.23  4990.7    4.93  4995.8     3.7  4999.1    3.27
    5007    3.75  5009.3    3.99  5026.1    13.7  5063.6    18.4  5083.6    22.5
  5093.6    23.8  5113.6    24.9  5163.6    26.1  5193.6    28.4  5213.6      29
  5233.6    27.5  5263.6    27.7  5280.3    27.2  5303.6    26.5  5606.2    28.3
#Mann= 5 , 1 , 0
  4374.3      .2       0  4380.8      .1       0  4983.6    .055       0
  5026.1     .14       0  5280.3      .1       0
Bank Sta=4983.6,5026.1
XS Rating Curve= 0 ,0
Exp/Cntr=0.3,0.1

Type RM Length L Ch R = 1 ,1697.6  ,710,813.7,741.5
BEGIN DESCRIPTION:
Cross Section 1697.6
END DESCRIPTION:
XS GIS Cut Line= 4
      3158117.89     13815919.31      3158559.23     13815776.79
      3158735.79     13815297.88      3159004.16     13814674.57
#Sta/Elev= 30
  4021.4    27.2  4091.4    27.1  4121.4    26.5  4485.2    26.3  4495.2      26
  4535.2    26.6  4645.2    25.9  4712.8    24.4  4825.2    21.9  4895.2    16.4
  4925.2    13.3  4936.3   13.84  4970.7   10.66  4983.6    5.42  4990.7    3.12
  4995.8    1.89  4999.1    1.46  5009.3    2.18  5026.1   11.89    5089   21.14
  5123.4   23.14  5145.6    25.8  5155.6      26  5185.6    25.9  5205.6    26.3
  5235.6    25.6  5338.5   26.42  5435.6    27.2  5545.6    27.9  5674.2    27.7
#Mann= 6 , 1 , 0
  4021.4      .2       0  4021.4      .1       0  4712.8     .14       0
  4983.6    .055       0  5026.1     .14       0  5338.5      .1       0
Bank Sta=4983.6,5026.1
XS Rating Curve= 0 ,0
Exp/Cntr=0.3,0.1

Type RM Length L Ch R = 1 ,883.9   ,0,0,0
BEGIN DESCRIPTION:
Cross Section 883.9
END DESCRIPTION:
XS GIS Cut Line= 5
      3158975.55     13815961.96      3159209.04     13815853.66
      3159294.46     13815717.46      3159562.25     13815345.78
       3159587.2     13815186.88
#Sta/Elev= 30
  4368.6    26.2  4410.3    25.4  4426.8    25.6  4542.6    25.4    4626    26.2
  4678.8    26.4  4786.7    26.8  4823.7    26.4  4882.5    23.6    4901    21.2
  4930.3   15.66    4957   12.82  4984.5    7.41  4992.6     .53  4992.8    1.01
  5001.2     -.2  5007.1     .52  5007.3     .96  5018.3    5.77  5040.8    8.71
  5049.5    9.29  5070.3   10.68  5085.8    17.6  5101.3    19.9  5141.3    22.5
  5159.8    22.8  5196.8    22.7  5244.8    24.3  5326.8    26.1  5405.7    26.3
#Mann= 6 , 1 , 0
  4368.6      .1       0  4678.8     .14       0  4984.5    .055       0
  5018.3     .14       0  5049.5      .1       0  5405.7      .2       0
Bank Sta=4984.5,5018.3
XS Rating Curve= 0 ,0
Exp/Cntr=0.3,0.1

Chan Stop Cuts=-1
Use User Specified Reach Order=0
Composite Channel Slope=5